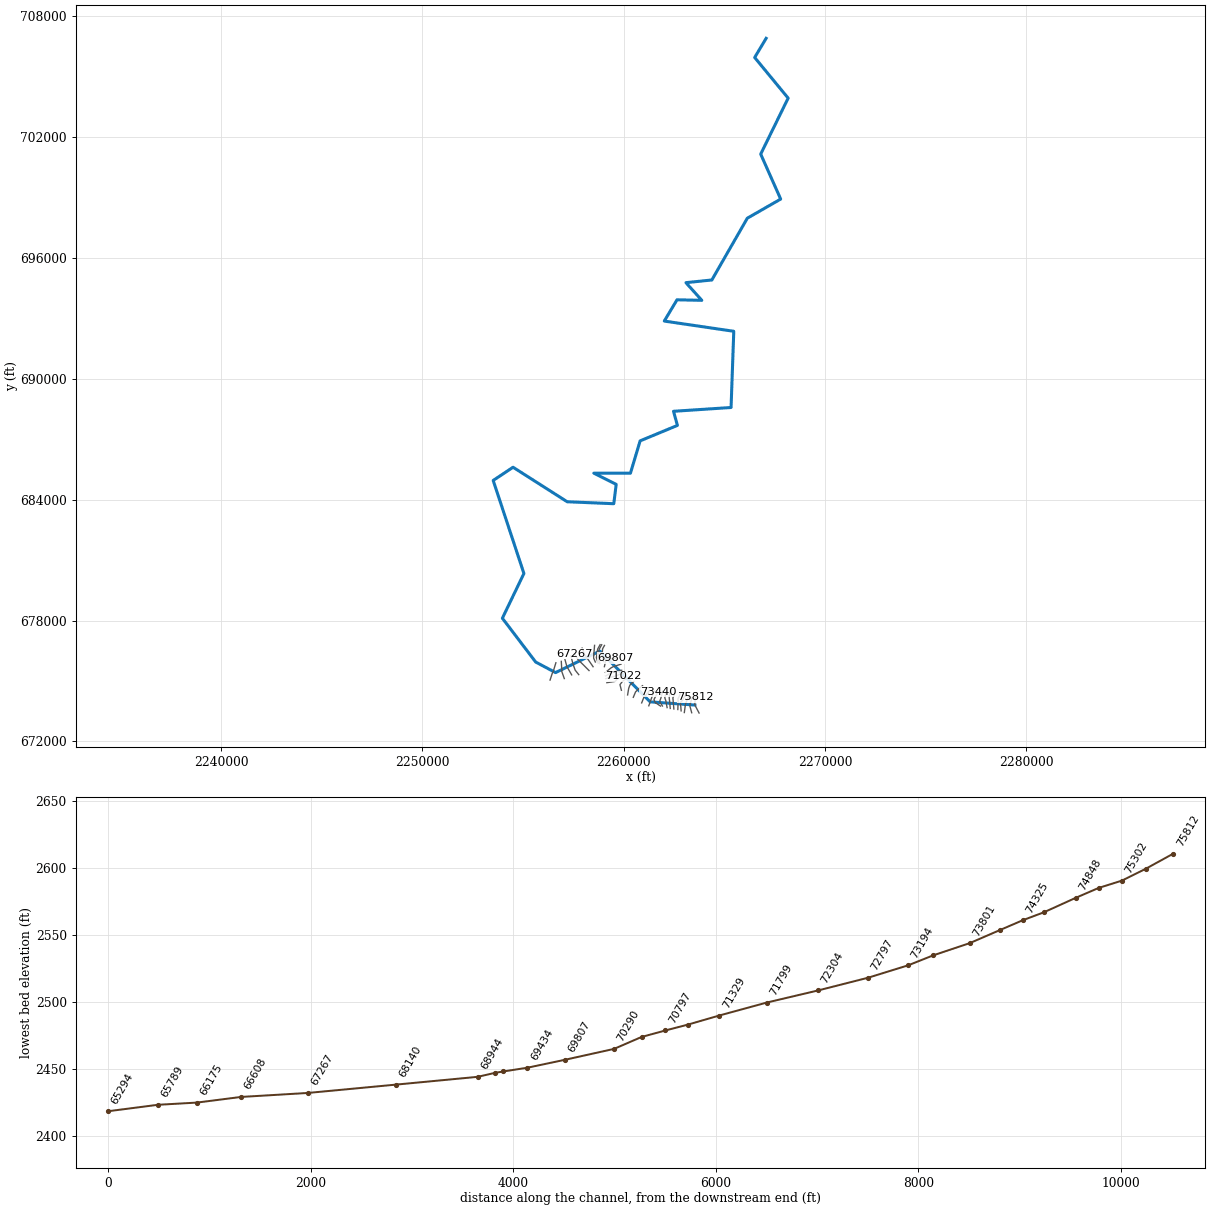
--- ROARCK.prj (project) ---

Proj Title=ROARCK
Current Plan=p01
Default Exp/Contr=0,0
English Units
Geom File=g01
Flow File=f01
Plan File=p01
BEGIN DESCRIPTION:
----------MODEL BY WOOD PLC 2022----------
AFH study
Randolph County, WV
HEC-RAS Version: RAS 6.2
Vertical Datum: NAVD88
Projection: NAD 1983 StatePlane West Virginia S FIPS 4702 (US Feet)
Terrain: 1-meter LIDAR (FEMA Region III 3DEP collected 2016-2018)
Land Use: 2019 NLCD
Hydrologic Method:
WV SIR2010-5033 regression equations
Additional Model Notes:
None
END DESCRIPTION:
DSS Export Rating Curves= 0
DSS Export Rating Curve Sorted= 0
DSS Export Volume Flow Curves= 0
DXF OffsetX= 0
DXF OffsetY= 0
DXF ScaleX= 0
DXF ScaleY= 0

--- ROARCK.p01 (plan) ---

Plan Title=Floodplain
Program Version=4.00
Geom File=g01
Flow File=f01
K Sum by GR=0
Std Step Tol=0.01
Critical Tol=0.01
Num of Std Step Trials=20
Max Error Tol=0.3
Flow Tol Ratio=0.001
Split Flow NTrial=30
Split Flow Tol=0.02
Split Flow Ratio=0.02
Log Output Level=0
Friction Slope Method=1
Unsteady Friction Slope Method=2
Unsteady Bridges Friction Slope Method=1
Global Log Level=0
CheckData=False
Run HTab=0
Run UNet=0
Run PostProcess=0
UNET Theta=0
UNET Theta Warmup=0
UNET ZTol=0
UNET ZSATol=0
UNET MxIter=0
UNET MaxInSteps=0
UNET DtIC=0
UNET DtMin=0
UNET MaxCRTS=0
UNET WFStab=0
UNET SFStab=0
UNET WFX=0
UNET SFX=0
UNET DSS MLevel=0
UNET DZMax Abort=0
UNET Convert EG Bridges=0
UNET Use Existing IB Tables=0
UNET Froude Limit=0
UNET Froude Power=0
Write IC File=0
Echo Input=False
Echo Output=False
Write Detailed=0

--- ROARCK.f01 (steady flow) ---

Flow Title=Flow
Program Version=6.20
Number of Profiles= 1
Profile Names=P100yr
River Rch & RM=ROARCK,Main,75812
     550
River Rch & RM=ROARCK,Main,69434
     622
River Rch & RM=ROARCK,Main,64036
     694
River Rch & RM=ROARCK,Main,60979
     873
River Rch & RM=ROARCK,Main,57717
    1280
River Rch & RM=ROARCK,Main,56825
    1430
River Rch & RM=ROARCK,Main,51265
    2300
River Rch & RM=ROARCK,Main,46906
    2560
River Rch & RM=ROARCK,Main,33666
    3040
River Rch & RM=ROARCK,Main,29243
    3460
River Rch & RM=ROARCK,Main,22240
    3850
River Rch & RM=ROARCK,Main,10606
    4370
Boundary for River Rch & Prof#=ROARCK,Main            , 1
Up Type= 0
Dn Type= 3
Dn Slope=0.01168
DSS Import GetInterval= 0
DSS Import GetPeak= 0
DSS Import FillOption= 0

--- ROARCK.g01 (geometry) ---

Geom Title=Geometry
Program Version=6.20

River Reach=ROARCK          ,Main
Reach XY= 30
     2263533.921      673806.236     2261311.067      673965.128
2258815.18633084 676487.16165418     2256614.299      675417.174
     2255626.037      675941.542     2253972.106      678116.975
     2255042.144      680338.392     2253515.996      684957.786
     2254503.312      685613.405     2257191.924      683899.492
     2259504.747      683802.879     2259624.628        684762.6
     2258512.784      685320.055 2260332.4636888685316.998957349
     2260813.803      686922.577     2262666.209      687690.272
2262471.66992582688390.797820863     2265329.944      688579.396
     2265464.752      692363.204     2262013.973      692870.613
     2262644.314      693926.152     2263877.497      693901.263
     2263087.556      694778.107     2264376.064      694910.825
     2266137.552      697978.784     2267794.181      698927.097
     2266801.773       701160.75     2268164.994      703939.873
     2266502.607      705957.919     2267072.221       706909.63

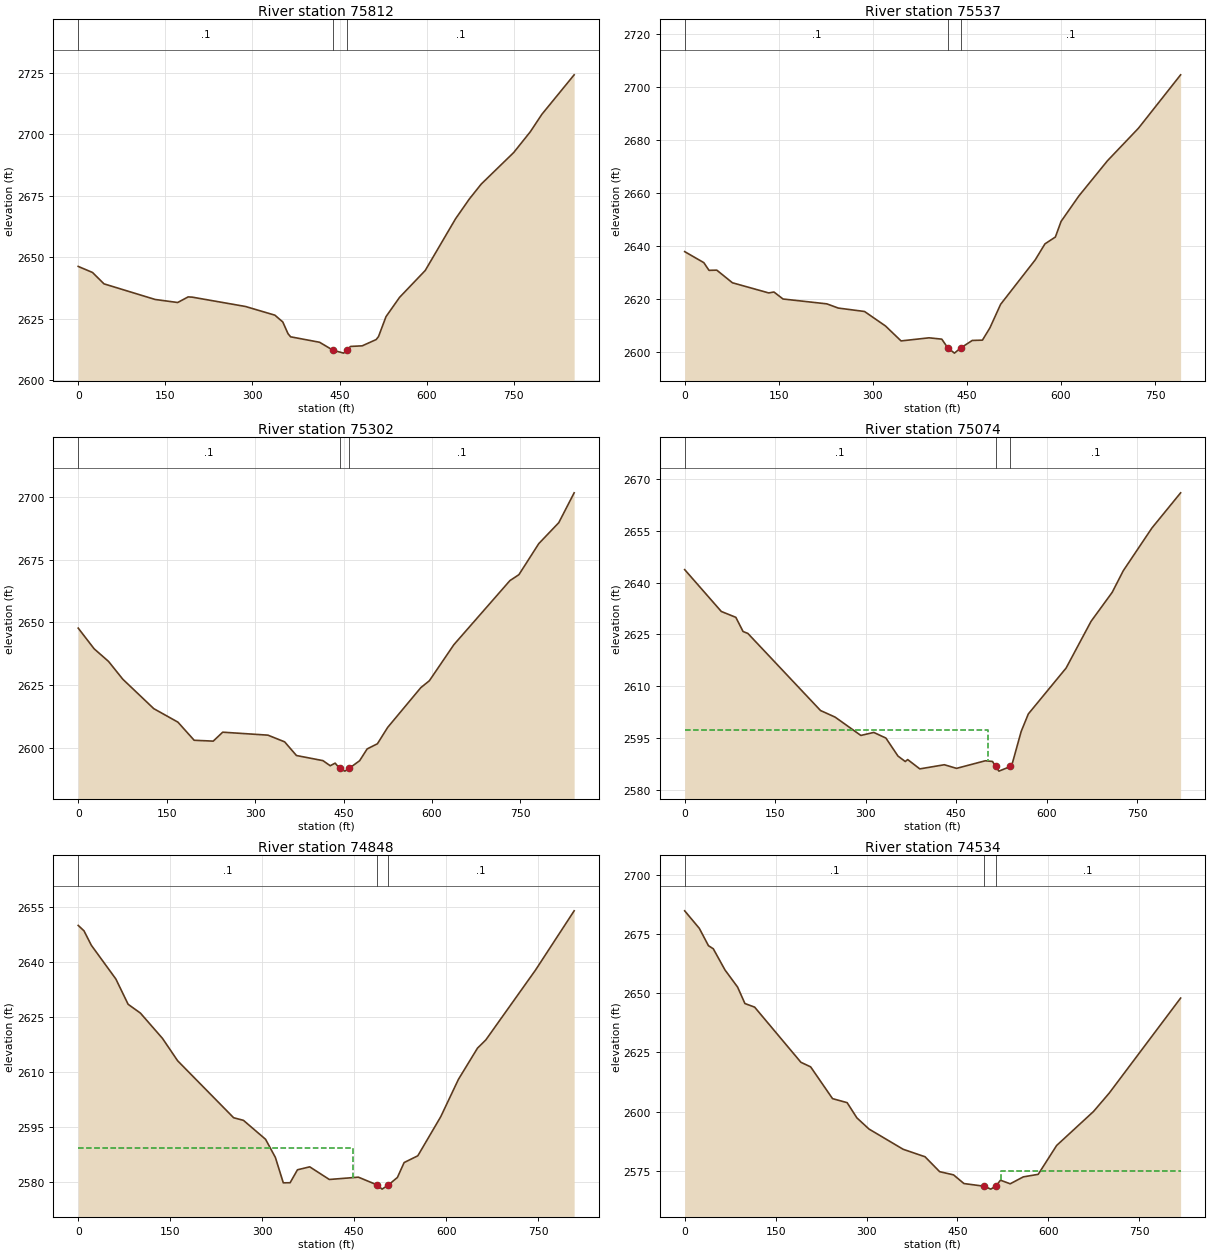
Type RM Length L Ch R = 1 ,75812   ,278.5,275.5,262.8
XS GIS Cut Line= 4
 2263742.1144084673409.888912911 2263545.9263123673780.770687697
2263525.35582057673822.2384301152263561.55121703674208.481086248
#Sta/Elev= 30
       0 2646.28    24.6 2643.82    44.4 2639.19   132.5 2632.84   171.2 2631.61
   189.3 2633.89   196.2 2633.79     288 2629.99   338.6 2626.46   352.2  2623.7
   361.2 2618.93   365.7 2617.66   415.5 2615.45  438.642612.206     457 2611.03
  462.532612.205   468.8 2613.75   488.9 2613.99     513 2616.55     517 2617.77
   529.9 2625.87   553.2 2633.69   597.4 2644.62   649.6 2665.64   673.2 2673.64
   693.8 2679.75   749.7 2692.57   778.2 2700.98   798.3 2708.14   853.8 2724.17
#Mann= 3 ,-1,0
       0      .1       0  438.64    .045       0  462.53      .1       0
Bank Sta=438.64,462.53
XS Rating Curve= 0 ,0
Exp/Cntr=0.3,0.1

Type RM Length L Ch R = 1 ,75537   ,234.6,234.1,232.9
XS GIS Cut Line= 4
2263374.71119545673423.7003309942263287.61236322673749.570099843
2263310.13792328673887.5952572132263394.81061423674189.470010492
#Sta/Elev= 30
       0 2637.85    30.5  2633.7    38.8 2630.79    51.2 2630.87    76.1 2626.11
     134 2622.28   142.3 2622.63   156.8 2619.99   226.7 2618.16     245 2616.57
   286.7 2615.29   320.2 2609.82     345 2604.19   389.6 2605.36   409.9 2604.86
  419.592601.555   430.1 2599.59   440.1 2601.54   458.5 2604.37   474.7 2604.48
   486.6 2609.09   503.7 2617.98   558.8 2634.71   574.4 2640.77     591 2643.35
   600.1 2649.23   628.4 2658.81   674.1 2672.11   723.4 2684.34   790.7 2704.49
#Mann= 3 ,-1,0
       0      .1       0  419.59    .045       0   440.1      .1       0
Bank Sta=419.59,440.1
XS Rating Curve= 0 ,0
Exp/Cntr(USF)=0,0
Exp/Cntr=0.3,0.1

Type RM Length L Ch R = 1 ,75302   ,233.5,228.2,222.7
XS GIS Cut Line= 4
2263008.81153199673434.2853446132263062.19238089673828.391176804
2263083.75339695673907.8906155852263222.59242298674241.258479205
#Sta/Elev= 30
       0 2647.74    27.1 2639.49    51.4  2634.5    75.6 2627.41   128.1  2615.7
   169.1 2610.32   196.7  2603.1     229 2602.76   245.1 2606.32   321.8 2605.14
   350.1 2602.48   370.2 2597.03   415.1    2595   427.5 2592.96   435.8    2594
  443.392591.919   452.4 2590.82  459.472591.918   477.3 2594.95   490.1 2599.66
   507.5 2601.71   524.8 2608.19   581.1 2624.04   595.6 2626.79   637.2 2641.15
   732.2 2666.64   747.5 2669.01   781.2 2681.37   815.1  2689.7   841.2 2701.59
#Mann= 3 ,-1,0
       0      .1       0  443.39    .045       0  459.47      .1       0
Bank Sta=443.39,459.47
XS Rating Curve= 0 ,0
Exp/Cntr=0.3,0.1

Type RM Length L Ch R = 1 ,75074   ,217.1,226.7,237.5
XS GIS Cut Line= 4
2262850.53916709673516.6928428792262816.29402486673937.814192588
2262913.79093974674030.0053054972263035.42896406674265.983072672
#Sta/Elev= 30
       0 2643.79    60.7 2631.67    84.8 2629.97    96.8 2625.86   104.8  2625.3
   225.2 2602.97   249.3 2601.07   292.1 2595.75   313.5 2596.62   333.6 2594.99
   353.6 2589.78   365.7 2588.19   369.7 2588.76   389.8 2586.06   430.5 2587.26
   450.7 2586.21   498.4 2588.41   510.4 2588.21 515.3652586.752     521 2585.41
 540.0352586.752   543.6 2587.91   557.8 2596.87   569.7 2601.97   632.3 2615.26
   673.7  2628.8   708.8 2637.22   727.1 2643.46   774.6 2655.84   822.2 2666.04
#Mann= 3 ,-1,0
       0      .1       0 515.365    .045       0 540.035      .1       0
#XS Ineff= 2 , 0
          502.14 2597.45
Permanent Ineff=
       F       F
Bank Sta=515.365,540.035
XS Rating Curve= 0 ,0
Exp/Cntr(USF)=0,0
Exp/Cntr=0.3,0.1

Type RM Length L Ch R = 1 ,74848   ,313.2,313.7,311.3
XS GIS Cut Line= 4
 2262686.1570175673583.7800148042262700.78981848674031.834605001
2262689.71165506674103.2799871832262813.95516554674363.450839846
#Sta/Elev= 30
       0 2649.92     9.4 2648.45    21.4 2644.51    61.4 2635.31    81.4 2628.41
   101.5    2626   137.5  2619.1   162.2    2613   253.5 2597.47   269.5 2596.76
   305.6 2591.59   321.6 2586.64   334.5 2579.72   345.6 2579.74   357.6 2583.27
   377.6 2584.08   409.6 2580.63     457 2581.26  488.082579.106   495.6    2578
  505.662579.105   520.6 2581.18   531.6 2585.25   553.9 2587.09   591.3 2597.75
   620.2 2607.95   651.2 2616.44   664.9 2618.71   745.9 2637.75   808.9  2653.9
#Mann= 3 ,-1,0
       0      .1       0  488.08    .045       0  505.66      .1       0
#XS Ineff= 2 , 0
          448.28  2589.1
Permanent Ineff=
       F       F
Bank Sta=488.08,505.66
XS Rating Curve= 0 ,0
Exp/Cntr=0.3,0.1

Type RM Length L Ch R = 1 ,74534   ,207.8,208.7,205.4
XS GIS Cut Line= 4
2262489.17638703673610.1645317792262450.39157153674058.652562835
2262441.77244709674164.236837194 2262543.7654196674405.572321444
#Sta/Elev= 30
       0 2684.72    24.2 2677.31    39.2 2670.01    47.2  2668.7    66.5 2659.76
    87.3 2652.53    99.4 2645.58   115.4 2644.07   191.7 2620.79   207.8 2618.85
   243.9 2605.44     268 2603.74   284.1 2597.31   304.1  2592.6   360.4 2584.06
   396.5  2580.9   420.6 2574.61   443.5 2573.26   460.7 2569.59   494.12568.463
   504.9 2567.24  513.232568.452   520.9 2571.01     537 2569.49   558.6 2572.41
   583.2 2573.49   613.6 2585.67   674.4 2600.01   700.4  2607.8   818.1 2647.89
#Mann= 3 ,-1,0
       0      .1       0   494.1    .045       0  513.23      .1       0
#XS Ineff= 2 , 0
                          521.08         2574.74
Permanent Ineff=
       F       F
Bank Sta=494.1,513.23
XS Rating Curve= 0 ,0
Exp/Cntr(USF)=0,0
Exp/Cntr=0.3,0.1

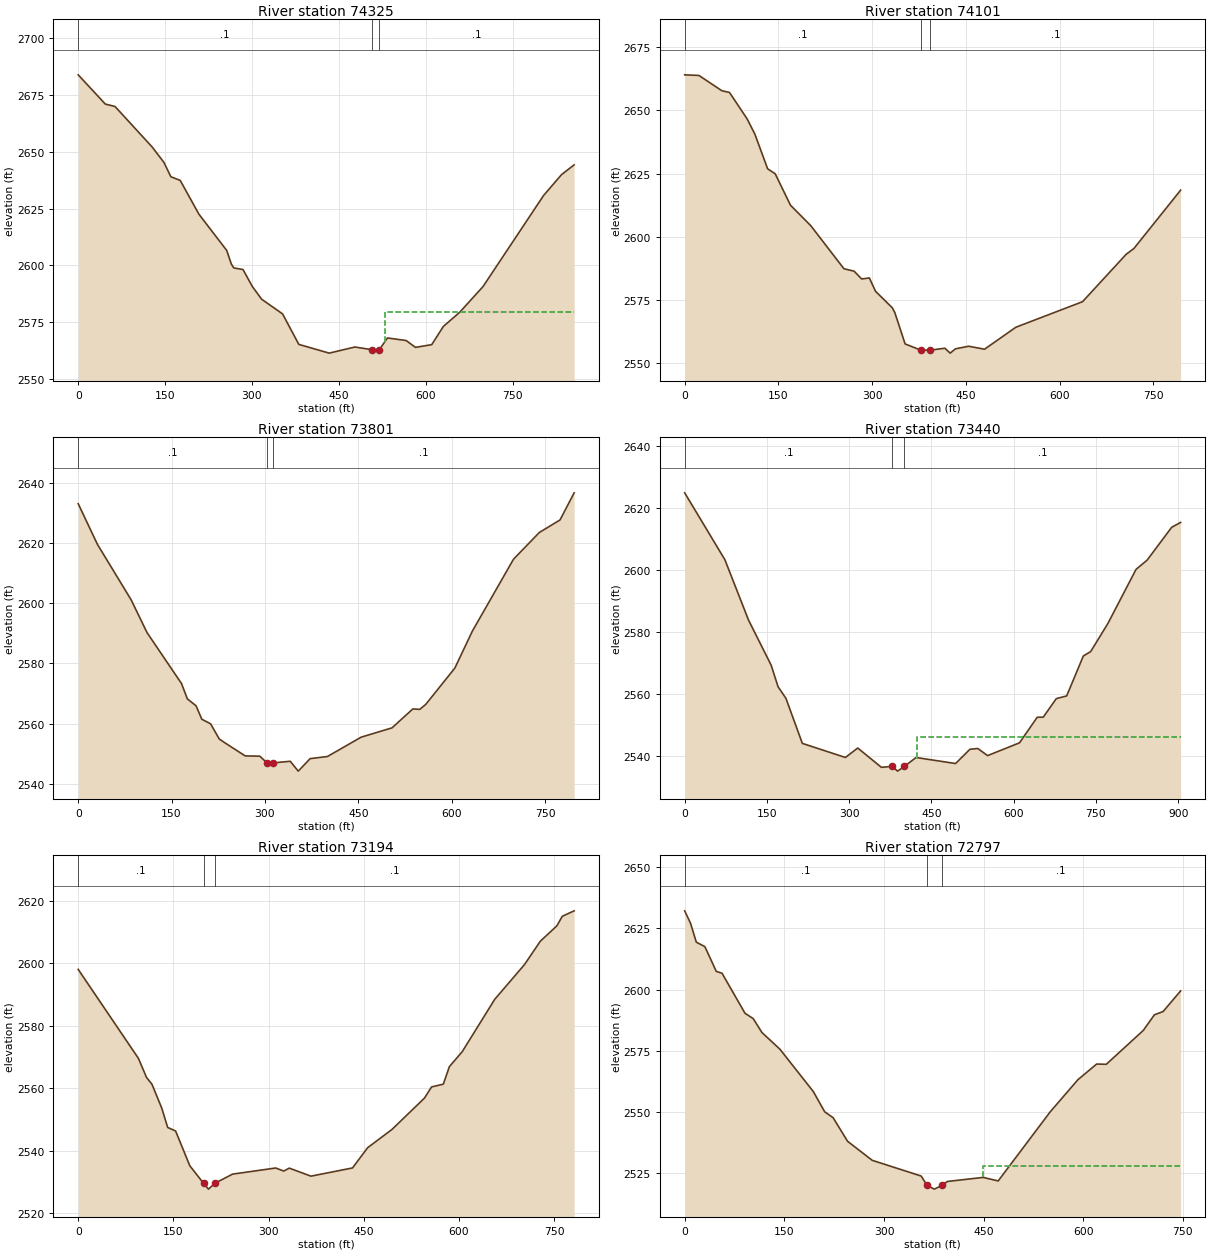
Type RM Length L Ch R = 1 ,74325   ,222.5,224.5,224.9
XS GIS Cut Line= 4
2262309.15604038673637.7961185882262276.05102614 674006.10820259
2262257.18863685674172.7871960272262289.36880827674489.802064755
#Sta/Elev= 30
       0 2683.95    46.8 2671.06    63.6 2669.99   127.9 2652.08     148 2645.35
     160 2639.03   176.1 2637.43   208.2 2622.61   256.4 2606.56   264.4 2600.54
   268.5 2598.87   284.5 2598.15   300.6 2590.69   316.7 2585.06   352.8  2578.6
   380.9 2565.16   433.3 2561.31   477.6    2564   507.52562.815  519.772562.801
   533.9    2568   566.2 2566.86   582.2 2563.85   610.3 2565.04   630.4 2573.07
   658.6 2579.32   698.8 2590.62   803.4 2630.76   834.4 2639.97   856.2 2644.29
#Mann= 3 ,-1,0
       0      .1       0   507.5    .045       0  519.77      .1       0
#XS Ineff= 2 , 0
                          529.42         2579.52
Permanent Ineff=
       F       F
Bank Sta=507.5,519.77
XS Rating Curve= 0 ,0
Exp/Cntr=0.3,0.1

Type RM Length L Ch R = 1 ,74101   ,301.9,300,294.3
XS GIS Cut Line= 4
2262153.80434284673678.726554705 2262090.5525702 674018.09664255
2262038.24821974 674167.711412462262103.93275287674449.911628876
#Sta/Elev= 30
       0 2664.11    22.8 2663.87    59.5 2657.82    71.7 2657.14   100.1 2646.61
   112.4  2640.6   132.7 2626.94   144.9 2624.94   169.3 2612.53   201.9 2604.39
   254.8  2587.4   271.1 2586.43   283.2 2583.35   295.5 2583.75   305.3  2578.5
   332.1 2571.96   336.2 2570.07   352.7 2557.65   377.8 2555.19  392.652555.177
   416.3 2555.95   424.8 2554.01   433.2 2555.71   454.4 2556.74   479.8 2555.56
   529.9 2564.25   636.6 2574.36   706.4 2593.11   718.8 2595.41   793.5 2618.49
#Mann= 3 ,-1,0
       0      .1       0   377.8    .045       0  392.65      .1       0
Bank Sta=377.8,392.65
XS Rating Curve= 0 ,0
Exp/Cntr(USF)=0,0
Exp/Cntr=0.3,0.1

Type RM Length L Ch R = 1 ,73801   ,353.6,360.6,363
XS GIS Cut Line= 4
2261921.36888089 673758.688042552261785.14993239673986.572071197
2261837.33961076674128.7188729022261937.66303634674495.063978467
#Sta/Elev= 30
       0 2633.11    30.9 2619.58    84.9  2601.2   110.6 2590.24     166  2573.3
   175.3 2568.24   189.4 2565.89   198.6 2561.44   212.7 2559.93   226.6 2554.88
     236 2553.56   268.3 2549.25   291.7 2549.16   303.32546.955  312.792546.918
   340.7 2547.47   353.5 2544.19   372.7 2548.35   400.4 2549.05   454.7 2555.49
   504.2 2558.58   537.7 2564.88   548.8 2564.72   558.4 2566.38   605.2 2578.47
   633.1 2590.68   699.4 2614.66   740.9 2623.54   774.1  2627.7   796.8 2636.72
#Mann= 3 ,-1,0
       0      .1       0   303.3    .045       0  312.79      .1       0
Bank Sta=303.3,312.79
XS Rating Curve= 0 ,0
Exp/Cntr=0.3,0.1

Type RM Length L Ch R = 1 ,73440   ,251,246.4,239.9
XS GIS Cut Line= 4
2261827.46496705673754.8929817842261553.10364553 673937.35001826
  2261504.260484674084.7123905592261692.61576836674459.775860952
#Sta/Elev= 30
       0 2624.78    73.3 2603.23   116.5 2583.75   157.7 2569.23   170.3 2562.29
   184.7 2558.52   214.6 2544.02   293.1 2539.48   315.6 2542.53   358.8  2536.3
   378.2 2536.62   388.3 2535.08  400.672536.613     422 2539.47     494 2537.53
   520.2 2542.12   534.5 2542.38   552.4 2540.08   610.6  2544.2   642.9 2552.44
   653.9 2552.47   677.7 2558.45   696.6 2559.32     727 2572.19   740.4 2573.61
   771.7 2582.65   823.2 2600.13   843.3 2603.08   888.1 2613.67   904.4 2615.24
#Mann= 3 ,-1,0
       0      .1       0   378.2    .045       0  400.67      .1       0
#XS Ineff= 2 , 0
                           424.3         2546.05
Permanent Ineff=
       F       F
Bank Sta=378.2,400.67
XS Rating Curve= 0 ,0
Exp/Cntr(USF)=0,0
Exp/Cntr=0.3,0.1

Type RM Length L Ch R = 1 ,73194   ,400.5,397,392.3
XS GIS Cut Line= 4
2261243.83975506673768.2582166792261303.87608004673930.047767766
2261331.71139319674014.9811591752261511.10013783674502.697700509
#Sta/Elev= 30
       0  2598.1    94.8 2569.62   107.6  2563.5   116.2 2561.31   131.7 2553.62
     141 2547.44   153.5  2546.3   175.9 2535.16  197.592529.516   205.3 2527.67
  215.182529.516   243.2 2532.48   311.2 2534.44     324 2533.46   332.6  2534.4
   366.8 2531.83   432.3 2534.46   456.1 2540.94   494.6 2546.82   545.6 2556.83
   556.9 2560.43   575.4 2561.32     585 2566.94   605.2 2571.73   656.4  2588.5
   703.3 2599.64   728.3 2607.14   754.4 2612.08   762.9 2615.13   781.6 2616.88
#Mann= 3 ,-1,0
       0      .1       0  197.59    .045       0  215.18      .1       0
Bank Sta=197.59,215.18
XS Rating Curve= 0 ,0
Exp/Cntr=0.3,0.1

Type RM Length L Ch R = 1 ,72797   ,491.8,492.2,492.2
XS GIS Cut Line= 4
2260890.83068799673912.8436574132261006.43803301674208.574162356
 2261126.0310074674324.455838489 2261283.8626033674534.189051296
#Sta/Elev= 30
       0 2632.17     8.9 2627.03    17.5 2619.36    30.4 2617.53    47.6 2607.41
    56.2 2606.66    90.8 2590.29   103.2 2588.09   116.3 2582.41   143.3 2575.61
   193.6 2558.29   210.8 2549.99   223.4 2547.59   245.2 2537.94   282.3 2530.16
     356 2523.73  364.862519.881   375.8 2518.38  387.082519.879   395.6 2521.52
   449.3 2523.17   471.9 2521.73     550 2549.91   591.8 2563.09   620.1 2569.52
   634.6 2569.42   690.2 2583.24   707.1 2589.67   720.2 2591.01   746.5 2599.43
#Mann= 3 ,-1,0
       0      .1       0  364.86    .045       0  387.08      .1       0
#XS Ineff= 2 , 0
                          449.16         2528.03
Permanent Ineff=
       F       F
Bank Sta=364.86,387.08
XS Rating Curve= 0 ,0
Exp/Cntr=0.3,0.1

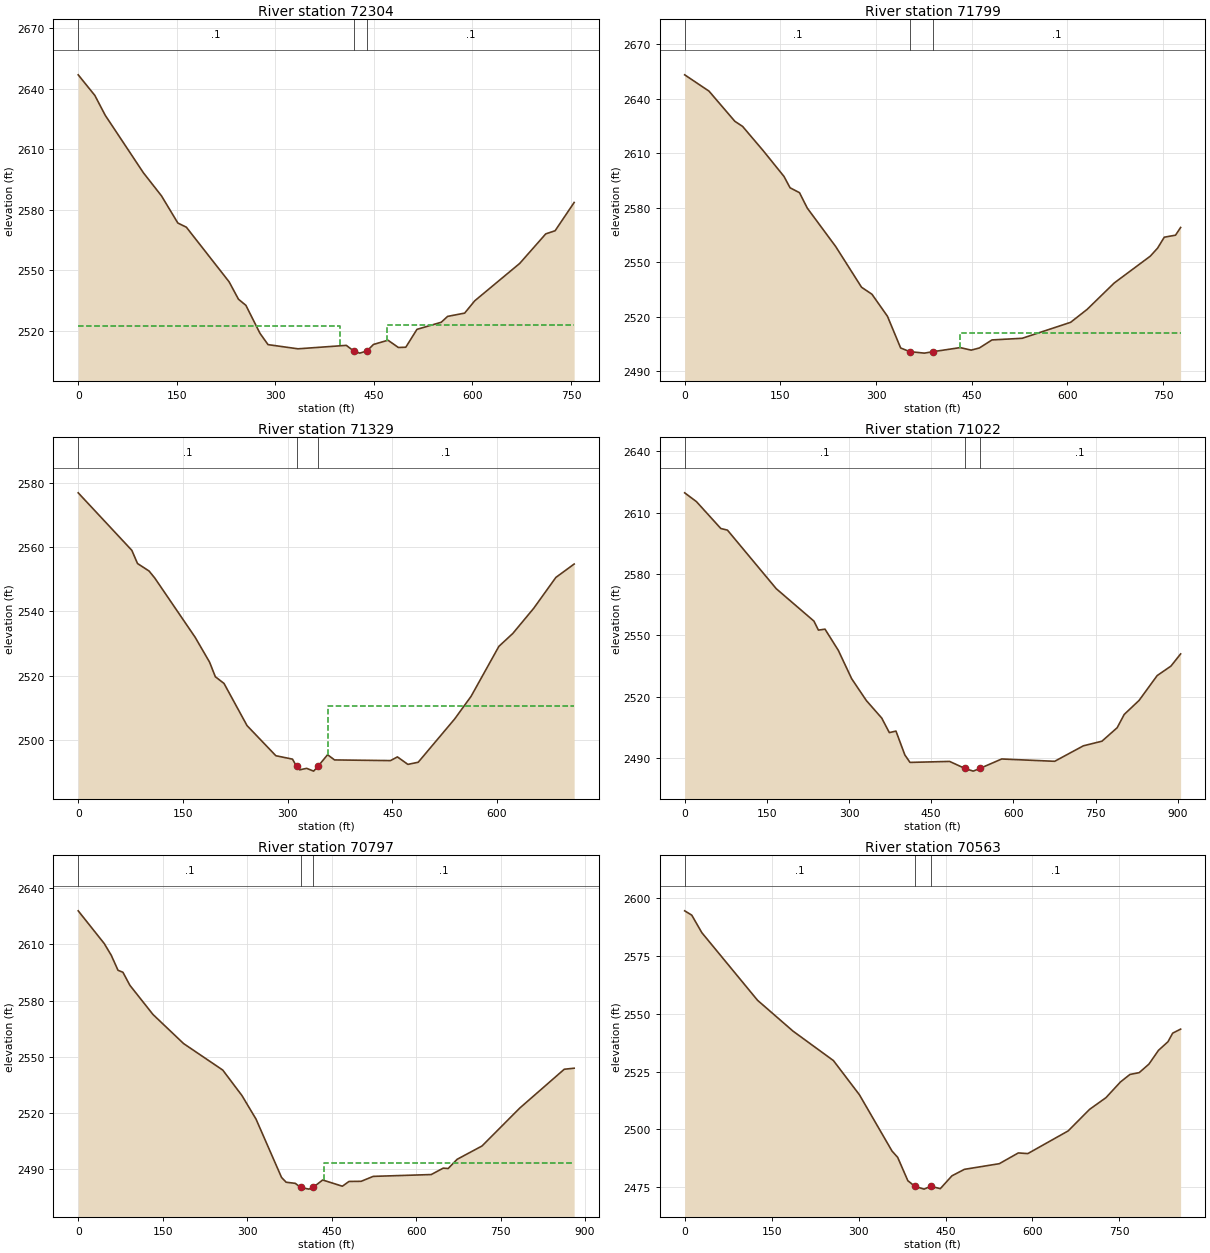
Type RM Length L Ch R = 1 ,72304   ,495.6,505.4,496.2
XS GIS Cut Line= 4
2260474.46501346674189.2049487042260586.86624987674459.341105926
2260741.66160238 674607.235597532260931.97869553674766.207234639
#Sta/Elev= 30
       0 2646.93    25.3 2636.72    41.1 2626.88    99.2 2598.36   126.7 2586.92
   151.6 2573.45   164.6 2571.36   229.6  2544.3   243.9 2535.64   255.2 2532.61
   276.6 2518.75   288.9 2513.13   334.4 2511.06     408 2512.77  419.172509.991
   428.4 2508.92  439.39 2509.99   449.3 2513.22   471.4 2515.32   487.2 2511.72
   498.5 2511.84   515.5 2520.71   552.4 2524.22   562.1 2527.13   588.1 2528.77
   603.3 2534.83   671.9 2553.42   711.5 2568.06   725.7  2569.6   754.7 2583.63
#Mann= 3 ,-1,0
       0      .1       0  419.17    .045       0  439.39      .1       0
#XS Ineff= 2 , 0
          398.61 2522.17  469.94         2522.89
Permanent Ineff=
       F       F
Bank Sta=419.17,439.39
XS Rating Curve= 0 ,0
Exp/Cntr=0.3,0.1

Type RM Length L Ch R = 1 ,71799   ,473.2,469.7,462.8
XS GIS Cut Line= 4
2260191.69399327674307.5972799432260246.23179273 674635.57778062
2260304.85433341674795.893359625 2260505.7998829674982.589671607
#Sta/Elev= 30
       0  2653.2    38.1 2644.24    78.6 2627.62    90.8 2624.79   123.3 2611.34
   155.7 2597.24   165.2 2590.99     180 2588.28   192.2  2579.8   236.8  2558.6
   277.3 2536.19   293.6 2532.35   317.9 2520.21   338.6 2502.74  352.962500.732
   375.8 2499.91  389.742500.727   431.9 2502.95   449.2 2501.57     462 2502.75
   481.8 2507.18   529.1 2508.08     605 2516.87     631 2524.02   673.4 2538.54
     730 2553.33   741.4 2557.75   751.9 2563.77   769.5 2564.87   777.5 2569.12
#Mann= 3 ,-1,0
       0      .1       0  352.96    .045       0  389.74      .1       0
#XS Ineff= 2 , 0
                          432.07         2511.11
Permanent Ineff=
       F       F
Bank Sta=352.96,389.74
XS Rating Curve= 0 ,0
Exp/Cntr=0.3,0.1

Type RM Length L Ch R = 1 ,71329   ,304.4,307.7,302.4
XS GIS Cut Line= 4
2259883.67915989674538.8169955592259812.43972598674817.296729567
2259935.13449528674980.7040719282260110.63194213675111.329927325
#Sta/Elev= 30
       0 2576.97    76.8 2559.05      85 2554.93   101.5  2552.6   109.8 2550.38
   167.6 2531.93   188.2  2524.2   196.5 2519.64   208.9 2517.56   241.9 2504.41
   283.2 2495.02     307 2493.96  312.842491.716   317.3 2490.62   327.3 2491.09
   337.3 2490.22  343.532491.714   357.3 2495.33   367.3 2493.71   447.4  2493.5
   457.4 2494.65   472.4 2492.32   487.2 2492.99   539.5 2506.51   562.9 2513.53
   602.8 2529.12   622.7 2533.13   652.7 2540.99   684.4  2550.6   710.6 2554.77
#Mann= 3 ,-1,0
       0      .1       0  312.84    .045       0  343.53      .1       0
#XS Ineff= 2 , 0
                          358.12         2510.47
Permanent Ineff=
       F       F
Bank Sta=312.84,343.53
XS Rating Curve= 0 ,0
Exp/Cntr=0.3,0.1

Type RM Length L Ch R = 1 ,71022   ,231.9,224.5,217.3
XS GIS Cut Line= 4
2259162.95243597674916.1263436832259565.57429646674978.161736085
2259695.80011053   675113.8826622259983.98248693 675227.66663221
#Sta/Elev= 30
       0  2619.7    21.5 2615.39      66 2602.23    78.1 2601.44   167.2 2572.76
     236  2556.9   244.1 2552.51   256.2 2552.96   280.5 2542.57   304.8 2528.72
   331.6 2518.04   359.7 2509.45   373.6 2502.34   385.7 2503.07   401.9 2491.42
   411.3 2487.75   483.6 2488.23   511.82484.771   526.7 2483.48   538.7 2484.78
   578.7 2489.42   675.4 2488.29   727.8 2495.87   761.7 2498.13   789.5 2504.73
   802.3 2511.21   829.5  2518.1   862.5 2530.25   887.6 2534.88   905.3 2540.85
#Mann= 3 ,-1,0
       0      .1       0   511.8    .045       0   538.7      .1       0
Bank Sta=511.8,538.7
XS Rating Curve= 0 ,0
Exp/Cntr(USF)=0,0
Exp/Cntr=0.3,0.1

Type RM Length L Ch R = 1 ,70797   ,237,234.5,233.1
XS GIS Cut Line= 4
2259107.50605249675119.1748936792259460.93016144675214.405080075
2259534.29721232675225.663913406 2259944.6099825675385.879947512
#Sta/Elev= 30
       0 2627.99    46.3 2610.45    58.7  2604.2    70.7 2596.17    79.4 2595.11
    91.8 2588.13   132.7 2572.55   187.1 2556.96   256.7 2542.77   290.7 2529.17
   315.7 2516.58   361.1  2485.3   369.3 2482.75   385.5 2482.15  394.752480.011
   409.6 2479.06  417.25 2480.01   434.1 2483.95   469.1 2480.62   480.9 2483.17
   502.4 2483.24   523.9 2485.88   626.9 2486.86   648.2 2490.29     657 2490.09
   672.9 2495.02   717.1 2502.15   784.1 2522.43   863.1 2543.21   880.7 2543.77
#Mann= 3 ,-1,0
       0      .1       0  394.75    .045       0  417.25      .1       0
#XS Ineff= 2 , 0
                          436.03         2492.78
Permanent Ineff=
       F       F
Bank Sta=394.75,417.25
XS Rating Curve= 0 ,0
Exp/Cntr=0.3,0.1

Type RM Length L Ch R = 1 ,70563   ,268.4,272.3,276.2
XS GIS Cut Line= 4
 2259106.8537641675249.7697567532259431.46859129675447.842612934
 2259519.4353753675448.8898365532259897.48908907675533.219336387
#Sta/Elev= 30
       0 2594.42    12.2 2592.56    29.6 2584.99   125.7 2555.79   186.8 2542.49
   256.6 2529.75   301.4 2515.01   357.7 2490.68   367.5 2487.94     385 2477.87
     397 2475.47     413 2474.23  424.642475.466     441 2474.43     461 2479.96
   482.5 2482.77   542.8 2485.22   575.6 2489.86     592 2489.58   661.6 2499.37
   698.5 2508.67   726.8 2513.73   751.8 2520.51   768.2 2523.76   784.1 2524.53
     801 2528.24   817.4 2534.16   833.8 2537.88   841.9 2541.59   855.6 2543.33
#Mann= 3 ,-1,0
       0      .1       0     397    .045       0  424.64      .1       0
Bank Sta=397,424.64
XS Rating Curve= 0 ,0
Exp/Cntr(USF)=0,0
Exp/Cntr=0.3,0.1

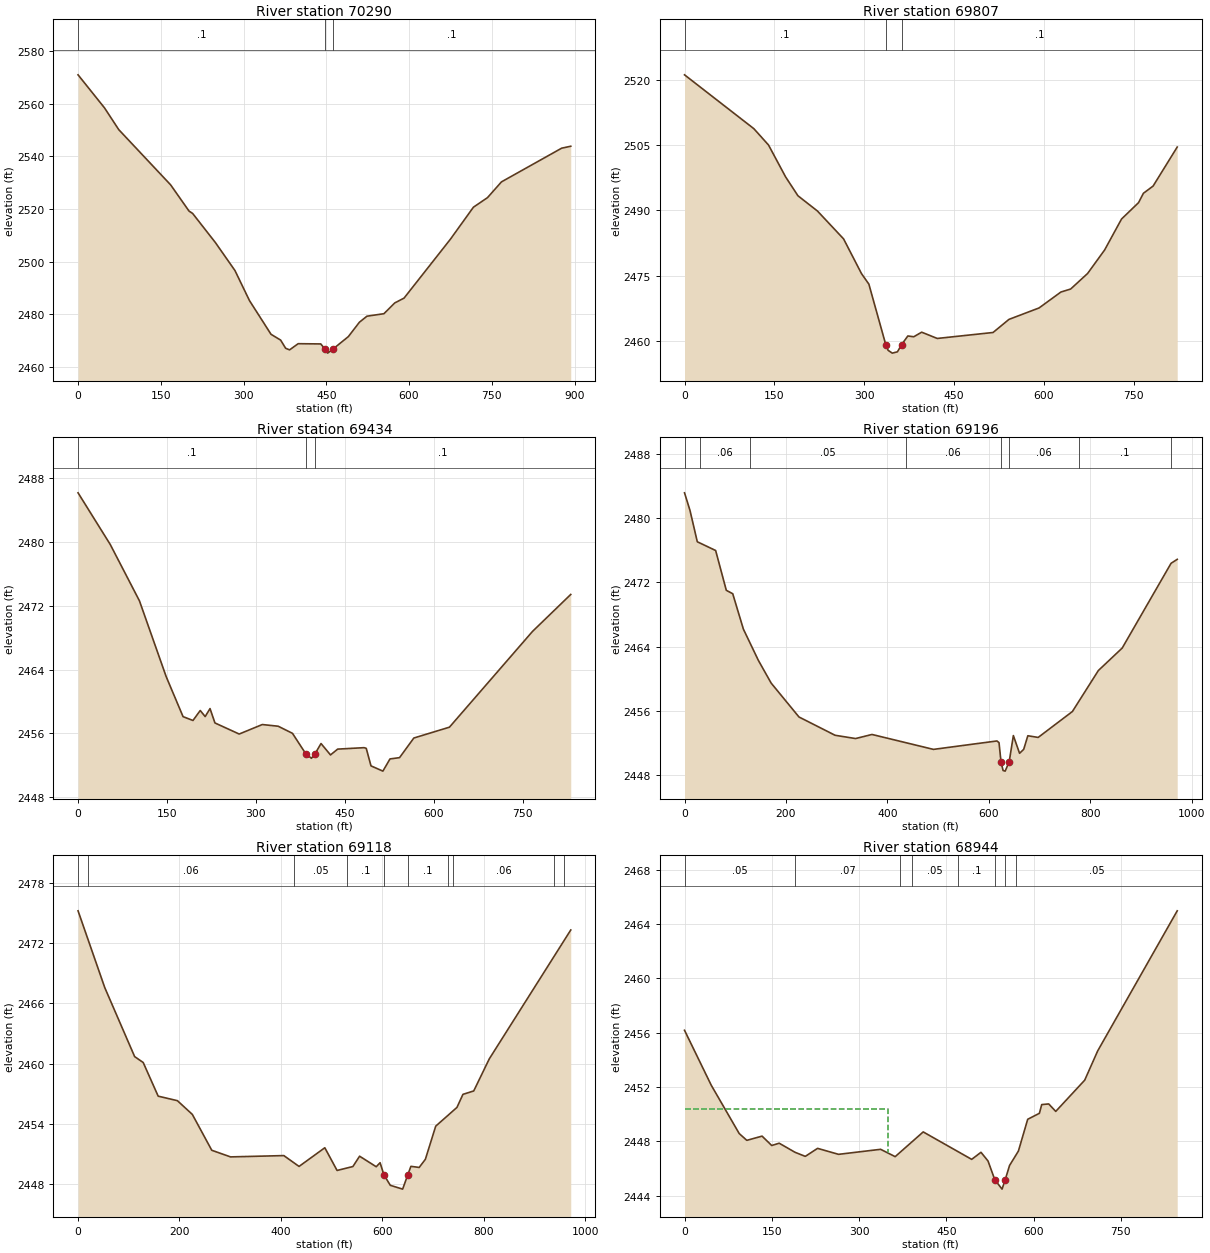
Type RM Length L Ch R = 1 ,70290   ,483.6,483.1,481.9
XS GIS Cut Line= 4
 2259086.9257519675422.3124852732259369.93072475675652.195516331
2259479.84174295675711.9200913072259863.82605383675835.467312851
#Sta/Elev= 30
       0 2570.97      48 2558.41    73.8 2550.16   167.9 2529.18   201.2 2519.24
   207.7 2518.35     249 2507.28   284.4 2496.68   310.8 2485.24   349.8 2472.47
   367.2 2470.27   376.3 2467.16   383.4 2466.55     399  2468.9     440 2468.81
  447.052466.985   452.5 2465.32   462.8 2466.98     490  2471.6     510 2477.05
   523.7 2479.34   554.5 2480.29   574.1 2484.38   590.9  2486.2   674.9 2508.55
   716.7 2520.72   742.2 2524.35   767.5 2530.33   876.6 2543.12   893.1 2543.86
#Mann= 3 ,-1,0
       0      .1       0  447.05    .045       0   462.8      .1       0
Bank Sta=447.05,462.8
XS Rating Curve= 0 ,0
Exp/Cntr=0.3,0.1

Type RM Length L Ch R = 1 ,69807   ,364.1,372.9,377
XS GIS Cut Line= 4
2259038.77816376675711.8845520012259106.41087972676033.202218164
 2259167.5050431676072.8332620852259584.01595356676139.029207948
#Sta/Elev= 30
       0 2521.14   115.8 2508.77   140.3 2505.02   168.9 2497.68   189.4 2493.37
   222.1 2489.85   265.7 2483.45   295.6 2475.48   307.9 2473.07   336.12459.178
     340 2457.87     347 2457.22   355.6 2457.52  362.63 2459.18     373 2461.16
   382.9 2460.98   396.1 2462.03   422.1 2460.59   515.3 2461.96   541.9 2464.97
   592.2  2467.6   628.7 2471.26   644.9 2471.94   673.2 2475.51   701.6  2480.9
   729.9 2488.02   758.3 2491.78   766.4 2493.93   782.6 2495.59   822.9 2504.55
#Mann= 3 ,-1,0
       0      .1       0   336.1    .045       0  362.63      .1       0
Bank Sta=336.1,362.63
XS Rating Curve= 0 ,0
Exp/Cntr=0.3,0.1

Type RM Length L Ch R = 1 ,69434   ,237.2,238,237.8
XS GIS Cut Line= 4
2259000.57890078675968.3065726842258923.54148538676299.432305544
2258949.22062385676596.7696983172259042.47644249676765.711398755
#Sta/Elev= 30
       0 2486.16    54.3 2479.69   103.6 2472.62   148.7 2463.12   177.2  2458.1
   193.9 2457.62   206.2 2458.87   214.5 2458.11   222.7 2459.11     231 2457.31
   271.9 2455.92   310.9 2457.11   337.7  2456.9   361.8 2456.01  384.222453.451
   393.8 2452.88  399.862453.436     410 2454.73     426  2453.3   438.1 2454.03
   482.6 2454.21   486.3 2454.13   494.3 2451.93   514.4 2451.27   526.4  2452.8
   542.5 2452.96   566.6 2455.42   626.7 2456.78   766.8 2468.78   831.4 2473.42
#Mann= 3 ,-1,0
       0      .1       0  384.22    .045       0  399.86      .1       0
Bank Sta=384.22,399.86
XS Rating Curve= 0 ,0
Exp/Cntr(USF)=0,0
Exp/Cntr=0.3,0.1

Type RM Length L Ch R = 1 ,69196   ,83.4,78.4,78
XS GIS Cut Line= 6
2258809.72207062675878.8915998342258719.55377149676152.002627976
2258731.22290471676229.3822820452258769.76410754 676502.38246872
2258786.46529543676587.8154683142258905.17446198676799.824138687
#Sta/Elev= 30
       0 2483.16    10.8 2480.97    25.2 2477.06    61.4 2475.97    82.4 2471.01
    95.1 2470.58   116.1 2466.17   145.6 2462.28   170.9 2459.44   225.7 2455.22
   296.9 2452.94   337.3 2452.53   369.7 2453.04   490.9 2451.18   616.1 2452.23
   620.2 2452.02  624.092449.637   628.2 2448.55   632.3 2448.47  640.242449.637
   648.5  2452.9   660.7 2450.69   668.9 2451.19     677 2452.88   697.4 2452.67
   764.9  2455.9   816.1 2461.01   863.1 2463.81   959.4 2474.37   971.6 2474.87
#Mann= 8 ,-1,0
       0      .1       0      30     .06       0     130     .05       0
  435.87     .06       0  624.09    .045       0  640.24     .06       0
  778.62      .1       0  958.62     .06       0
Bank Sta=624.09,640.24
XS Rating Curve= 0 ,0
Exp/Cntr=0.3,0.1

Type RM Length L Ch R = 1 ,69118   ,163.7,173.6,175.8
XS GIS Cut Line= 6
2258731.21221301675883.1739557032258641.04391388676156.284983845
2258652.71304711676233.6646379152258691.25424993676506.664824589
2258707.95543782676592.0978241842258826.66460437676804.106494556
#Sta/Elev= 30
       0 2475.21    52.7 2467.56   111.6 2460.69   128.5  2460.1     158 2456.75
   195.9  2456.3   225.4 2454.93   263.7 2451.36   300.7  2450.7   405.8 2450.83
   435.8 2449.75   486.6 2451.61   510.8 2449.35     542 2449.74   555.2 2450.77
     588 2449.72   595.6 2450.12  603.212448.904   615.8 2447.87   640.1 2447.49
  650.132448.904   656.4 2449.76   672.7 2449.65   684.9 2450.46   705.3 2453.76
   747.2 2455.63     759 2456.93   780.3 2457.27   810.9 2460.46   971.6  2473.3
#Mann= 10 ,-1,0
       0      .1       0      20     .06       0  425.87     .05       0
  531.29      .1       0  603.21    .045       0  650.13      .1       0
  728.62     .05       0  738.62     .06       0  938.62      .1       0
  958.62     .06       0
Bank Sta=603.21,650.13
XS Rating Curve= 0 ,0
Exp/Cntr=0.3,0.1

Type RM Length L Ch R = 1 ,68944   ,789.9,804.7,811.3
XS GIS Cut Line= 3
2258588.53023246675943.1548845742258499.73447471676145.074004939
 2258550.7814725676769.272847387
#Sta/Elev= 30
       0 2456.17    45.9 2452.13      94 2448.57   107.1 2448.07   133.3 2448.38
   149.9 2447.69   162.7 2447.86     190 2447.19   207.6 2446.89   228.7 2447.48
   264.8 2447.04   337.1 2447.41   362.1 2446.87   410.3 2448.69   493.6 2446.67
   509.6 2447.19   521.7 2446.55  533.282445.178   545.8 2444.48   551.3 2445.18
   558.7 2446.22   573.9 2447.28   589.9 2449.62     610 2450.06     614  2450.7
     626 2450.75   638.1  2450.2   687.9  2452.5   710.3 2454.66   846.9 2464.96
#Mann= 8 ,-1,0
       0     .05       0     190     .07       0  370.58      .1       0
  390.58     .05       0  470.58      .1       0  533.28    .045       0
   551.3      .1       0  570.58     .05       0
#XS Ineff= 2 , 0
          349.31 2450.37
Permanent Ineff=
       F       F
Bank Sta=533.28,551.3
XS Rating Curve= 0 ,0
Exp/Cntr(USF)=0,0
Exp/Cntr=0.3,0.1

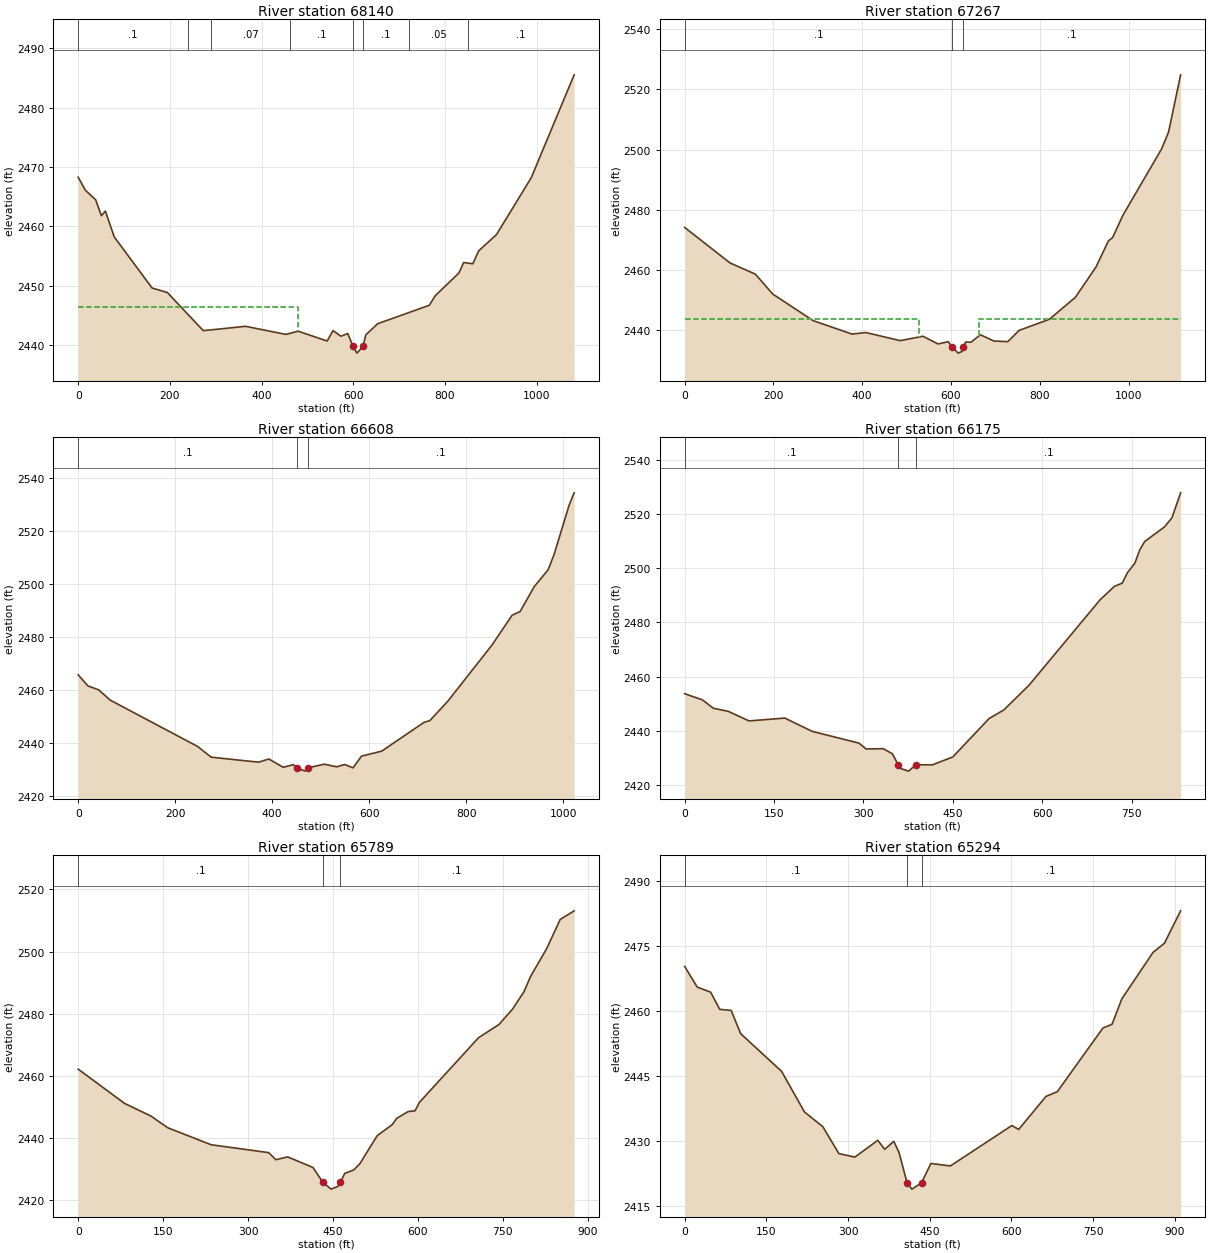
Type RM Length L Ch R = 1 ,68140   ,842.5,872.2,869.5
XS GIS Cut Line= 4
2258477.78946228675708.4071554132258232.70575249676064.429618511
2258077.54196345676271.628055372     2257931.663      676634.346
#Sta/Elev= 30
       0 2468.27    15.5 2466.11    38.1 2464.48    50.6  2461.8    59.3 2462.58
    78.6 2458.24   161.2 2449.64   194.4 2448.89   272.9 2442.47   365.1  2443.2
   453.1 2441.84   479.8 2442.38   543.1 2440.73     556 2442.48   573.2 2441.53
   588.1 2441.99   599.62439.813   608.1 2438.69  621.262439.812   627.4 2441.76
   653.2 2443.63     766 2446.74     779 2448.35   830.7 2452.18   840.9 2453.93
   860.9 2453.72   873.8  2455.9   912.6 2458.63   988.5 2468.21    1082  2485.5
#Mann= 8 ,-1,0
       0      .1       0     240     .05       0     290     .07       0
  462.22      .1       0   599.6    .045       0  621.26      .1       0
  721.08     .05       0  851.08      .1       0
#XS Ineff= 2 , 0
           479.9 2446.46
Permanent Ineff=
       F       F
Bank Sta=599.6,621.26
XS Rating Curve= 0 ,0
Exp/Cntr=0.3,0.1

Type RM Length L Ch R = 1 ,67267   ,649.2,659,648.9
XS GIS Cut Line= 4
2258276.38013599675518.1444216462258023.71653399675771.906111729
2257738.34623436676052.767264939     2257554.026      676360.575
#Sta/Elev= 30
       0 2474.15   102.3 2462.36     159 2458.68   198.7 2452.02   289.4 2443.23
     377 2438.77     408 2439.29   485.4 2436.59   536.7 2438.05   570.9 2435.49
   593.7 2436.23  603.162434.448   616.1 2432.45   624.6 2432.99  628.062434.449
     633 2436.13     645 2436.07   666.1 2438.55   696.4 2436.48   727.9 2436.25
   753.4 2439.99   821.6 2443.68   880.2 2450.96   926.6 2461.01   954.8 2469.71
   964.1 2470.79   987.4 2478.22  1074.2 2500.15    1090 2505.72  1117.3 2524.79
#Mann= 3 ,-1,0
       0      .1       0  603.16    .045       0  628.06      .1       0
#XS Ineff= 2 , 0
          528.38 2443.62  663.18         2443.68
Permanent Ineff=
       F       F
Bank Sta=603.16,628.06
XS Rating Curve= 0 ,0
Exp/Cntr=0.3,0.1

Type RM Length L Ch R = 1 ,66608   ,429.5,433.7,433.5
XS GIS Cut Line= 4
 2257764.6227328675316.5059876142257586.15420037 675540.20002525
2257472.08110344675870.351318969     2257375.482      676245.133
#Sta/Elev= 30
       0 2465.81      20 2461.64    41.8 2460.17    66.3 2456.24   246.5 2438.76
     274 2434.75   371.8 2432.86     393 2434.06   422.6 2430.94   443.8 2431.91
  451.162430.698   467.8 2429.48  473.02  2430.7   507.3  2432.1   532.7 2431.11
   549.6 2431.97   566.5 2430.71   584.1 2435.13   625.8 2437.03   712.7 2447.85
   725.1 2448.56   762.3 2455.93   853.2 2477.07   894.5 2488.29     911 2489.68
     940 2499.04   968.8 2505.45   981.2 2511.24  1012.1 2529.83  1022.5 2534.49
#Mann= 3 ,-1,0
       0      .1       0  451.16    .045       0  473.02      .1       0
Bank Sta=451.16,473.02
XS Rating Curve= 0 ,0
Exp/Cntr=0.3,0.1

Type RM Length L Ch R = 1 ,66175   ,389.4,385.7,372.5
XS GIS Cut Line= 4
 2257414.4240513675303.5459223512257258.03888883675575.547186681
2257175.28677208675717.114686182 2257082.0389487676059.330631059
#Sta/Elev= 30
       0 2453.78    29.6 2451.54      48 2448.44    73.2 2447.29     108 2443.77
     168 2444.81   214.1 2439.92   292.6 2435.58   304.6 2433.44   333.3 2433.54
   348.5  2431.7  358.462427.632     362 2426.28   375.9 2425.28  388.142427.632
   415.7 2427.59     450  2430.5     511 2444.65   535.7 2447.81   578.1 2456.95
   697.5 2488.43   721.4 2493.31   734.4  2494.5   743.1 2498.32   755.6 2501.84
     764 2506.83   772.2 2509.84   805.3 2515.19   817.8 2518.53   832.4 2527.74
#Mann= 3 ,-1,0
       0      .1       0  358.46    .045       0  388.14      .1       0
Bank Sta=358.46,388.14
XS Rating Curve= 0 ,0
Exp/Cntr=0.3,0.1

Type RM Length L Ch R = 1 ,65789   ,496.5,494.5,484
XS GIS Cut Line= 4
2257047.44306056675120.126029608      2256922.97675471.113421268
2256918.90399142675603.1337222522256898.65105518675973.811969046
#Sta/Elev= 30
       0 2462.19    81.8 2451.19   128.4 2447.12   158.1 2443.36   234.5  2437.9
   336.4 2435.36   349.1 2433.08   369.9 2433.99   414.5 2430.59  432.132425.781
   446.5 2423.63   458.5  2424.5  462.632425.778   470.7 2428.69   486.5 2429.79
   497.5 2431.84     528 2440.83   554.6 2444.37   562.6  2446.4   582.6 2448.56
   594.7  2448.8   602.7 2451.56   706.8 2472.28   742.9 2476.54   766.9 2481.49
     787 2487.05     799 2492.07     827 2500.86     851 2510.29   875.7 2513.08
#Mann= 3 ,-1,0
       0      .1       0  432.13    .045       0  462.63      .1       0
Bank Sta=432.13,462.63
XS Rating Curve= 0 ,0
Exp/Cntr=0.3,0.1

Type RM Length L Ch R = 1 ,65294   ,508,499.8,490
XS GIS Cut Line= 4
2256340.31669087675043.9604617122256459.96985225675411.218988595
2256505.28385979675494.8962841982256630.45630687675905.595001132
#Sta/Elev= 30
       0 2470.34    23.1 2465.55    47.6  2464.4    64.4 2460.41    85.4 2460.16
   102.8 2454.79     178 2446.06     220 2436.66   253.7 2433.26   283.1 2427.02
   312.6 2426.22   354.7  2430.1   367.3 2428.02   384.1 2429.86   393.8 2427.23
  408.422420.257   417.4  2418.8  434.982420.258   452.2 2424.74     488 2424.17
   600.9 2433.52   613.4 2432.61   663.6 2440.26   684.3 2441.35   768.2  2456.1
   784.9 2456.95   802.8 2462.83   860.2  2473.6   881.1 2475.71   910.8 2483.21
#Mann= 3 ,-1,0
       0      .1       0  408.42    .045       0  434.98      .1       0
Bank Sta=408.42,434.98
XS Rating Curve= 0 ,0
Exp/Cntr=0.3,0.1