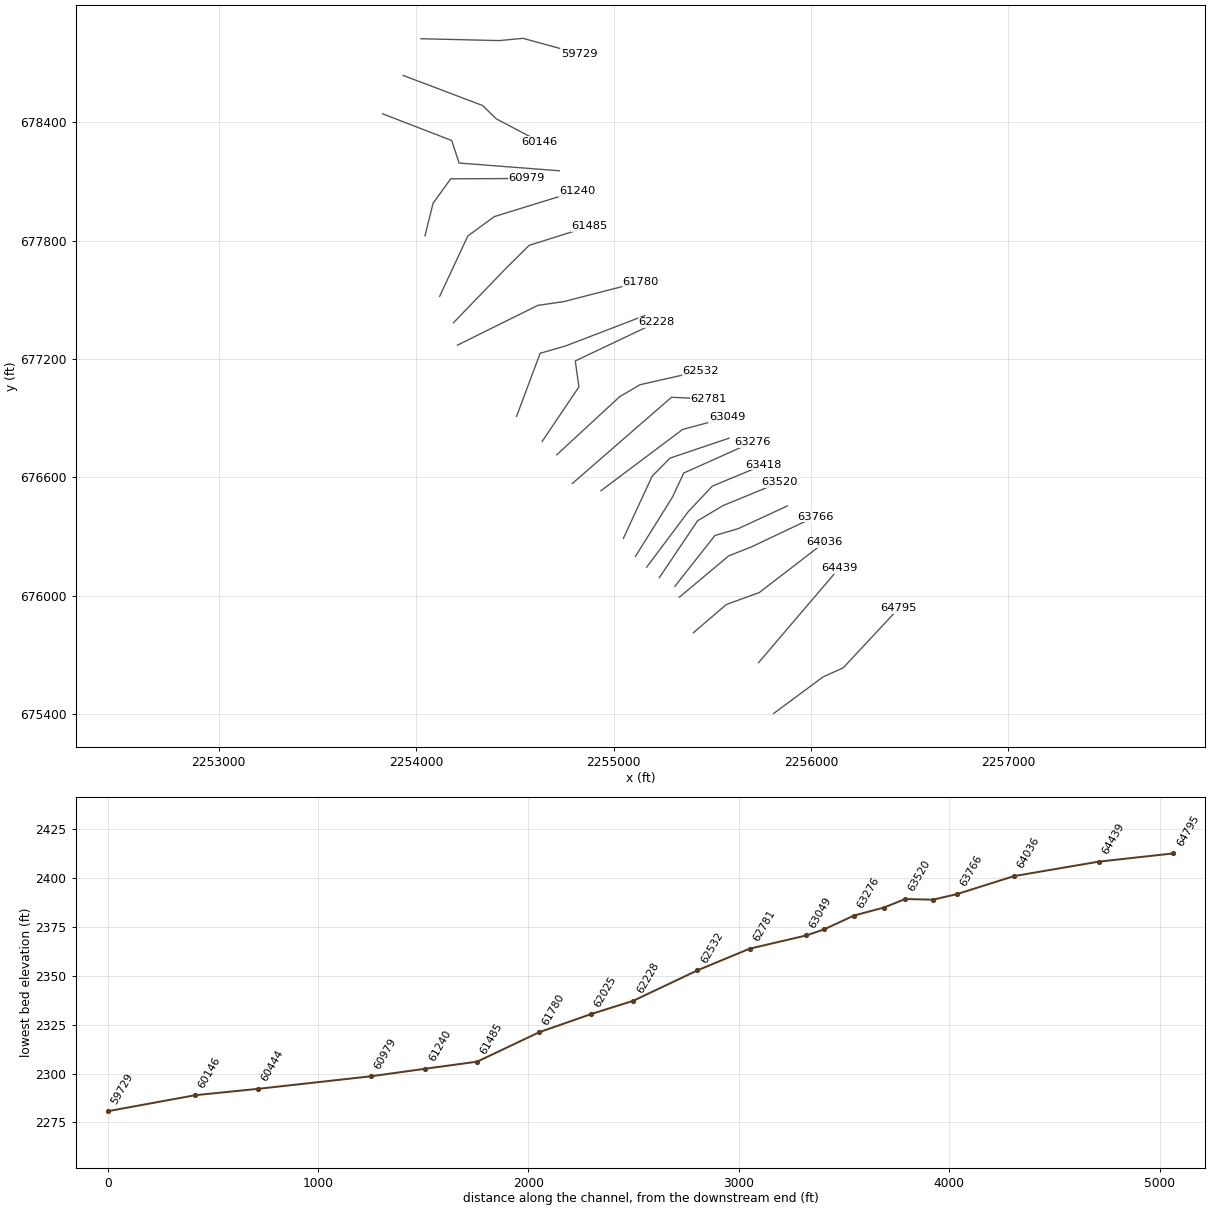
HEC-RAS study ROARCK.prj: ROARCK

--- ROARCK.g01 (geometry) --- (continued)

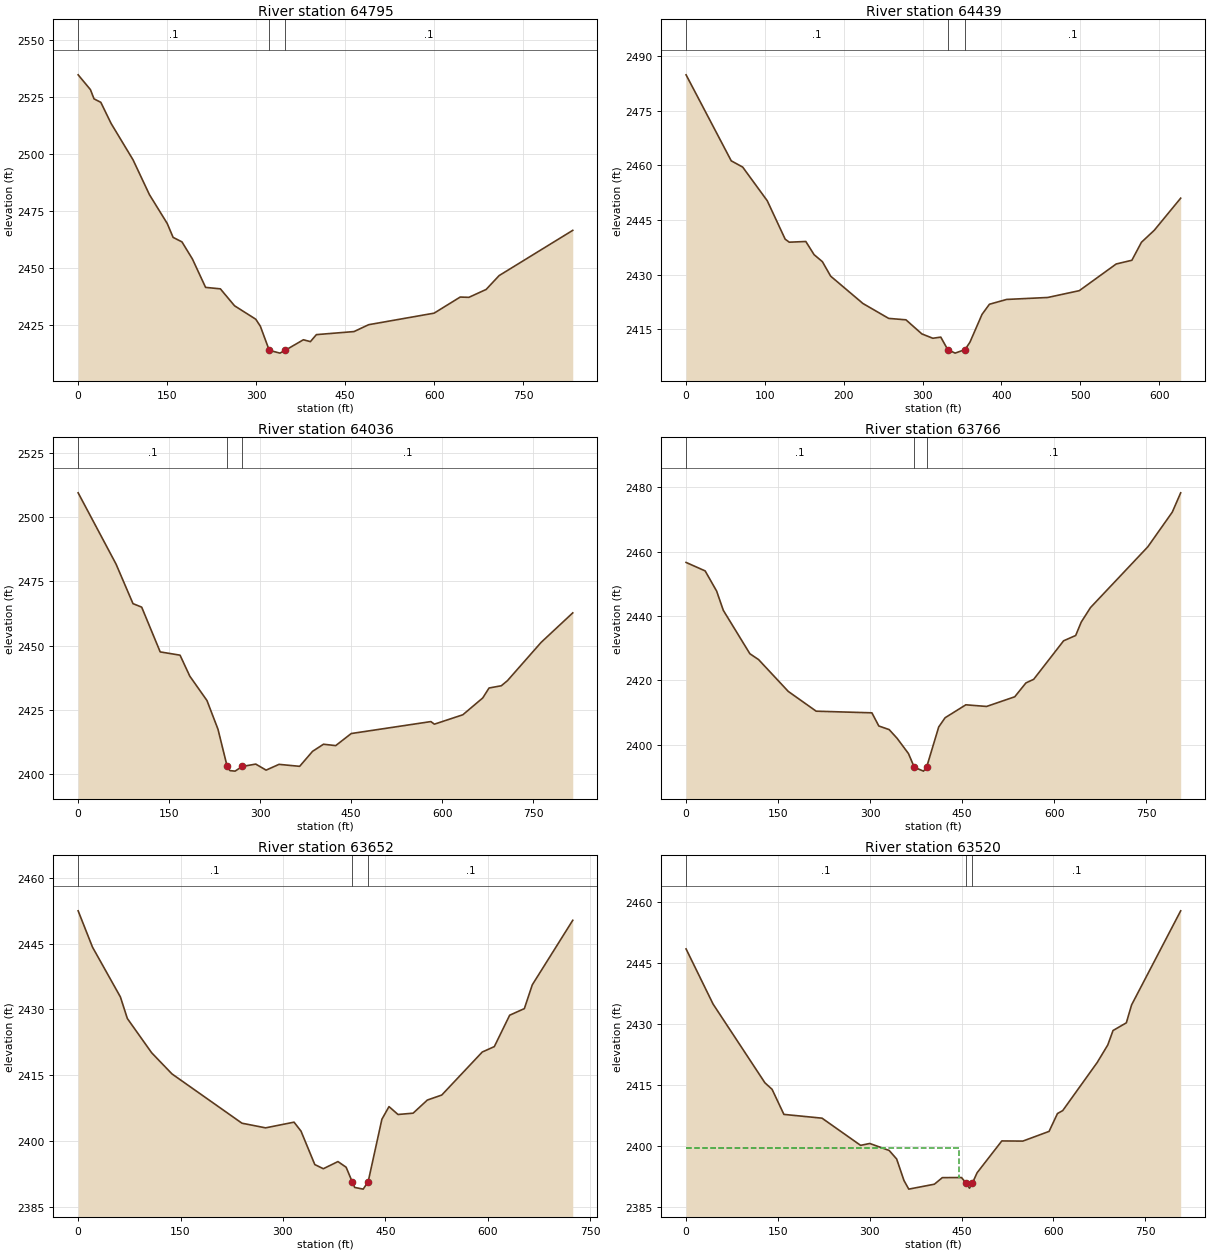
Type RM Length L Ch R = 1 ,64795   ,347.9,355.7,357.1
XS GIS Cut Line= 4
2255811.53581835675404.3361317642256060.85349467675588.897206414
2256163.20843367675635.1355743372256443.50902635675935.939550591
#Sta/Elev= 30
       0 2534.64    20.7 2528.16    26.8  2524.1    38.2 2522.59    55.5 2513.35
    92.6 2497.35   120.2  2482.1   150.1  2469.5   160.1 2463.38     175 2461.41
   192.7 2453.87   214.8 2441.47   239.7 2440.83   263.6 2433.41   299.4 2427.51
   307.1 2424.46  322.11  2413.9   340.1 2412.65   349.1  2413.9   379.7 2418.51
   391.5 2417.69   401.6 2420.76     465  2422.1   489.7 2425.11     600 2430.17
     644 2437.23   658.6  2437.1   687.7 2440.56   709.6 2446.64   833.7 2466.47
#Mann= 3 ,-1,0
       0      .1       0  322.11    .045       0   349.1      .1       0
Bank Sta=322.11,349.1
XS Rating Curve= 0 ,0
Exp/Cntr=0.3,0.1

Type RM Length L Ch R = 1 ,64439   ,408.3,402.6,394.3
XS GIS Cut Line= 2
2255734.61263138675661.5566668042256141.54859971676139.060736667
#Sta/Elev= 30
       0 2484.79    57.3 2461.19    71.8 2459.48     103 2450.23   125.7  2439.7
   130.9 2438.87   151.9 2439.06   162.4 2435.44   172.9 2433.53   183.4 2429.55
   224.4 2422.04     257 2417.96   278.9 2417.57   299.1  2413.7     313 2412.51
   323.1 2412.82  331.872409.413   341.3 2408.43   353.9 2409.41   360.1 2411.44
   375.4 2419.06   384.8 2421.84   406.6 2423.16   458.8  2423.7   498.8 2425.57
   545.6 2432.89   565.5 2433.91   577.6 2438.84   593.9 2442.14   627.4 2450.95
#Mann= 3 ,-1,0
       0      .1       0  331.87    .045       0   353.9      .1       0
Bank Sta=331.87,353.9
XS Rating Curve= 0 ,0
Exp/Cntr=0.3,0.1

Type RM Length L Ch R = 1 ,64036   ,273.7,270.6,271.7
XS GIS Cut Line= 4
2255404.68423212675813.2613329762255571.39157721675956.026665738
2255737.85071191676016.4671771832256069.45243182 676271.63457686
#Sta/Elev= 30
       0 2509.55    62.5 2481.74    90.4 2466.33   104.7 2464.97   135.2 2447.51
   167.9 2446.24     184 2438.05   212.3 2428.54   230.4 2417.36   245.6 2402.84
   250.1 2401.22   258.6 2401.02  270.492402.848   292.7 2403.76   309.7 2401.41
     331 2403.66     365 2402.89   386.3 2408.75   404.3 2411.51   424.4 2410.97
     450 2415.68   581.2 2420.34     587 2419.33   633.9    2423   666.7 2429.56
   677.1 2433.44   697.3 2434.31   707.4  2436.3   762.9 2451.23     815 2462.73
#Mann= 3 ,-1,0
       0      .1       0   245.6    .045       0  270.49      .1       0
Bank Sta=245.6,270.49
XS Rating Curve= 0 ,0
Exp/Cntr(USF)=0,0
Exp/Cntr=0.3,0.1

Type RM Length L Ch R = 1 ,63766   ,115.1,114.1,113
XS GIS Cut Line= 4
2255333.63117765675993.2249232872255583.10426508676202.231904038
 2255699.3724692676248.4387905312256020.62798923676400.622955587
#Sta/Elev= 30
       0 2456.61    31.1 2453.98    49.8 2447.71    60.7 2441.73     104 2428.26
   118.1 2426.46   166.5 2416.57     212 2410.43   302.8 2409.92   314.1 2405.83
   330.9 2404.72   343.8 2402.03   362.4 2397.27  371.952392.999   386.9 2391.82
  391.89    2393   411.7 2405.53   422.1 2408.39   455.9 2412.41   489.7  2411.9
   535.6  2414.9   553.8  2419.2   566.5 2420.33   615.2 2432.28   634.9 2433.93
   643.9 2438.08     659 2442.59   752.4 2461.45   792.3 2472.22     806 2478.22
#Mann= 3 ,-1,0
       0      .1       0  371.95    .045       0  391.89      .1       0
Bank Sta=371.95,391.89
XS Rating Curve= 0 ,0
Exp/Cntr=0.3,0.1

Type RM Length L Ch R = 1 ,63652   ,128.8,132,135.2
XS GIS Cut Line= 4
2255311.17432814676048.5208799222255513.35132112676305.675827132
2255631.28790035676340.2587338252255880.46217679676455.535089471
#Sta/Elev= 30
       0 2452.51      21 2444.23    61.9 2432.85    72.1 2427.92   107.7  2420.1
   137.5 2415.27     240 2404.02   274.6 2402.96   316.3 2404.26   326.5 2402.21
   346.7 2394.58   359.2 2393.63   380.6 2395.26   392.6 2393.97  401.382390.691
   405.1 2389.36   417.6 2388.97   424.9 2390.68     445 2404.93   455.4 2407.81
   468.6 2406.01   490.7 2406.31   511.6 2409.31   532.7 2410.45     592 2420.27
   609.7 2421.51   632.2 2428.68   653.7 2430.18   665.3 2435.61   724.6 2450.35
#Mann= 3 ,-1,0
       0      .1       0  401.38    .045       0   424.9      .1       0
Bank Sta=401.38,424.9
XS Rating Curve= 0 ,0
Exp/Cntr(USF)=0,0
Exp/Cntr=0.3,0.1

Type RM Length L Ch R = 1 ,63520   ,99.3,101.2,102.6
XS GIS Cut Line= 4
2255232.35866295 676092.537857882255425.84933366676380.604686024
2255554.26466669676456.9597489052255842.33149483676575.830699073
#Sta/Elev= 30
       0 2448.52    44.1 2434.93   128.8 2415.52   140.5 2413.91   159.8 2407.73
   222.1  2406.8   285.1  2400.1   300.1 2400.56   331.8 2398.84     344 2396.74
     356 2391.42   363.8 2389.31   405.6 2390.52   418.6 2392.14   449.9 2392.17
  457.722390.752     463 2389.53  467.642390.768   475.4 2393.34   515.8 2401.19
   550.1 2401.15     593 2403.54   606.7 2407.94   615.3 2408.67   671.6 2420.52
   688.9 2424.85   697.5 2428.41   719.2  2430.3   727.8 2434.72     808 2457.91
#Mann= 3 ,-1,0
       0      .1       0  457.72    .045       0  467.64      .1       0
#XS Ineff= 2 , 0
          445.97 2399.44
Permanent Ineff=
       F       F
Bank Sta=457.72,467.64
XS Rating Curve= 0 ,0
Exp/Cntr(USF)=0,0
Exp/Cntr=0.3,0.1

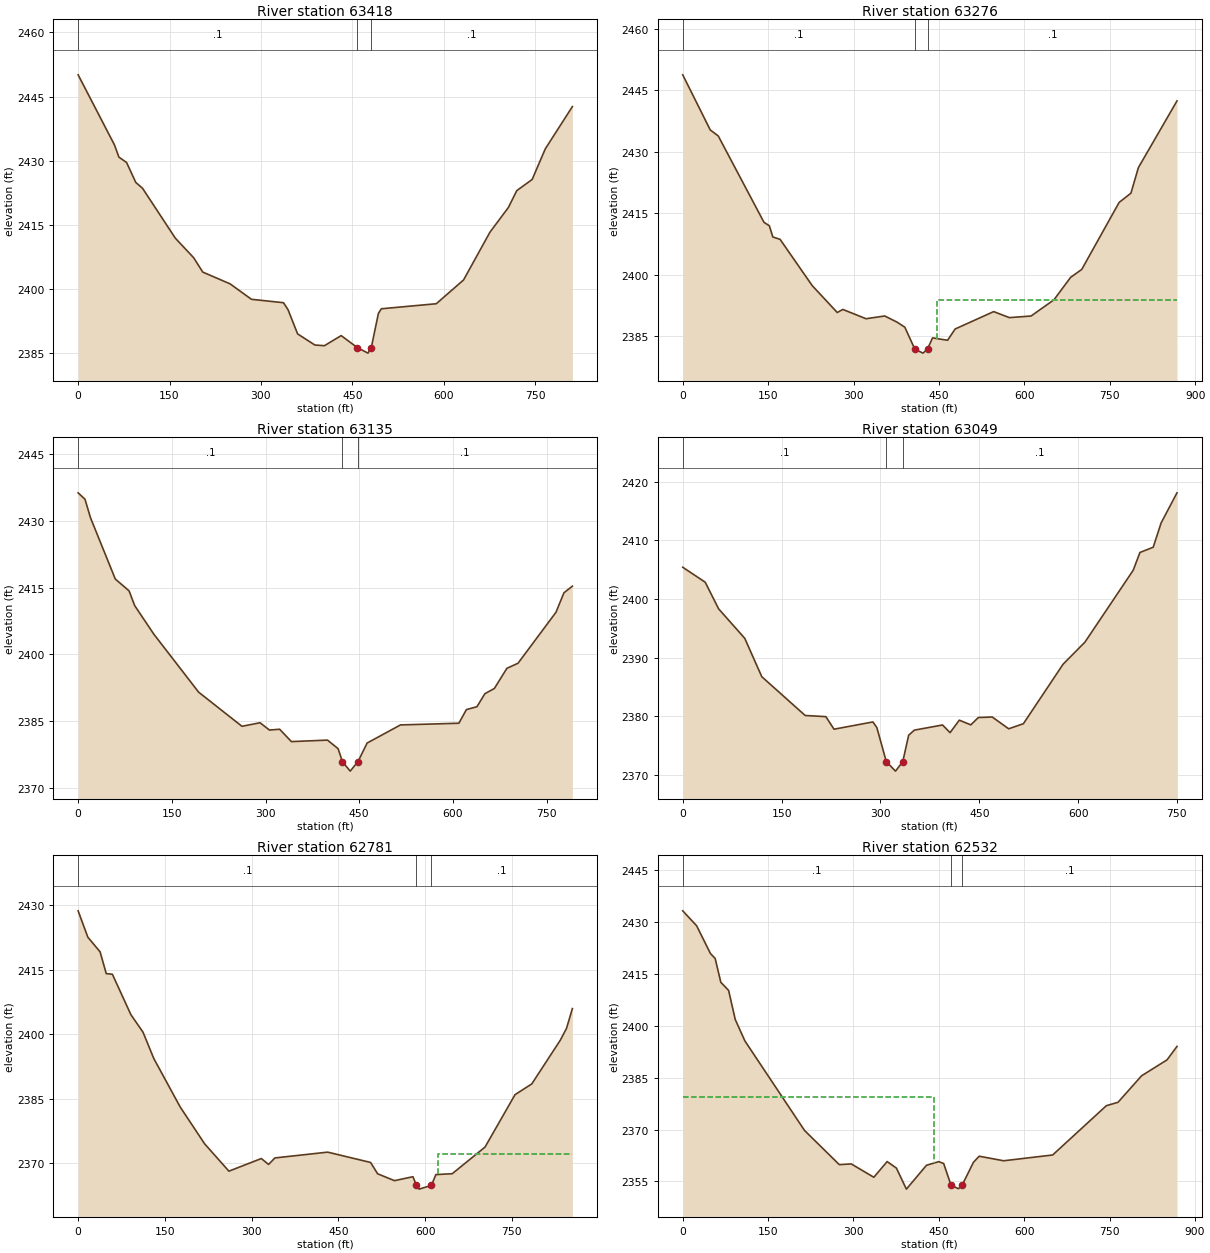
Type RM Length L Ch R = 1 ,63418   ,138.9,142.9,145.9
XS GIS Cut Line= 4
2255167.98916199676145.4336935232255378.34469584676426.332782968
2255500.51711097676555.9948678612255761.21902297676664.177293929
#Sta/Elev= 30
       0 2450.08    59.6 2433.69      67 2430.81    79.6 2429.55    94.6  2424.9
   105.7 2423.53   159.6 2411.84   189.6 2407.28   204.6 2403.91   249.5 2401.15
   284.5 2397.54   337.1 2396.74   344.5 2395.12   360.3 2389.44   388.6 2386.84
   404.3 2386.68   431.8 2389.04  458.34 2386.23   475.8 2384.94   481.2 2386.23
   492.9 2394.23   497.7 2395.32   587.9  2396.5   632.7 2402.07     676 2413.25
   706.3 2419.04     720 2422.97   745.3 2425.59   766.9 2432.77   811.3 2442.64
#Mann= 3 ,-1,0
       0      .1       0  458.34    .045       0   481.2      .1       0
Bank Sta=458.34,481.2
XS Rating Curve= 0 ,0
Exp/Cntr(USF)=0,0
Exp/Cntr=0.3,0.1

Type RM Length L Ch R = 1 ,63276   ,141.7,140.8,134.3
XS GIS Cut Line= 4
2255111.24903006676200.1695689172255298.47684541676500.006979471
2255355.59111488676622.2801004552255702.03875439676777.631370954
#Sta/Elev= 30
       0 2448.79    48.3 2435.34    62.4 2433.86   142.7 2412.77   152.1 2411.93
   158.2  2409.2     171 2408.61   227.5  2397.3   271.4 2390.75   281.2  2391.5
   321.9 2389.23   354.8  2389.9   376.9 2388.36   390.1 2387.15  407.622381.815
   421.9 2380.83  429.912381.814   438.7 2384.55   465.2 2383.97   478.4 2386.72
   546.1 2390.97   573.7  2389.5   611.8 2389.89     652 2393.85   681.3 2399.34
   700.8 2401.27   766.5 2417.63   787.2 2419.89   800.3 2426.13   868.1 2442.42
#Mann= 3 ,-1,0
       0      .1       0  407.62    .045       0  429.91      .1       0
#XS Ineff= 2 , 0
                          446.21         2393.77
Permanent Ineff=
       F       F
Bank Sta=407.62,429.91
XS Rating Curve= 0 ,0
Exp/Cntr=0.3,0.1

Type RM Length L Ch R = 1 ,63135   ,87.4,85.7,83.8
XS GIS Cut Line= 4
2255049.93799157676291.1882569632255195.75765512676606.474015995
2255286.40231085676698.1039397132255584.93851393676798.601275404
#Sta/Elev= 30
       0 2436.31      11 2434.86    19.8 2430.71    59.5 2416.95    81.6 2414.28
    90.6 2410.96   121.2 2404.56     193 2391.52   262.3 2383.86   291.2 2384.66
   306.3 2383.02   322.6  2383.2   341.5 2380.42   399.2 2380.76   416.2 2378.84
   423.1 2375.93   435.6 2373.79  448.092375.944   462.7  2380.1   516.1 2384.17
   609.6 2384.55   621.6 2387.61   638.5 2388.26   651.2 2391.18   666.4 2392.36
   686.5 2396.89   704.3 2398.03   765.1 2409.49   777.8 2413.86   791.3 2415.34
#Mann= 3 ,-1,0
       0      .1       0   423.1    .045       0  448.09      .1       0
Bank Sta=423.1,448.09
XS Rating Curve= 0 ,0
Exp/Cntr(USF)=0,0
Exp/Cntr=0.3,0.1

Type RM Length L Ch R = 1 ,63049   ,275,268.4,276.5
XS GIS Cut Line= 3
2254936.57750506676532.7015280122255349.97625123676843.149621174
2255575.03116709676903.802719067
#Sta/Elev= 30
       0 2405.42    34.1 2402.87    54.5 2398.32    94.1  2393.3     120 2386.75
   185.8 2380.14   217.2 2379.94   229.6  2377.8   288.6 2379.04   294.6 2378.08
  308.942372.268   322.9 2370.65   333.9 2372.26   342.9 2376.78   351.5 2377.64
   394.3 2378.52   405.7 2377.21   419.7 2379.34   437.2 2378.54   448.6 2379.79
   469.7 2379.88   494.7 2377.87     517 2378.74   577.3 2388.89   610.4 2392.65
   683.6  2404.9   693.9 2407.94     714 2408.83     726 2412.97   750.1 2418.11
#Mann= 3 ,-1,0
       0      .1       0  308.94    .045       0   333.9      .1       0
Bank Sta=308.94,333.9
XS Rating Curve= 0 ,0
Exp/Cntr(USF)=0,0
Exp/Cntr=0.3,0.1

Type RM Length L Ch R = 1 ,62781   ,252.4,248.8,249.3
XS GIS Cut Line= 3
2254791.49624961676569.2891278262255293.65260868677006.244589621
2255482.33677729676997.552171812
#Sta/Elev= 30
       0  2428.7    16.8 2422.56      38 2419.15    48.6 2414.09    59.2 2413.94
    91.2 2404.54   112.2 2400.45   130.8 2394.33   176.5 2383.03   218.7 2374.47
   260.7  2368.1   316.7 2371.04   329.3 2369.67   340.2 2371.18   431.4 2372.53
   505.6 2370.13   517.8 2367.49     547 2365.89   578.8 2366.81  584.952364.792
   589.5 2363.92   610.7 2364.79   618.5  2367.3   646.8 2367.51   703.5 2373.71
   755.3  2385.9   784.3 2388.41   833.7  2398.6   844.4 2401.35   854.5 2405.94
#Mann= 3 ,-1,0
       0      .1       0  584.95    .045       0   610.7      .1       0
#XS Ineff= 2 , 0
                          622.22          2372.2
Permanent Ineff=
       F       F
Bank Sta=584.95,610.7
XS Rating Curve= 0 ,0
Exp/Cntr(USF)=0,0
Exp/Cntr=0.3,0.1

Type RM Length L Ch R = 1 ,62532   ,290.7,304.2,317.7
XS GIS Cut Line= 4
2254712.38824898676714.4728889032255031.43480747677009.326343435
2255134.25549931677069.8091033392255441.20550582677139.364277229
#Sta/Elev= 30
       0 2433.18    24.4 2428.87    48.7 2420.85      57 2419.42    66.9 2412.54
    80.6 2410.19    92.3 2401.78   109.3 2395.58   214.1 2369.72   275.1 2359.87
   296.1 2360.07   335.8 2356.22   359.2 2360.75   375.5 2358.86     393 2352.79
   428.3 2359.68   449.9 2360.73   458.5 2360.19  471.542353.884   484.5 2352.92
  490.75 2353.86   510.8 2360.53   520.9  2362.3   563.9 2360.98     650 2362.65
   744.4 2376.89   764.9 2377.88   806.3 2385.53     851 2390.13   868.5 2394.01
#Mann= 3 ,-1,0
       0      .1       0  471.54    .045       0  490.75      .1       0
#XS Ineff= 2 , 0
          441.88 2379.35
Permanent Ineff=
       F       F
Bank Sta=471.54,490.75
XS Rating Curve= 0 ,0
Exp/Cntr(USF)=0,0
Exp/Cntr=0.3,0.1

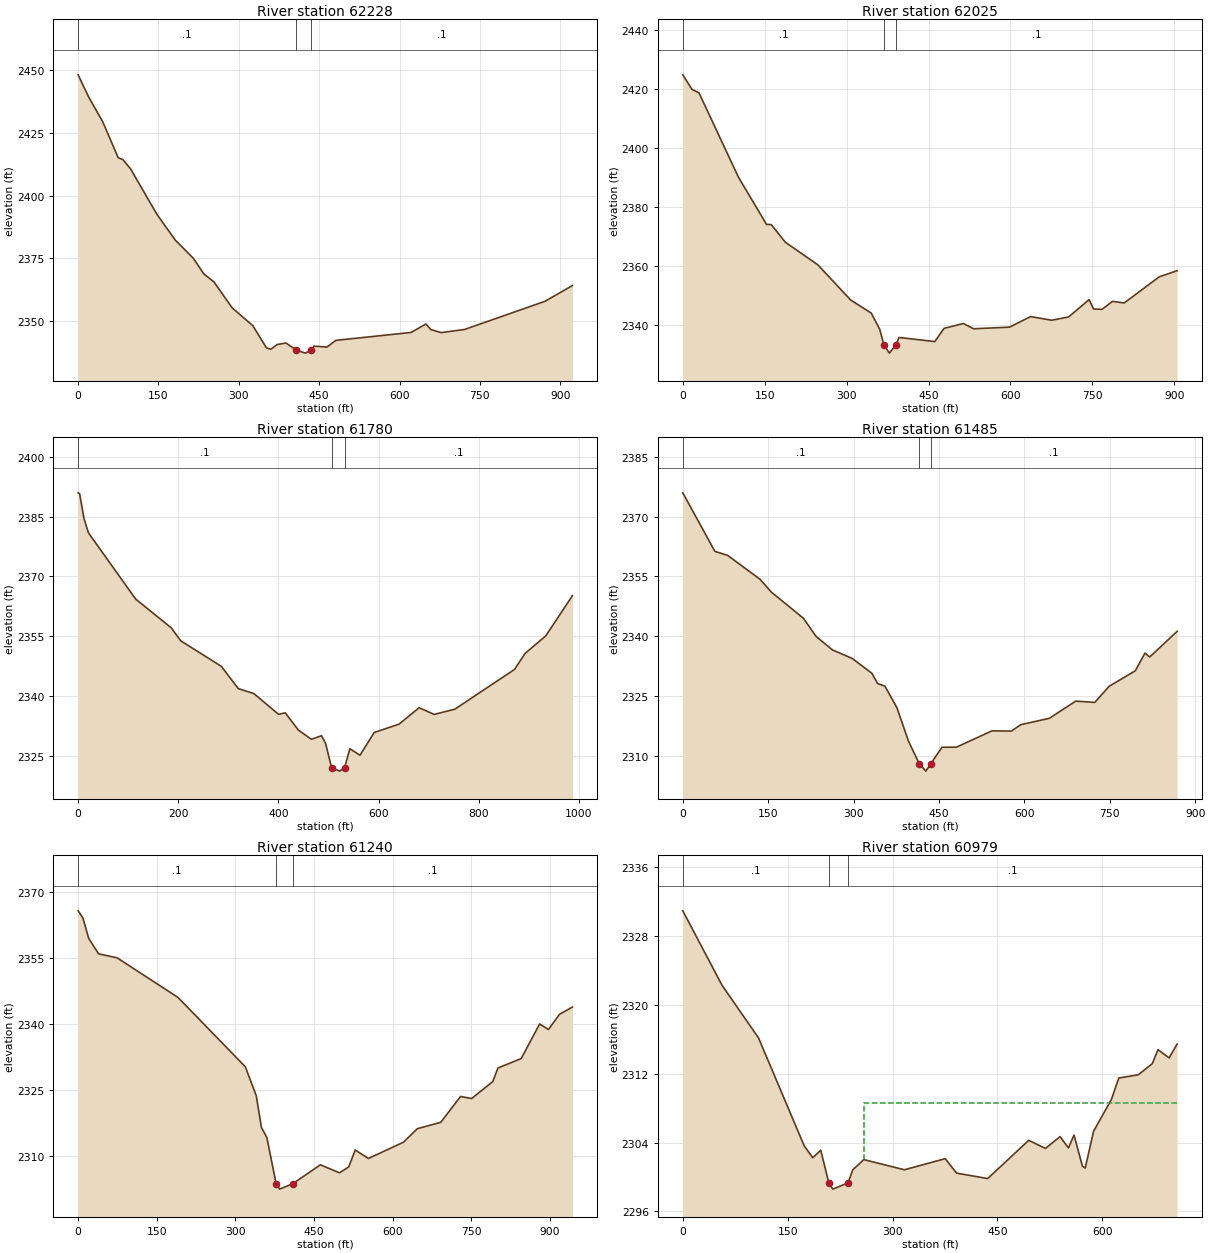
Type RM Length L Ch R = 1 ,62228   ,219.7,202.6,184.4
XS GIS Cut Line= 4
2254638.86298789676782.6890780592254824.78844131  677058.8295651
2254806.37538004677190.3171251992255219.14405114677386.311858687
#Sta/Elev= 30
       0 2448.11      20 2439.14      46 2429.37    74.8 2415.09    83.4 2414.36
    97.8 2410.69   146.8 2392.63   181.4 2382.25   215.2 2374.99   234.5 2368.82
   253.5 2365.62   287.5 2355.29   326.1 2348.18   351.4 2339.37   359.5 2338.78
   371.6 2340.68   387.8 2341.29   407.32338.453   424.1 2337.25  434.532338.454
   440.3 2340.04   464.5 2339.67   480.9 2342.33   621.5 2345.49   649.2 2348.86
   658.3 2346.65   677.5 2345.42   721.4 2346.68   871.5 2357.91   922.6 2364.17
#Mann= 3 ,-1,0
       0      .1       0   407.3    .045       0  434.53      .1       0
Bank Sta=407.3,434.53
XS Rating Curve= 0 ,0
Exp/Cntr=0.3,0.1

Type RM Length L Ch R = 1 ,62025   ,245.4,244.8,243.3
XS GIS Cut Line= 4
2254509.06615738676909.4316588882254628.37329682677228.937581597
2254759.61099401 677267.067453082255158.64453279677420.473680209
#Sta/Elev= 30
       0 2424.74    16.8 2419.81    29.6 2418.65   101.7  2390.1   153.4    2374
     162 2373.97   187.6 2368.01   247.4 2360.31   307.2 2348.42     345 2343.97
   360.5 2338.53  368.262333.203   378.3 2330.38  390.292333.191     396 2335.69
   461.6  2334.3   478.3 2338.77   513.8 2340.42   532.4 2338.64   598.3 2339.19
   636.9 2342.77   675.5 2341.53   706.5 2342.65     744  2348.5   752.2 2345.36
   767.7 2345.22   786.9 2347.94   808.3 2347.39   872.6 2356.27   905.2 2358.31
#Mann= 3 ,-1,0
       0      .1       0  368.26    .045       0  390.29      .1       0
Bank Sta=368.26,390.29
XS Rating Curve= 0 ,0
Exp/Cntr(USF)=0,0
Exp/Cntr=0.3,0.1

Type RM Length L Ch R = 1 ,61780   ,286.2,295.2,302.9
XS GIS Cut Line= 4
2254209.60300404677270.1479609712254616.69363309677471.901769082
2254747.07810863677490.7026537162255135.56502961677590.625966354
#Sta/Elev= 30
       0 2390.94     2.9 2390.76    11.8 2384.44    20.7 2380.89   114.9  2364.3
   185.9 2357.09     205 2353.82   286.1 2347.42   319.8 2341.85   351.1 2340.59
   400.2  2335.4   413.6 2335.77     440 2331.43   465.9 2329.13   486.1 2330.03
   494.2 2328.12  506.132322.023   522.5 2321.15  532.162322.024   542.7 2326.78
   562.9 2325.13   591.3 2330.84   640.9 2332.93     681 2337.05   711.1 2335.37
   752.4 2336.69   871.5 2346.65   892.8 2350.68     934 2355.07   987.2 2365.16
#Mann= 3 ,-1,0
       0      .1       0  506.13    .045       0  532.16      .1       0
Bank Sta=506.13,532.16
XS Rating Curve= 0 ,0
Exp/Cntr=0.3,0.1

Type RM Length L Ch R = 1 ,61485   ,247.7,245.7,242.6
XS GIS Cut Line= 4
2254189.57227893677384.001185851 2254458.2548617677662.437921797
 2254573.2775872677776.2951057952254878.06627612677872.191773363
#Sta/Elev= 30
       0 2375.97    56.4 2361.26    78.6 2360.28   135.6 2354.28   155.4 2351.06
     212 2344.46   234.2  2339.9   262.9 2336.53   297.5 2334.39   332.1 2330.67
   342.1  2328.1   355.1 2327.41   376.1 2322.03   396.5 2313.58   415.7 2307.87
     427 2306.09   435.5 2307.92   455.3 2312.09   480.7  2312.1     543  2316.2
   577.3 2316.15   593.7 2317.75   644.1 2319.36   690.2 2323.67   723.7 2323.35
   748.9 2327.39     795  2331.3   811.8 2335.72   820.2 2334.75   868.3 2341.18
#Mann= 3 ,-1,0
       0      .1       0   415.7    .045       0   435.5      .1       0
Bank Sta=415.7,435.5
XS Rating Curve= 0 ,0
Exp/Cntr(USF)=0,0
Exp/Cntr=0.3,0.1

Type RM Length L Ch R = 1 ,61240   ,255.4,260.6,265
XS GIS Cut Line= 4
2254119.66957081677517.7963758752254262.32828672677823.553971135
2254396.28465601677921.667919527  2254815.905448678051.427841883
#Sta/Elev= 30
       0 2365.68     8.9 2364.13    20.1 2359.44      39 2355.91    74.4    2355
   190.4 2346.02   318.9 2330.26   339.7  2323.7   349.6 2316.47   359.9  2314.2
  377.582303.749   384.3 2302.48  409.842303.749     462 2308.01   498.4 2306.18
   515.9  2307.5   528.5 2311.37   553.6 2309.44   620.6 2313.15   646.9  2316.2
   691.6 2317.65   729.4 2323.53   750.4 2323.05   790.8  2326.9   800.6 2329.98
   845.1 2332.14   880.1 2339.99   896.9 2338.72   917.8 2342.15   942.7 2343.83
#Mann= 3 ,-1,0
       0      .1       0  377.58    .045       0  409.84      .1       0
Bank Sta=377.58,409.84
XS Rating Curve= 0 ,0
Exp/Cntr=0.3,0.1

Type RM Length L Ch R = 1 ,60979   ,557.9,535.1,502
XS GIS Cut Line= 4
2254045.29456469677824.0823873032254086.08465976677989.016249994
2254175.64552069678113.160017611 2254559.6044591678114.933500005
#Sta/Elev= 30
       0 2330.93    56.1 2322.28   108.3 2316.16   173.5 2303.64   185.8 2302.24
   197.3 2303.11   208.8 2299.32   214.5 2298.59  236.232299.312   243.1 2300.84
   258.9 2302.02     317 2300.84   375.3 2302.13   391.5 2300.45     436 2299.82
   494.7 2304.26   518.6 2303.32   539.5 2304.69   551.5 2303.38   559.5 2304.87
   571.5 2301.25   575.5 2301.04   587.5 2305.33   612.8 2308.98   623.5  2311.5
   651.5 2311.88   671.5 2313.18   679.5  2314.8   695.5 2313.84   706.9 2315.44
#Mann= 3 ,-1,0
       0      .1       0   208.8    .045       0  236.23      .1       0
#XS Ineff= 2 , 0
                          259.73         2308.56
Permanent Ineff=
       F       F
Bank Sta=208.8,236.23
XS Rating Curve= 0 ,0
Exp/Cntr(USF)=0,0
Exp/Cntr=0.3,0.1

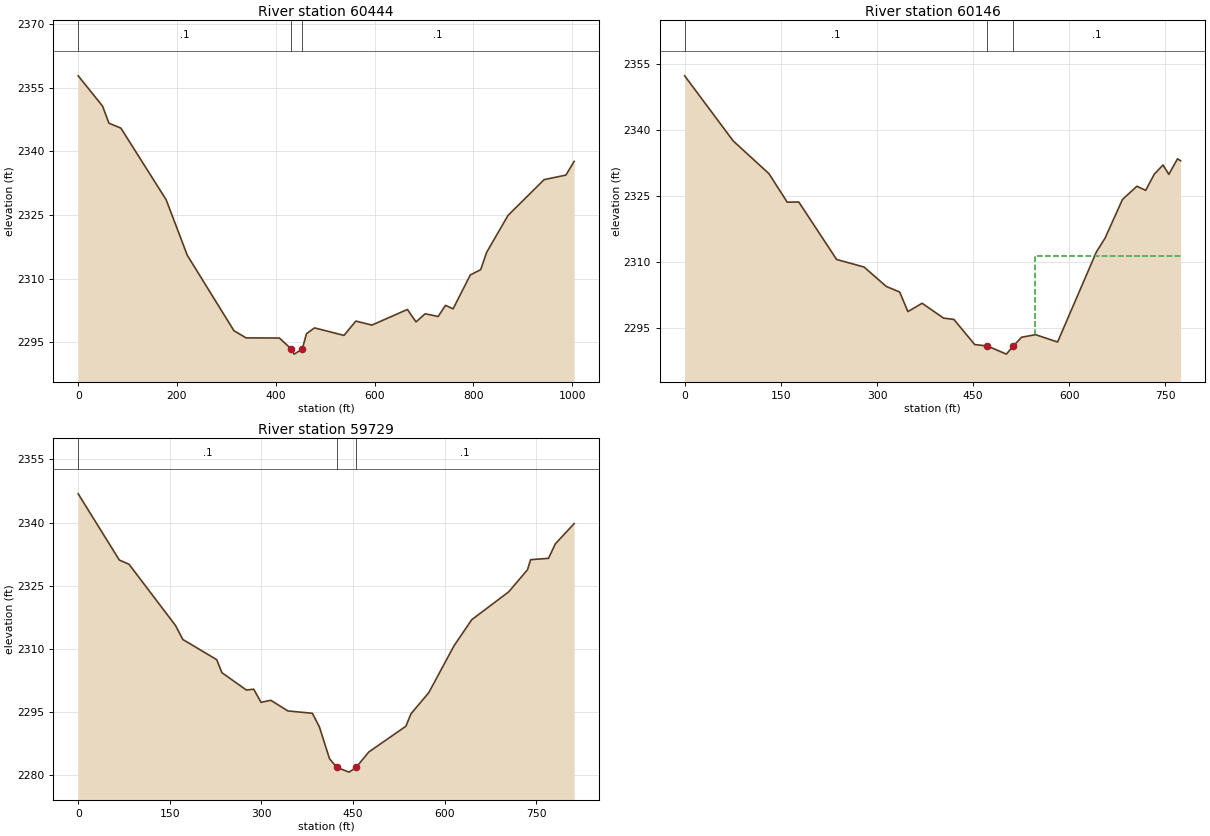
Type RM Length L Ch R = 1 ,60444   ,294.7,298.2,302.9
XS GIS Cut Line= 4
2253830.19632931678442.9095108332254180.54777634678307.238107652
2254218.05692899678193.1145155642254724.82952322678154.009228765
#Sta/Elev= 30
       0 2357.82    49.3 2350.68    62.2 2346.65    86.4 2345.49     178 2328.61
   220.9 2315.49   315.3 2297.71   339.9 2296.02   407.3 2295.99  431.45 2293.39
   437.2 2292.19   453.7 2293.38   462.1    2297   478.4 2298.38   538.1 2296.61
   562.1 2299.98   594.6 2299.04   666.5 2302.72     684 2299.79   702.5 2301.71
   728.7 2301.06   743.6  2303.7     759 2302.87   793.8 2310.85   814.9 2312.11
   826.9 2316.19   870.2  2324.9   943.3 2333.34   987.4 2334.41  1004.1 2337.64
#Mann= 3 ,-1,0
       0      .1       0  431.45    .045       0   453.7      .1       0
Bank Sta=431.45,453.7
XS Rating Curve= 0 ,0
Exp/Cntr(USF)=0,0
Exp/Cntr=0.3,0.1

Type RM Length L Ch R = 1 ,60146   ,390.4,416.4,424.6
XS GIS Cut Line= 4
2253934.55298654678637.1512346382254336.84499097678484.632749873
 2254406.7533022678416.7843699172254624.44997055678302.274304468
#Sta/Elev= 30
       0  2352.3    75.7 2337.48   131.5 2330.02     160 2323.53     178 2323.58
     237 2310.49   279.8 2308.77   314.5 2304.35   335.4 2303.08   348.2 2298.62
   370.4 2300.52   403.8 2297.14     420 2296.84   452.4 2291.12  472.122290.796
   501.8 2288.94  512.632290.797   525.6 2292.79   547.3 2293.37   581.7  2291.7
   642.2  2312.2   655.8 2315.37   682.9 2324.15   705.5 2327.17   719.1 2326.22
   732.6 2329.93   746.2 2332.01   755.2 2329.87   768.8 2333.42   773.6 2332.96
#Mann= 3 ,-1,0
       0      .1       0  472.12    .045       0  512.63      .1       0
#XS Ineff= 2 , 0
                          546.43         2311.36
Permanent Ineff=
       F       F
Bank Sta=472.12,512.63
XS Rating Curve= 0 ,0
Exp/Cntr=0.3,0.1

Type RM Length L Ch R = 1 ,59729   ,230.5,225.7,221.9
XS GIS Cut Line= 4
2254024.89377255678823.0812214392254421.74043857678813.639293003
2254541.80832345678825.0573069582254825.92992183678747.290221439
#Sta/Elev= 30
       0 2346.83    67.3 2331.11    83.3 2330.09   159.3 2315.56   171.3 2312.24
   226.8 2307.44   235.3 2304.35   275.4 2300.23   287.4 2300.43   299.4  2297.3
   315.4 2297.79   343.4 2295.26   383.4 2294.71   394.9  2291.5   411.5 2283.92
  423.492281.842   443.6 2280.73  455.08 2281.84   475.8 2285.51   536.6 2291.63
   544.9 2294.59   573.9 2299.57   615.4 2310.74   644.4 2316.93     705 2323.56
   735.7  2328.8   740.8 2331.19   770.1 2331.51   781.3 2334.96   812.1 2339.75
#Mann= 3 ,-1,0
       0      .1       0  423.49    .045       0  455.08      .1       0
Bank Sta=423.49,455.08
XS Rating Curve= 0 ,0
Exp/Cntr=0.3,0.1