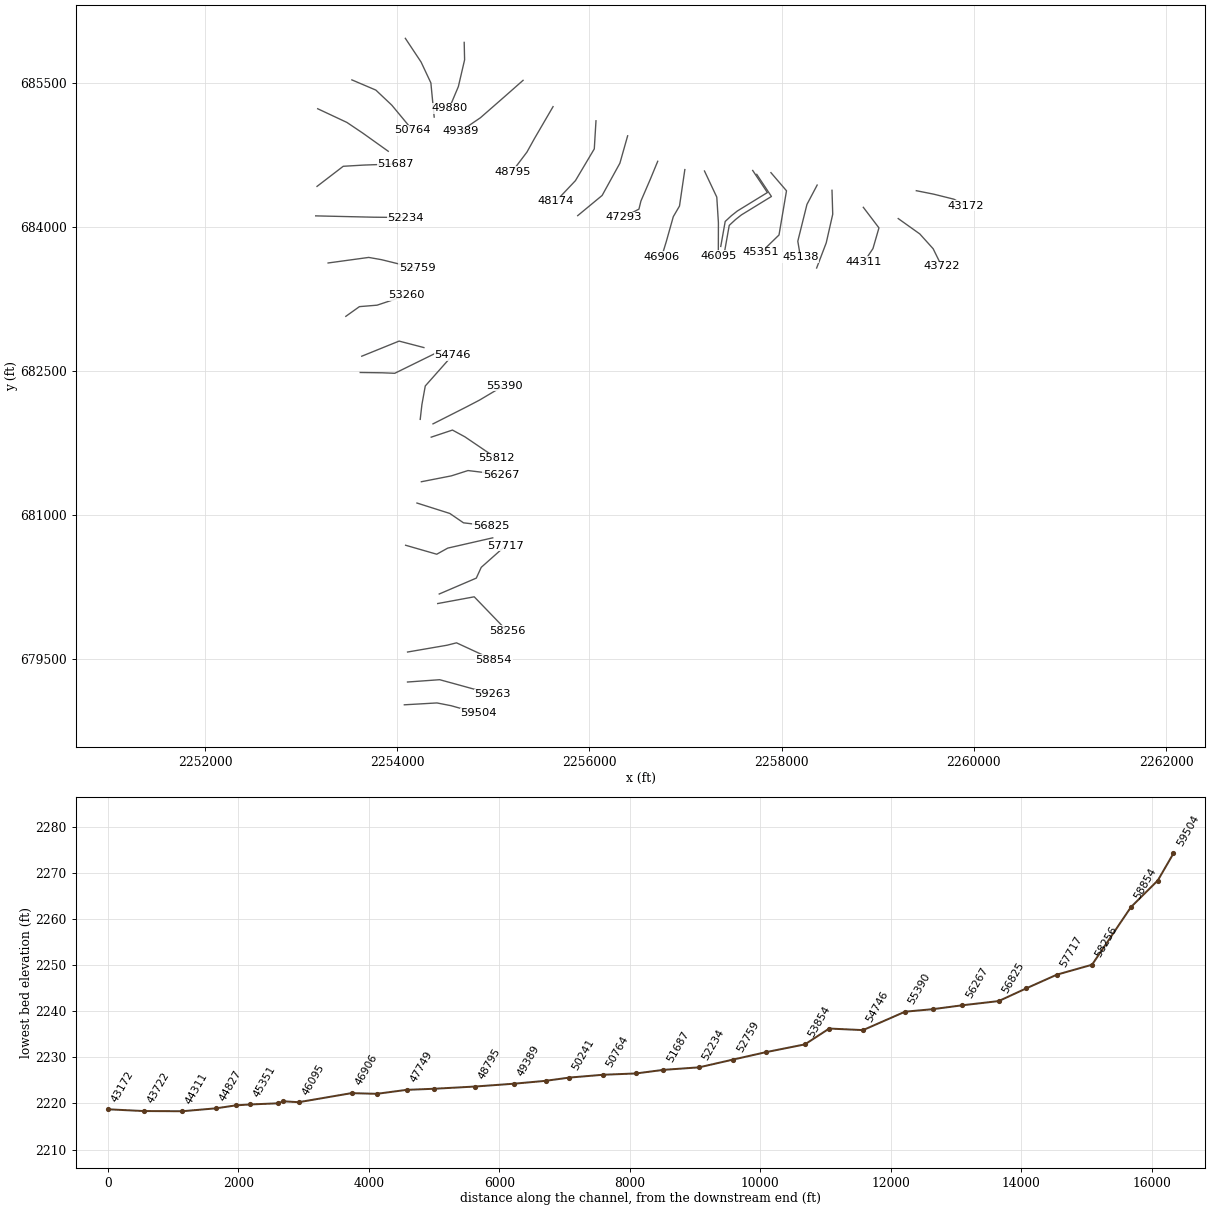
HEC-RAS study ROARCK.prj: ROARCK

--- ROARCK.g01 (geometry) --- (continued)

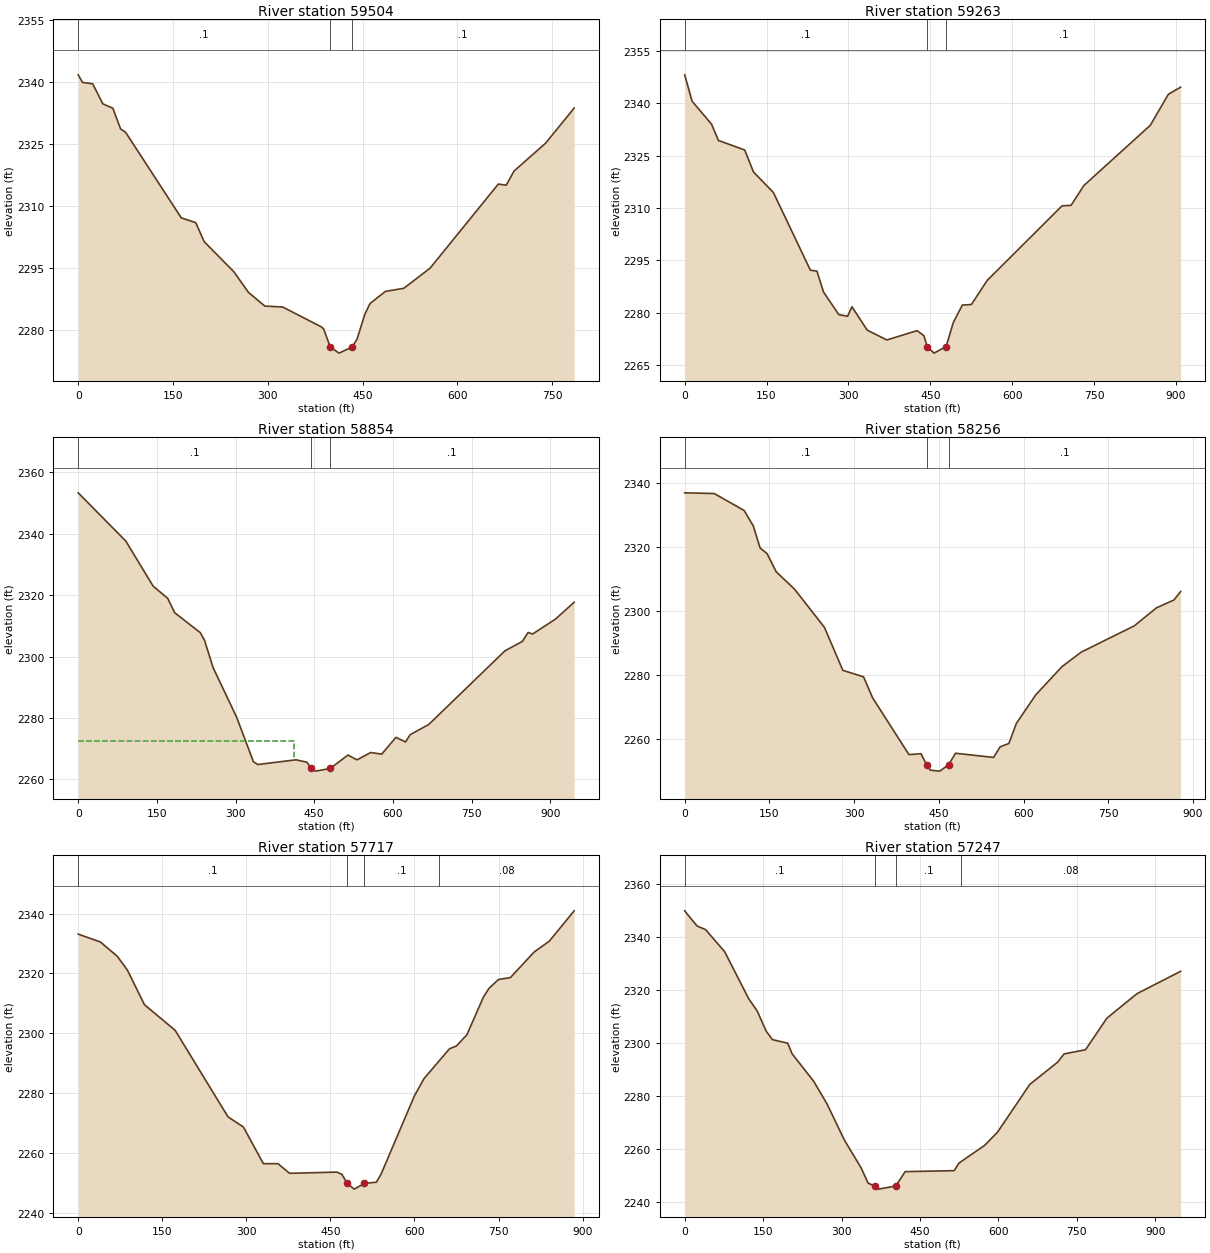
Type RM Length L Ch R = 1 ,59504   ,241.4,240.6,238.8
XS GIS Cut Line= 4
2254073.33356806679027.6801870022254412.71867294679047.202339053
2254560.36108229679018.2830639592254843.67489482678938.476356203
#Sta/Elev= 30
       0 2341.69     6.9 2339.84    22.9 2339.53    38.9 2334.67    54.9 2333.58
      67 2328.59      75 2327.77   163.1 2307.04     186 2305.89   199.2 2301.31
   246.6 2293.93   269.3 2289.01   295.3 2285.67   323.4 2285.46   384.2 2280.68
   388.3 2280.18  398.752275.791   412.7 2274.28   433.7 2275.78   441.3 2277.71
   453.5 2283.69   461.7  2286.3   486.1 2289.24   515.1 2289.98   556.7 2294.85
   664.7 2315.23   677.2 2314.96   689.7  2318.4   739.5 2325.13   784.7 2333.63
#Mann= 3 ,-1,0
       0      .1       0  398.75    .045       0   433.7      .1       0
Bank Sta=398.75,433.7
XS Rating Curve= 0 ,0
Exp/Cntr(USF)=0,0
Exp/Cntr=0.3,0.1

Type RM Length L Ch R = 1 ,59263   ,401.7,408.9,418.9
XS GIS Cut Line= 4
2254106.49498654679265.023905791 2254441.0102262679289.142873878
2254596.44672841679246.6997571952254993.63298654679136.936091671
#Sta/Elev= 30
       0 2348.18    13.7 2340.59    49.2 2334.05    61.8 2329.37     110 2326.62
     126 2320.35   162.6 2314.43   230.3 2292.17   242.3  2291.9   254.3 2285.94
   282.4 2279.42   298.5 2278.97   306.5 2281.68   334.5 2274.97   370.5 2272.17
   425.7 2274.83   438.2 2273.42  444.312270.267   456.7 2268.39  478.952270.264
   492.1 2277.15   508.7 2282.17   525.3 2282.33   554.3 2289.24   691.3 2310.61
   707.9 2310.76   731.6 2316.48   853.1 2333.72   886.3 2342.63   908.6 2344.64
#Mann= 3 ,-1,0
       0      .1       0  444.31    .045       0  478.95      .1       0
Bank Sta=444.31,478.95
XS Rating Curve= 0 ,0
Exp/Cntr=0.3,0.1

Type RM Length L Ch R = 1 ,58854   ,607.8,598.5,566.2
XS GIS Cut Line= 4
2254106.88301203679577.3451733362254516.91393239 679648.01591109
2254616.32042983679673.0603656212255003.90347895679493.924640265
#Sta/Elev= 30
       0 2353.37    90.6 2337.68   142.9 2322.95   170.6 2318.99     184 2314.28
   232.7  2307.8   240.8 2305.33     257 2296.48   302.2 2280.18   334.1 2265.73
   342.3 2264.81   415.3 2266.35   435.9 2265.57  444.722263.522   452.4 2262.66
  480.472263.523   514.3  2267.9   531.6 2266.33   557.6 2268.72   578.7  2268.2
   605.8 2273.67   624.2 2272.18   632.9 2274.54   668.3 2277.85   813.7 2301.88
   846.9 2304.94   857.7 2307.85   866.5 2307.36   910.2 2312.24   945.6  2317.7
#Mann= 3 ,-1,0
       0      .1       0  444.72    .045       0  480.47      .1       0
#XS Ineff= 2 , 0
           411.7 2272.61
Permanent Ineff=
       F       F
Bank Sta=444.72,480.47
XS Rating Curve= 0 ,0
Exp/Cntr=0.3,0.1

Type RM Length L Ch R = 1 ,58256   ,507.6,538.5,568.8
XS GIS Cut Line= 3
2254420.76454418 680082.23760386 2254800.6864163680152.293588109
2255141.93588141679798.176196801
#Sta/Elev= 30
       0 2336.79    52.3 2336.57   105.2  2331.3   121.4 2326.52   133.6  2319.6
   145.8 2317.88   162.1 2312.19   194.6 2306.78   247.5 2294.87   280.1  2281.5
   316.7 2279.47   332.9  2272.9   397.1 2255.25   418.4 2255.54  428.172252.173
   435.1 2250.39   451.8 2250.11  467.612252.174   479.5 2255.68     547 2254.38
   558.5 2257.68     574 2258.72   587.3 2264.97   621.9 2273.93   668.2 2282.68
   702.2 2287.18   796.2 2295.37   835.2 2300.95   866.3 2303.42   878.1 2306.05
#Mann= 3 ,-1,0
       0      .1       0  428.17    .045       0  467.61      .1       0
Bank Sta=428.17,467.61
XS Rating Curve= 0 ,0
Exp/Cntr=0.3,0.1

Type RM Length L Ch R = 1 ,57717   ,482.1,470,455.9
XS GIS Cut Line= 4
2254436.55953433680181.6000777062254822.29083438680347.032790147
2254873.62939859680459.2652846722255129.33507827680686.203001131
#Sta/Elev= 30
       0 2333.13    39.5 2330.51      70 2325.68    87.7 2321.13   118.2 2309.56
     173    2301   267.4 2272.07   294.8  2268.7   330.4 2256.47   356.5 2256.47
   377.1 2253.24   461.7 2253.65   470.5  2252.9   480.1 2249.87   492.4 2247.96
   510.8 2249.88     532 2250.28   540.5 2252.98   600.1 2279.16   617.1 2284.88
   662.5 2294.83   674.9 2295.77   693.6 2299.51     723 2312.07   732.8 2314.95
   749.8 2317.97   771.2 2318.61   813.9 2327.21   840.7 2330.77     885 2340.91
#Mann= 4 ,-1,0
       0      .1       0   480.1    .045       0   510.8      .1       0
  643.13     .08       0
Bank Sta=480.1,510.8
XS Rating Curve= 0 ,0
Exp/Cntr=0.3,0.1

Type RM Length L Ch R = 1 ,57247   ,444.5,422.5,402.2
XS GIS Cut Line= 4
2254086.78488141680689.1233742992254410.63898403680595.775277242
 2254524.9671836680659.3823658082254993.54329939680766.522695532
#Sta/Elev= 30
       0 2350.05    23.7 2344.32    39.9 2342.97    76.4 2334.65   122.2 2316.96
   138.8  2312.2   156.2 2304.52     168 2301.41   197.1 2300.08   205.4  2296.1
   246.7 2285.71     272 2277.25   305.3 2263.56   337.4 2253.03     351  2247.2
  363.48 2246.19   370.8 2244.98  403.932246.191   421.6 2251.58   515.5 2251.95
   524.5  2254.8   573.7 2261.51   598.4  2266.5   659.9 2284.49   713.3 2292.92
   725.6 2296.03   766.6  2297.6   807.6 2309.55   865.1 2318.78   948.5 2327.21
#Mann= 4 ,-1,0
       0      .1       0  363.48    .045       0  403.93      .1       0
  527.87     .08       0
Bank Sta=363.48,403.93
XS Rating Curve= 0 ,0
Exp/Cntr=0.3,0.1

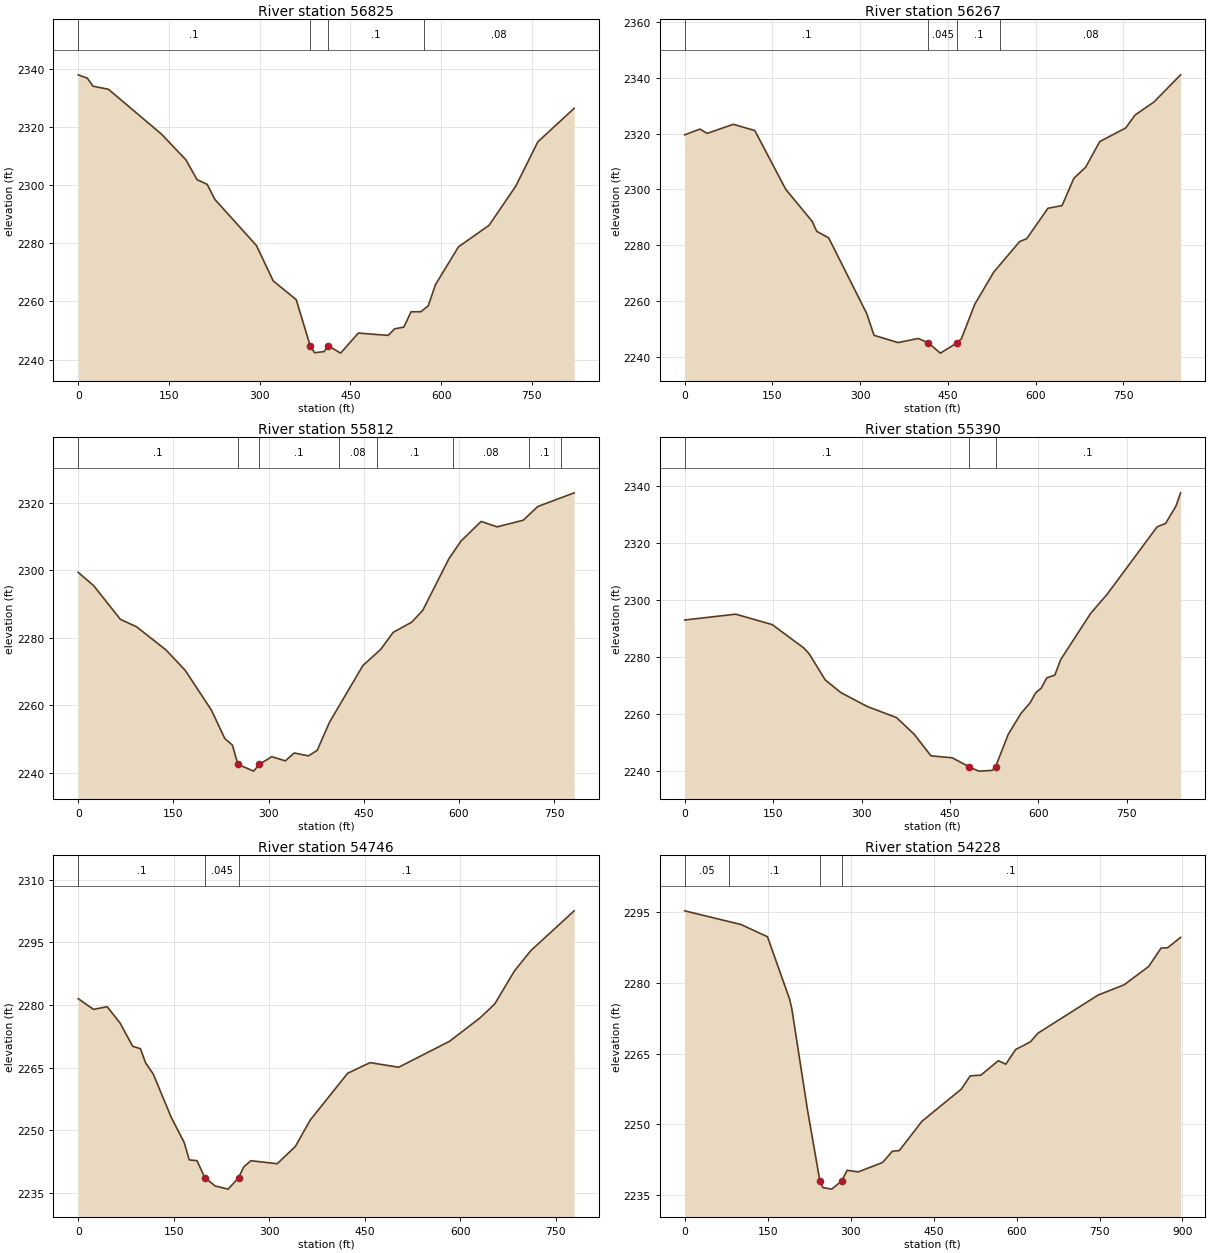
Type RM Length L Ch R = 1 ,56825   ,533.4,557.7,569.9
XS GIS Cut Line= 4
2254204.89165765681128.8349206262254546.59333976681020.226535518
2254689.02735499680922.7117152182254975.91953859680889.253138682
#Sta/Elev= 30
       0 2337.88    15.1 2336.73    24.4 2333.99    50.1  2332.9   137.8 2317.47
   177.9  2308.7   196.5 2301.86   213.3 2300.23   225.9 2295.08   294.8 2279.17
   322.4 2267.05   360.5  2260.6  383.512244.769   390.7 2242.36   406.4 2242.74
   413.7 2244.74   433.8 2242.22   463.1 2249.11   512.6 2248.32     523 2250.56
   538.4 2251.17   550.4 2256.43   566.5 2256.46   578.7 2258.45   590.7 2265.77
   628.7 2278.74   679.3 2286.15   723.6 2299.67   759.9 2314.83     820 2326.37
#Mann= 4 ,-1,0
       0      .1       0  383.51    .045       0   413.7      .1       0
  571.16     .08       0
Bank Sta=383.51,413.7
XS Rating Curve= 0 ,0
Exp/Cntr=0.3,0.1

Type RM Length L Ch R = 1 ,56267   ,467.5,454.7,439
XS GIS Cut Line= 4
2254250.52153336681350.6252197992254562.95678369681411.781028782
2254735.88746372681467.0881357652255081.44868868681425.180961975
#Sta/Elev= 30
       0 2319.56    26.1 2321.63    38.4 2320.09    83.2 2323.34   119.9 2321.11
   172.9    2300   217.7 2288.64   225.9 2284.97   246.2 2282.64   311.5 2255.41
   323.8 2247.69     365 2245.09   399.4 2246.57  416.622244.982   437.2 2241.31
  465.612244.983   473.2 2246.48     496 2258.82   528.4 2270.34   572.7 2281.31
   584.8 2282.32   621.1 2293.24   645.3  2294.2   665.4 2303.98   685.6 2307.95
   709.7 2317.15   754.1 2322.02   770.2 2326.69   802.4 2331.34     848 2341.08
#Mann= 4 ,-1,0
       0      .1       0  416.62    .045       0  465.61      .1       0
  539.92     .08       0
Bank Sta=416.62,465.61
XS Rating Curve= 0 ,0
Exp/Cntr=0.3,0.1

Type RM Length L Ch R = 1 ,55812   ,387.2,422.1,433.1
XS GIS Cut Line= 4
2254353.04688964681814.8564465072254574.04845447681888.721920691
2254703.80399549681818.1425163492255035.59047346 681593.05571356
#Sta/Elev= 30
       0 2299.41    24.4 2295.46    66.6 2285.46    91.9 2283.28   138.3 2276.41
   168.7 2270.34     210 2258.54     231 2250.14   243.1 2248.18  251.69 2242.49
   276.4 2240.46   285.5 2242.45     305 2244.76   326.5 2243.51   340.4 2245.84
   362.9 2244.99   376.6 2246.59   396.1 2254.96   448.8  2271.8   476.7 2276.54
   496.4 2281.61   525.7 2284.65     543 2288.12   584.2 2303.42   603.4 2308.71
   635.1 2314.51   660.3 2312.91   701.4 2314.87   724.4 2318.94   781.7    2323
#Mann= 8 ,-1,0
       0      .1       0  251.69    .045       0   285.5      .1       0
  410.73     .08       0  470.73      .1       0  590.73     .08       0
  710.73      .1       0  760.73     .08       0
Bank Sta=251.69,285.5
XS Rating Curve= 0 ,0
Exp/Cntr=0.3,0.1

Type RM Length L Ch R = 1 ,55390   ,612.1,644.4,651.6
XS GIS Cut Line= 4
 2254371.7752466681953.2891757422254722.39889604 682130.98820328
2254855.54405496682200.654295435 2255111.5675956682352.656489671
#Sta/Elev= 30
       0 2292.89    86.5 2294.94   148.4 2291.29   202.2 2283.06   211.2 2281.03
   238.3  2271.9     265 2267.44   309.9 2262.55   359.2  2258.7   389.1 2252.88
   417.7 2245.29   453.8 2244.59  482.93  2241.4   498.9 2239.92   521.5 2240.18
  527.162241.399   548.7 2252.79   570.5 2260.19     586 2263.91   595.3 2267.39
   604.6 2268.98   614.2 2272.61   627.8 2273.58   637.6 2278.97   688.3 2295.15
   716.8 2301.99   801.1 2325.52   815.7 2326.77   833.2 2332.81   841.1 2337.47
#Mann= 3 ,-1,0
       0      .1       0  482.93    .045       0  527.16      .1       0
Bank Sta=482.93,527.16
XS Rating Curve= 0 ,0
Exp/Cntr=0.3,0.1

Type RM Length L Ch R = 1 ,54746   ,543.2,518,481
XS GIS Cut Line= 4
2254238.62585976 682000.096497672254256.26581895682153.883432211
2254291.17721124682347.721475263 2254574.3561564682667.406732677
#Sta/Elev= 30
       0 2281.51      24 2278.95    45.4 2279.59    65.5 2275.74    85.6 2270.11
    97.7 2269.54   105.8 2266.16   117.9 2263.45     146 2253.13   166.3 2247.12
   174.4 2242.92   186.6 2242.72   198.8 2238.66     215 2236.68   235.4 2235.92
   251.92238.642   259.8 2241.21   271.2 2242.73   312.5    2242     341 2246.13
   364.4 2252.47   423.2 2263.66   458.3  2266.2   503.3  2265.1     583  2271.3
   630.8 2276.89   653.9  2280.2     685 2288.13   710.5 2292.97   778.8 2302.54
#Mann= 3 ,-1,0
       0      .1       0   198.8    .045       0   251.9      .1       0
Bank Sta=198.8,251.9
XS Rating Curve= 0 ,0
Exp/Cntr=0.3,0.1

Type RM Length L Ch R = 1 ,54228   ,380.5,373.5,369
XS GIS Cut Line= 4
2253614.54066976682488.2507700082253845.58665306682484.892405026
2253973.85525033      682479.9192254455.79131339682717.073096879
#Sta/Elev= 30
       0 2295.35   101.6 2292.45   149.7 2289.85   189.7 2276.59   193.7 2274.58
   221.8 2253.25  244.472237.982   249.7  2236.6   265.7 2236.26  283.812237.981
   293.7 2240.26   313.7 2239.92   357.8 2241.92   375.4  2244.3   388.1 2244.45
   428.9 2250.66   500.2  2257.5   516.3 2260.32   535.4 2260.45   567.1 2263.53
   580.5 2262.78   598.3  2265.9   625.1 2267.53   638.4 2269.35   747.5 2277.47
   794.5 2279.64     839 2283.55   861.3 2287.45     873  2287.5   896.6 2289.71
#Mann= 4 ,-1,0
       0     .05       0      80      .1       0  244.47    .045       0
  283.81      .1       0
Bank Sta=244.47,283.81
XS Rating Curve= 0 ,0
Exp/Cntr=0.3,0.1

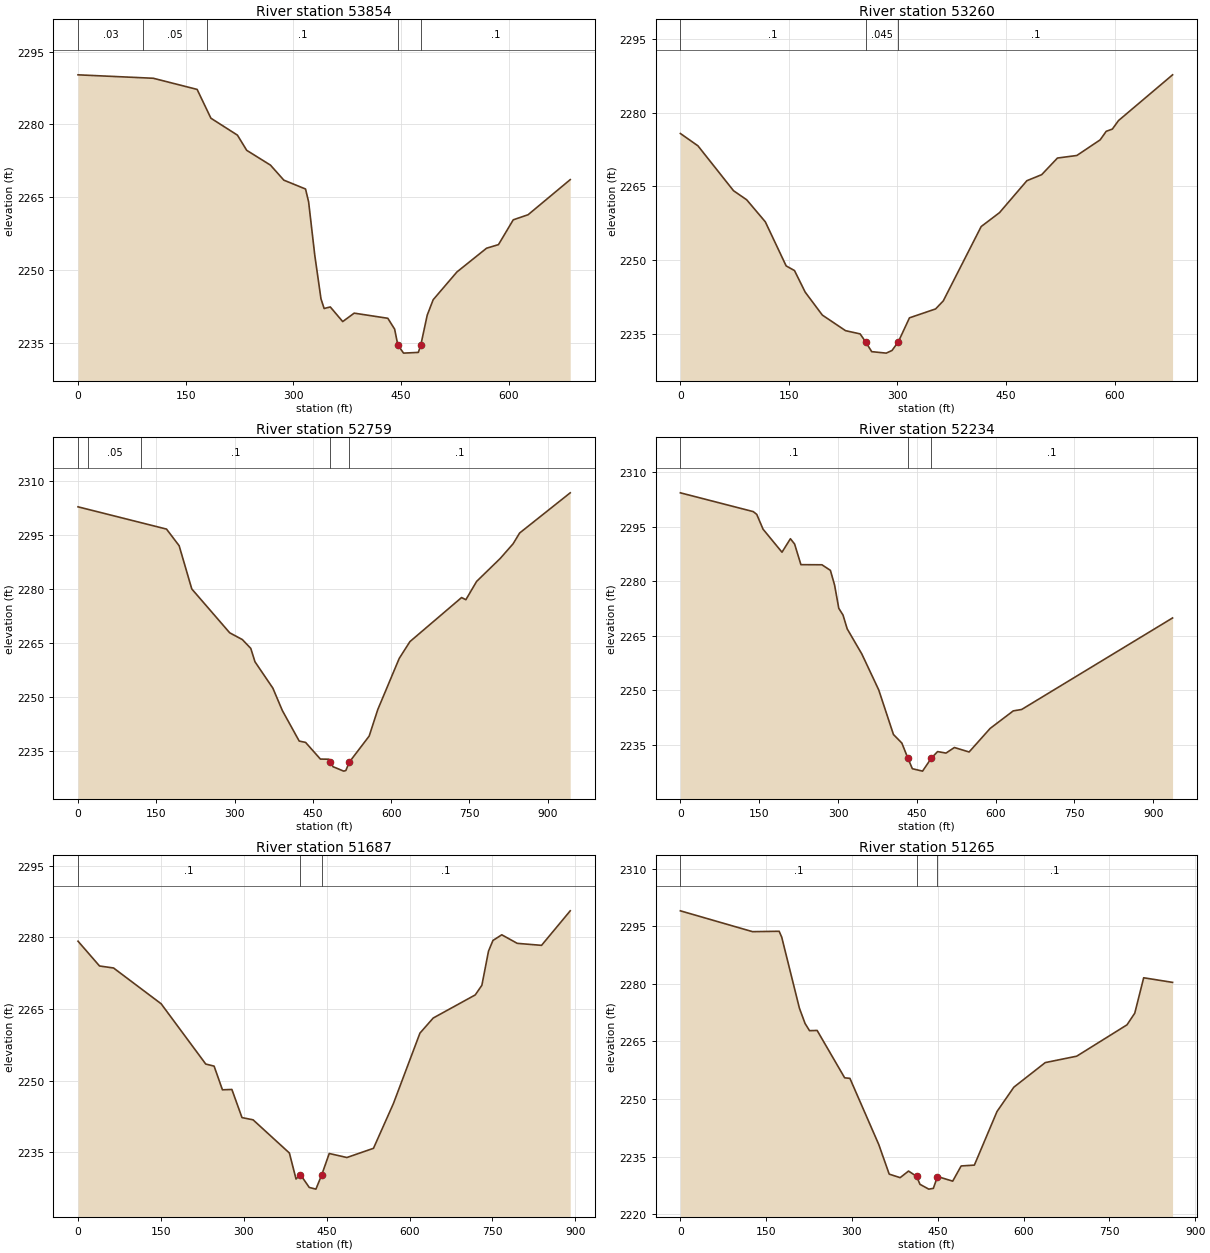
Type RM Length L Ch R = 1 ,53854   ,596.4,594.7,593.7
XS GIS Cut Line= 3
2253630.31730045682657.7986371942254018.81599824682815.220577361
2254276.91014358682747.708873879
#Sta/Elev= 30
       0 2290.25   104.9 2289.54     166 2287.24   185.2  2281.3   222.2  2277.8
   235.1 2274.67   268.2 2271.62   286.9 2268.51   317.1 2266.69   321.4 2264.03
     330 2252.99   338.6 2244.04     343 2242.03   351.6 2242.35   368.9 2239.33
   384.9 2241.07   431.8 2240.01   441.3 2237.76  445.712234.508   453.7 2232.82
   474.3 2232.97   477.7 2234.46   486.7 2240.66     495 2243.84   528.1 2249.57
   569.4 2254.47     586 2255.21   606.6 2260.33   627.3 2261.38     686 2268.62
#Mann= 5 ,-1,0
       0     .03       0      90     .05       0     180      .1       0
  445.71    .045       0   477.7      .1       0
Bank Sta=445.71,477.7
XS Rating Curve= 0 ,0
Exp/Cntr=0.3,0.1

Type RM Length L Ch R = 1 ,53260   ,506,501,494.5
XS GIS Cut Line= 4
2253464.42436592683072.979757328 2253606.1034983 683174.04270484
2253789.35393769 683189.11923761  2254095.116745683290.981926049
#Sta/Elev= 30
       0 2275.77    24.3 2273.26    73.4 2264.15    91.7 2262.29   117.4 2257.82
   146.2 2248.86   157.7 2247.92   172.5 2243.53   196.2 2238.87   228.3  2235.7
   248.4 2235.05  255.852233.466   264.4 2231.44   284.5 2231.14   292.5 2231.68
  301.282233.467   316.6 2238.31   352.7 2240.12   363.3 2241.75   415.7 2256.86
     441 2259.68   478.9 2266.18   499.3  2267.4   521.1 2270.78   547.9  2271.3
   580.1 2274.47   588.5 2276.21     597 2276.67   605.4 2278.38   680.2 2287.69
#Mann= 3 ,-1,0
       0      .1       0  255.85    .045       0  301.28      .1       0
Bank Sta=255.85,301.28
XS Rating Curve= 0 ,0
Exp/Cntr=0.3,0.1

Type RM Length L Ch R = 1 ,52759   ,524.1,525,523
XS GIS Cut Line= 4
     2253280.166      683628.6112253702.76301395683686.464911906
2253836.79865821683662.749603401     2254206.376      683571.507
#Sta/Elev= 30
       0 2302.78   169.6 2296.61   193.8    2292     218 2280.03   290.7 2267.87
   314.9    2266   331.1 2263.55   339.1 2259.85   373.4 2252.54   391.6 2246.33
   423.9 2237.87   436.1  2237.5   464.5 2232.88   480.8 2232.84  483.532231.997
   488.9 2230.75   509.2 2229.54   513.3 2229.71  519.762231.998     558 2239.26
   574.4 2246.57   615.6 2260.78   636.1 2265.43   735.1 2277.64   743.3 2277.04
   763.9 2282.11   809.2 2288.48   833.9 2292.55   846.3 2295.52   943.3 2306.66
#Mann= 5 ,-1,0
       0     .03       0      20     .05       0     120      .1       0
  483.53    .045       0  519.76      .1       0
Bank Sta=483.53,519.76
XS Rating Curve= 0 ,0
Exp/Cntr=0.3,0.1

Type RM Length L Ch R = 1 ,52234   ,545.6,546.7,550
XS GIS Cut Line= 3
       2253150.8      684119.1122253753.02333742684105.288861622
2254087.36876664684102.140137224
#Sta/Elev= 30
       0 2304.31   138.7 2299.15   145.4 2298.38   157.4 2294.31   193.4 2287.99
   209.4  2291.7   217.4 2290.24   229.4 2284.57   269.4 2284.54   285.5 2283.01
   293.5 2278.96   301.5 2272.56   309.5 2270.74   317.5 2266.93   345.5 2259.98
   377.5 2250.16   405.5 2237.91   421.5 2235.55     4332231.386   441.5  2228.5
   460.9 2227.84  477.532231.385   489.5 2233.21   505.5  2232.8   521.5 2234.33
   549.5  2233.1   589.5 2239.57   633.5 2244.39   649.5 2244.78   936.7 2269.93
#Mann= 3 ,-1,0
       0      .1       0     433    .045       0  477.53      .1       0
Bank Sta=433,477.53
XS Rating Curve= 0 ,0
Exp/Cntr=0.3,0.1

Type RM Length L Ch R = 1 ,51687   ,431.1,421.6,407.3
XS GIS Cut Line= 4
2253164.79906656684426.0466967142253437.50307313684635.431773152
2253649.73849051684648.0224559592253983.97707666684659.757310025
#Sta/Elev= 30
       0 2279.21    38.9 2274.02    64.3  2273.6   150.5  2266.1   231.2 2253.48
   246.3 2253.05   261.4 2248.09   278.5 2248.16   296.8 2242.27   316.9  2241.8
   382.6 2234.85   394.6 2229.41   402.6 2230.31   418.6 2227.64   430.6 2227.29
  441.092230.268   454.7 2234.75   486.7 2233.91   534.8 2235.84   570.9 2245.22
   618.9 2259.96   642.9 2263.12     719 2267.96     731 2269.98     743 2277.13
     751 2279.36     767 2280.55     795 2278.76     839 2278.34   890.9 2285.57
#Mann= 3 ,-1,0
       0      .1       0   402.6    .045       0  441.09      .1       0
Bank Sta=402.6,441.09
XS Rating Curve= 0 ,0
Exp/Cntr=0.3,0.1

Type RM Length L Ch R = 1 ,51265   ,501.1,501.5,496.4
XS GIS Cut Line= 4
2253171.78446335685234.7321634352253476.13009851685091.991242211
2253641.37558868684980.7100752382253906.02555349684791.831546755
#Sta/Elev= 30
       0 2299.05   126.1 2293.62   172.7 2293.72   177.2 2292.18   208.1 2273.68
     218 2269.69   225.8 2267.81   239.1 2267.87   287.2 2255.53   296.4 2255.38
   346.9 2238.12   365.1 2230.42   384.2  2229.5   398.9 2231.22   413.1 2229.82
   418.9 2227.76   434.3 2226.51   442.3 2226.71  449.462229.801   476.1 2228.59
   490.9 2232.55     514 2232.77   553.6 2246.75     583 2253.08   637.9 2259.49
   692.9 2261.16   780.8 2269.33   794.4 2272.37     810  2281.6   860.5  2280.4
#Mann= 3 ,-1,0
       0      .1       0   413.1    .045       0  449.46      .1       0
Bank Sta=413.1,449.46
XS Rating Curve= 0 ,0
Exp/Cntr=0.3,0.1

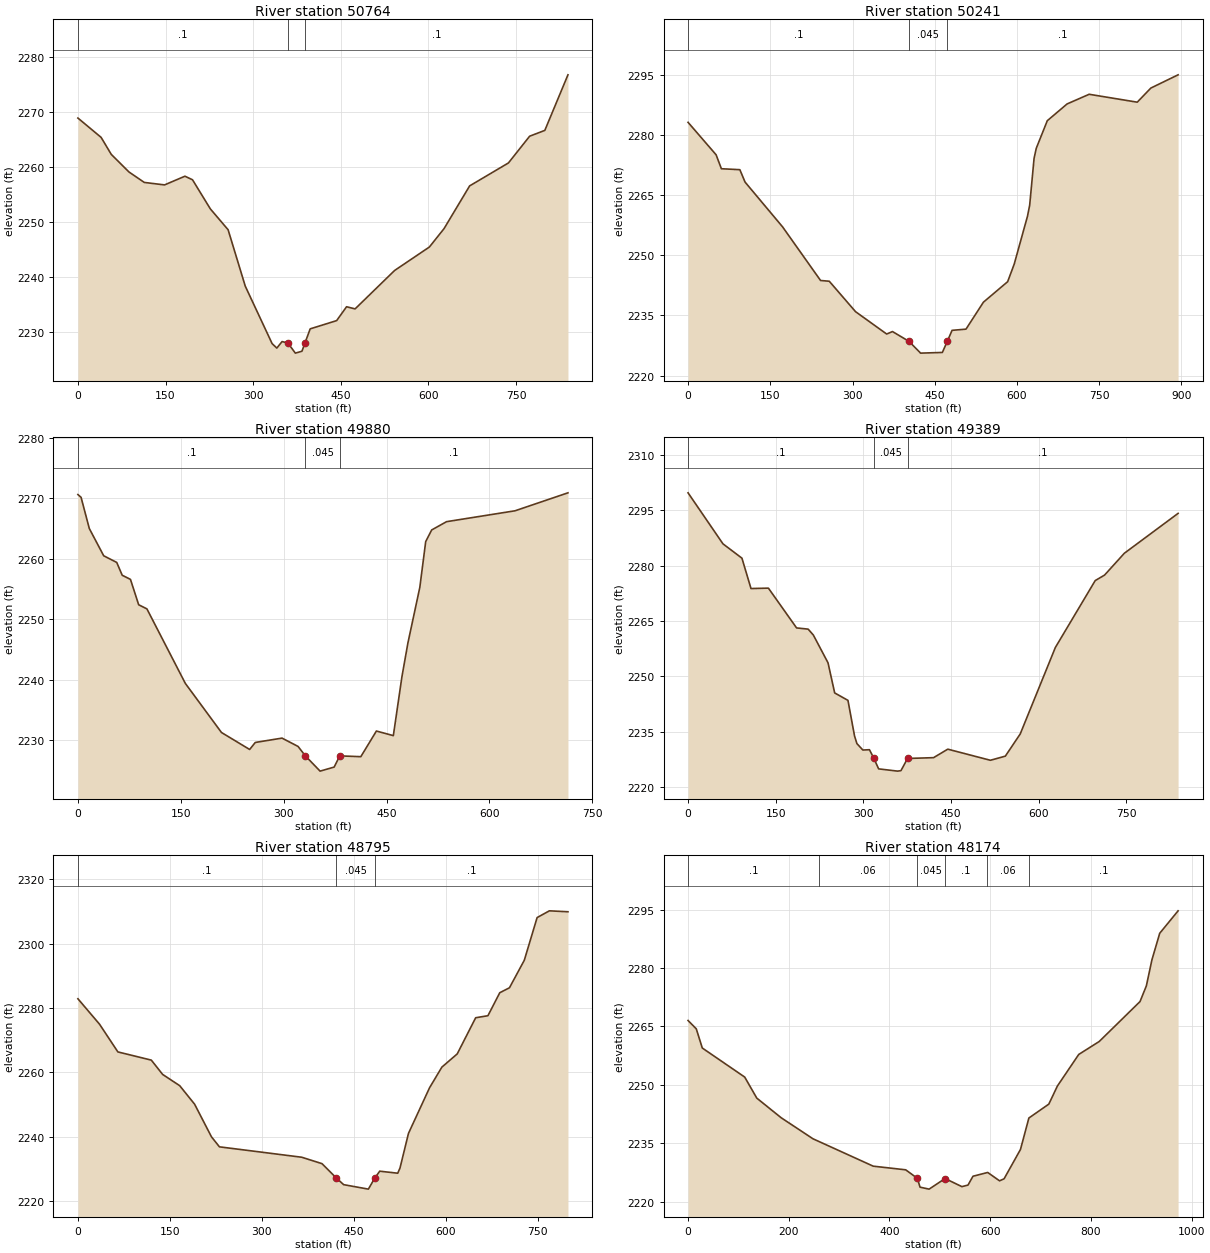
Type RM Length L Ch R = 1 ,50764   ,528.3,522.5,519.3
XS GIS Cut Line= 4
2253527.63444454685535.1965521792253776.75154225685429.043683299
2253942.30468775685272.641959876     2254159.685      685010.716
#Sta/Elev= 30
       0 2268.96    39.7 2265.45    57.1 2262.36    87.3 2259.17   113.6 2257.26
   148.3 2256.81   183.2 2258.39   196.2 2257.74   226.7 2252.45   257.1 2248.66
   286.5  2238.4   332.5 2227.95   340.5 2227.15   349.5 2228.33   359.4 2228.08
   372.2 2226.23   383.5 2226.57  388.762228.082   397.6 2230.64   442.9 2232.14
   459.9 2234.66   474.5 2234.27   542.1 2241.25   601.7 2245.52   626.7 2248.85
   670.6 2256.63     737  2260.8   773.3 2265.66   799.3 2266.72   838.9 2276.82
#Mann= 3 ,-1,0
       0      .1       0   359.4    .045       0  388.76      .1       0
Bank Sta=359.4,388.76
XS Rating Curve= 0 ,0
Exp/Cntr=0.3,0.1

Type RM Length L Ch R = 1 ,50241   ,388,361.1,344.2
XS GIS Cut Line= 4
2254083.89748891685967.8744889072254247.55124062 685721.15491357
2254349.46424728685503.9812241592254384.03670748685147.684022186
#Sta/Elev= 30
       0 2283.15    51.2 2275.05    60.8 2271.58    94.5 2271.34     104 2268.25
   172.4 2257.09   241.7 2243.72   257.6 2243.53   305.5 2235.95   362.3 2230.37
   372.9 2230.99  403.06 2228.54   424.2 2225.61   463.9 2225.78   472.8 2228.52
   481.6 2231.29     507 2231.59   538.8 2238.31     583 2243.42     595 2247.82
   619.2 2259.75   623.2 2262.52   631.2 2274.18   635.2 2276.68   655.3 2283.55
   691.5 2287.74   731.7 2290.14   819.4 2288.17   844.2 2291.69   893.9 2294.99
#Mann= 3 ,-1,0
       0      .1       0  403.06    .045       0   472.8      .1       0
Bank Sta=403.06,472.8
XS Rating Curve= 0 ,0
Exp/Cntr=0.3,0.1

Type RM Length L Ch R = 1 ,49880   ,505.5,490.8,472.5
XS GIS Cut Line= 4
2254696.36713123685925.751475679 2254700.4676137685743.927217932
 2254635.6078069685465.3094467212254539.81940283685238.114585568
#Sta/Elev= 30
       0 2270.64     4.6 2270.19    16.6 2265.03    37.6 2260.52    56.6 2259.42
    64.6  2257.3    76.6 2256.62    88.6 2252.42   100.6 2251.74   156.6 2239.42
   209.3  2231.3   250.4 2228.49   258.6 2229.65   297.6 2230.37     321 2228.99
  331.592227.437   353.1 2224.91   373.6 2225.58   381.8 2227.43   412.5  2227.3
   435.2 2231.54   459.9 2230.78   472.4  2240.5   481.1 2246.08   498.5 2255.29
   507.1 2262.87   515.8 2264.79   537.5 2266.16   637.4 2267.96   714.5 2270.93
#Mann= 3 ,-1,0
       0      .1       0  331.59    .045       0   381.8      .1       0
Bank Sta=331.59,381.8
XS Rating Curve= 0 ,0
Exp/Cntr=0.3,0.1

Type RM Length L Ch R = 1 ,49389   ,579.9,594.4,601.8
XS GIS Cut Line= 4
2255308.92112791685530.5323412752255119.91776548685363.739600695
2254864.36268565685140.324181458     2254660.157      685001.362
#Sta/Elev= 30
       0  2299.7    59.7 2285.88    92.2 2281.99   107.7 2273.76   137.5 2273.87
   185.7 2263.09   205.5 2262.76   214.4 2261.16   239.5 2253.63   250.9 2245.47
   273.6 2243.46   284.9 2233.79   288.9 2231.75   299.1    2230   310.4 2230.08
  317.732227.812   326.1 2224.89   358.6 2224.28   364.3 2224.41   375.6 2227.71
   420.1 2227.93   444.4 2230.23   517.3 2227.22   542.9 2228.34   568.4 2234.36
   628.5 2257.79   696.7 2275.92   712.7 2277.41   746.5 2283.32   838.5 2294.13
#Mann= 3 ,-1,0
       0      .1       0  317.73    .045       0   375.6      .1       0
Bank Sta=317.73,375.6
XS Rating Curve= 0 ,0
Exp/Cntr=0.3,0.1

Type RM Length L Ch R = 1 ,48795   ,614.5,620.9,613.5
XS GIS Cut Line= 4
     2255620.988      685256.5862255426.67196121684922.932436057
2255349.46834627684783.7553833392255196.56397875684580.972318975
#Sta/Elev= 30
       0 2282.87    35.3 2274.95    65.2 2266.34   119.7 2263.79   138.2 2259.34
     166 2255.84   190.3 2250.09   217.8 2239.94   230.8 2236.82     365 2233.59
   398.1 2231.59   421.6 2227.11   433.4 2225.06   473.7 2223.67   484.2 2227.12
   492.2 2229.25   521.6 2228.62   525.3 2230.25   539.1    2241   573.5  2255.2
   593.6 2261.62   618.6 2265.72   648.7 2276.97   668.7  2277.6     688 2284.75
   703.8 2286.29     728 2294.85   748.9 2308.12   768.9 2310.22   799.2 2309.93
#Mann= 3 ,-1,0
       0      .1       0   421.6    .045       0   484.2      .1       0
Bank Sta=421.6,484.2
XS Rating Curve= 0 ,0
Exp/Cntr=0.3,0.1

Type RM Length L Ch R = 1 ,48174   ,419.9,424.7,402.3
XS GIS Cut Line= 4
     2256067.754      685109.435 2256050.0902984684816.533793508
2255854.00261214684486.079875471     2255651.102      684271.361
#Sta/Elev= 30
       0 2266.51    16.3 2264.38    28.3 2259.44   112.5 2251.98   136.5 2246.57
     185 2241.52   248.1 2236.12   367.7 2229.09   432.2 2228.15  455.262225.976
   460.7 2223.69   478.7 2223.19   510.4 2225.91   543.8 2223.83   555.9 2224.23
   565.8  2226.5     595 2227.47   618.6 2225.32   627.6 2225.85   660.1 2233.38
   676.8 2241.46   716.4 2245.03   733.4 2249.67   775.8 2257.79   816.5 2261.12
   897.5 2271.38   910.1 2275.41   921.1 2282.08   936.6 2288.92   973.1 2294.69
#Mann= 6 ,-1,0
       0      .1       0     260     .06       0  455.26    .045       0
   510.4      .1       0  593.43     .06       0  677.69      .1       0
Bank Sta=455.26,510.4
XS Rating Curve= 0 ,0
Exp/Cntr=0.3,0.1

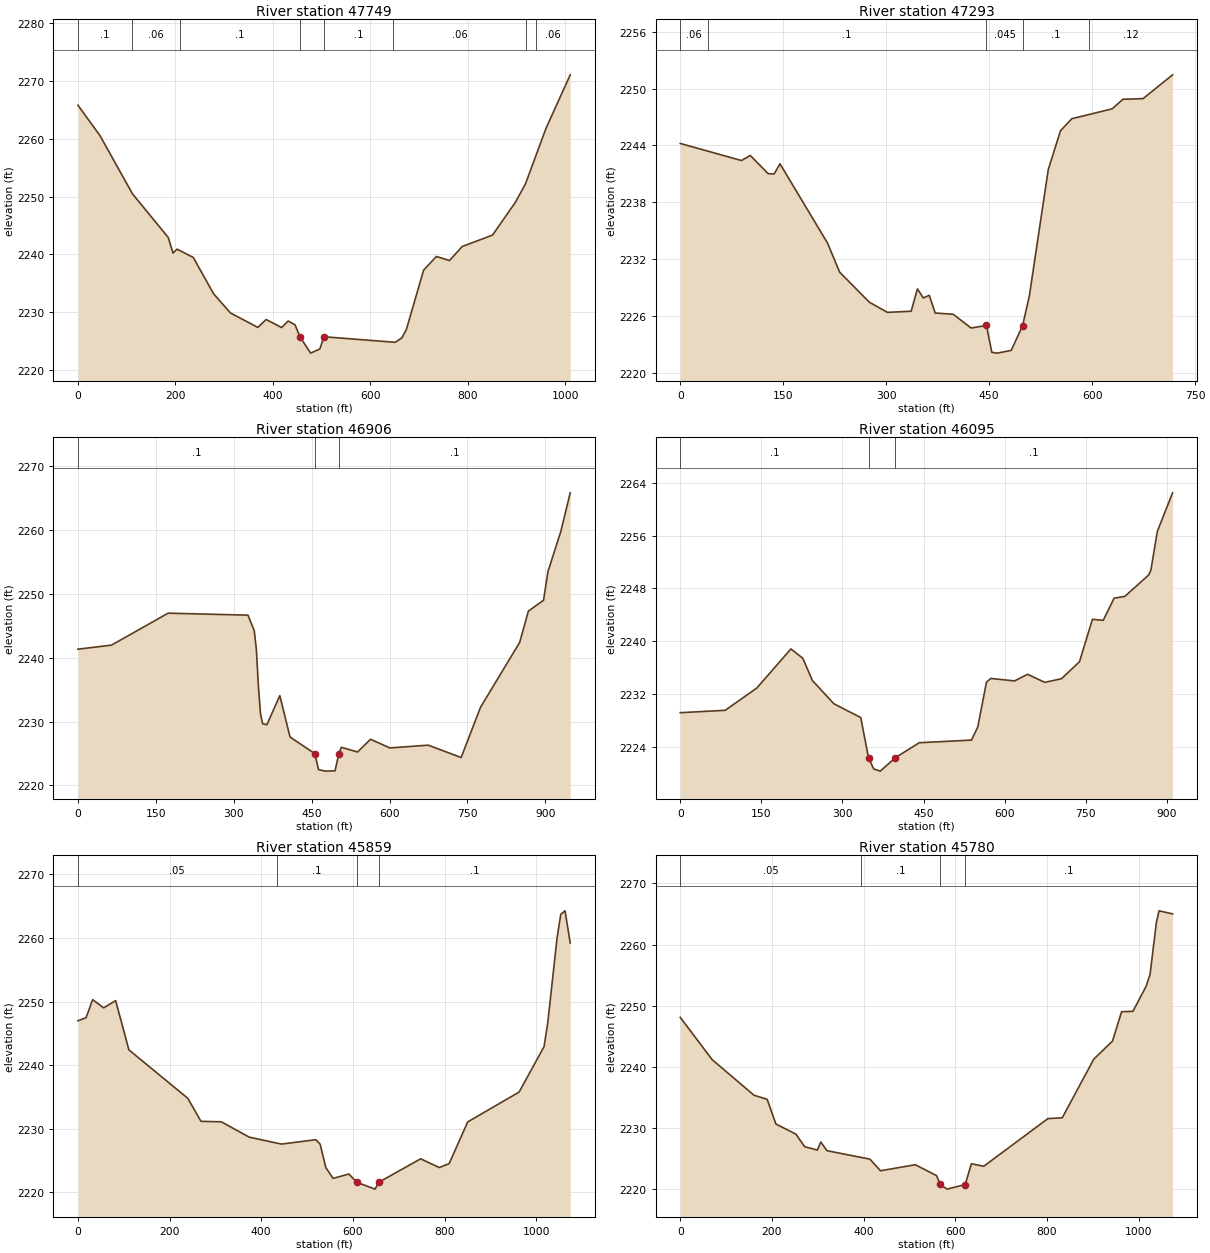
Type RM Length L Ch R = 1 ,47749   ,448.4,456.2,452.6
XS GIS Cut Line= 4
 2256397.2208447684952.8538923572256316.46410398684667.586227962
2256131.72674967684331.887272128     2255877.462      684121.522
#Sta/Elev= 30
       0 2265.79    45.4 2260.52   111.9 2250.48   185.3 2242.93   195.1 2240.24
   203.4 2240.92   236.6 2239.48   278.2 2233.22   312.9 2229.89   369.1 2227.39
     386 2228.76   417.9 2227.37     431  2228.5   445.3 2227.85  455.222225.795
   477.3 2222.95   496.2 2223.67   504.6 2225.78   650.8 2224.82   664.5 2225.59
   673.6 2227.02     709 2237.28   735.2 2239.65   762.1 2238.95   788.1 2241.37
   850.4 2243.35   897.2 2249.01   917.9 2252.19     960 2261.79  1009.7 2271.04
#Mann= 8 ,-1,0
       0      .1       0     110     .06       0     210      .1       0
  455.22    .045       0   504.6      .1       0  646.48     .06       0
  919.65      .1       0  939.65     .06       0
Bank Sta=455.22,504.6
XS Rating Curve= 0 ,0
Exp/Cntr=0.3,0.1

Type RM Length L Ch R = 1 ,47293   ,393,386.7,380.1
XS GIS Cut Line= 5
     2256710.138      684687.545 2256634.0277599684502.845591585
2256535.40131725684273.9060606482256514.65355307684189.411606517
2256354.03645336684105.733412397
#Sta/Elev= 30
       0 2244.21    89.1 2242.41   102.1 2242.94     128 2241.02   136.7 2240.99
   145.3 2242.06   214.6 2233.69   232.1 2230.64   275.5 2227.46   301.8 2226.39
   336.4 2226.51   345.5 2228.87     354 2227.91   362.7 2228.19   371.4 2226.32
   397.6 2226.19   423.7 2224.74     446 2225.01   453.9 2222.17     462 2222.09
   482.1 2222.38   498.6 2224.96   508.5 2228.11   536.1 2241.45   553.9 2245.55
   570.4 2246.82   629.1 2247.86   644.8 2248.87   674.2 2248.94   717.2 2251.45
#Mann= 5 ,-1,0
       0     .06       0      40      .1       0     446    .045       0
   498.6      .1       0  596.05     .12       0
Bank Sta=446,498.6
XS Rating Curve= 0 ,0
Exp/Cntr=0.3,0.1

Type RM Length L Ch R = 1 ,46906   ,786.6,811.2,813.3
XS GIS Cut Line= 5
2256992.38584044684601.0927361762256936.82198892684221.847972908
2256872.25334183684110.8596911822256799.37491705683851.693482313
     2256750.671      683692.045
#Sta/Elev= 30
       0 2241.31    64.6 2241.94   173.7 2246.94   327.4 2246.63   339.5  2244.2
   343.5 2241.35   347.6  2235.4   351.6 2231.15   355.7 2229.65   363.8  2229.5
   388.7 2234.05   408.4 2227.58   456.2 2224.97   463.2 2222.48   476.6 2222.24
   495.1  2222.3  502.362224.959   507.1 2225.97   538.4 2225.23   563.3 2227.22
   600.7 2225.87   674.5  2226.3   737.8 2224.37   775.2 2232.24   850.5 2242.37
   867.2 2247.25   896.5 2248.97   904.8 2253.41   929.7 2259.72   947.8 2265.76
#Mann= 3 ,-1,0
       0      .1       0   456.2    .045       0  502.36      .1       0
Bank Sta=456.2,502.36
XS Rating Curve= 0 ,0
Exp/Cntr=0.3,0.1

Type RM Length L Ch R = 1 ,46095   ,253.4,236,205.1
XS GIS Cut Line= 4
2257196.78830405684586.2918966132257324.79985064684314.290910019
2257341.69052878684047.6645826672257340.77399592683704.920163937
#Sta/Elev= 30
       0 2229.14    83.1  2229.5   141.7 2232.89   204.6 2238.82   226.7 2237.39
   244.4 2234.02   284.2 2230.49   333.8  2228.4  348.122222.314   357.8  2220.6
   369.9 2220.27   397.9 2222.31     442 2224.58   538.5 2224.98   550.2 2226.96
   566.3 2233.77   574.3 2234.34   618.3 2233.96   642.3 2234.97   674.3 2233.74
   705.1  2234.3   738.3 2236.87   762.3 2243.31   782.3 2243.16   802.3 2246.52
   822.3  2246.8   866.3 2250.04   870.3 2250.74   882.3 2256.65   910.5 2262.51
#Mann= 3 ,-1,0
       0      .1       0  348.12    .045       0   397.9      .1       0
Bank Sta=348.12,397.9
XS Rating Curve= 0 ,0
Exp/Cntr=0.3,0.1

Type RM Length L Ch R = 1 ,45859   ,79.7,79.2,73.9
XS GIS Cut Line= 6
 2257698.5621471684592.0071289922257851.45677254684362.062950626
2257538.78985601 684169.898421852257476.92609036684120.898699423
2257412.35120195684061.0085230012257366.20400964683800.913064474
#Sta/Elev= 30
       0 2246.97    17.8 2247.46    32.2  2250.3    56.2 2249.01    82.4 2250.14
   111.3 2242.39   239.8 2234.77   268.6 2231.14   312.9 2231.07     374 2228.65
   444.1 2227.56   519.1 2228.25   528.6 2227.55     541 2223.86   556.8 2222.16
   591.4 2222.85   608.6 2221.55   648.4 2220.47  656.452221.546   747.9 2225.24
   788.5 2223.87   810.1 2224.48   850.6 2231.05   962.8 2235.75  1017.2 2242.91
  1025.3 2246.66  1045.6 2260.03  1053.7 2263.74    1063 2264.28  1074.3 2259.23
#Mann= 4 ,-1,0
       0     .05       0  433.38      .1       0   608.6    .045       0
  656.45      .1       0
Bank Sta=608.6,656.45
XS Rating Curve= 0 ,0
Exp/Cntr=0.3,0.1

Type RM Length L Ch R = 1 ,45780   ,414.8,429,451.4
XS GIS Cut Line= 6
2257740.60043975684551.1629082992257893.49506519684321.218729933
2257580.82814865684129.054201157  2257518.964383684080.054478731
 2257454.3894946684020.1643023092257408.24230228683760.068843782
#Sta/Elev= 30
       0 2248.11    69.6  2241.2   160.9 2235.38   189.7 2234.72   208.7 2230.67
   252.2 2229.03   271.4 2226.97   299.1 2226.42   306.7 2227.74     320 2226.32
   413.8 2224.93     437 2223.03   512.8 2224.02   559.3 2222.24     567  2220.8
   582.2 2220.03  621.682220.781   635.3 2224.18   662.3 2223.77   802.2 2231.56
   833.5 2231.69   902.5  2241.3   943.2 2244.23     963 2249.03   987.8  2249.1
  1016.3 2253.15  1025.1 2255.11  1038.9 2263.61  1044.7 2265.53  1074.3 2265.03
#Mann= 4 ,-1,0
       0     .05       0  393.38      .1       0     567    .045       0
  621.68      .1       0
Bank Sta=567,621.68
XS Rating Curve= 0 ,0
Exp/Cntr=0.3,0.1

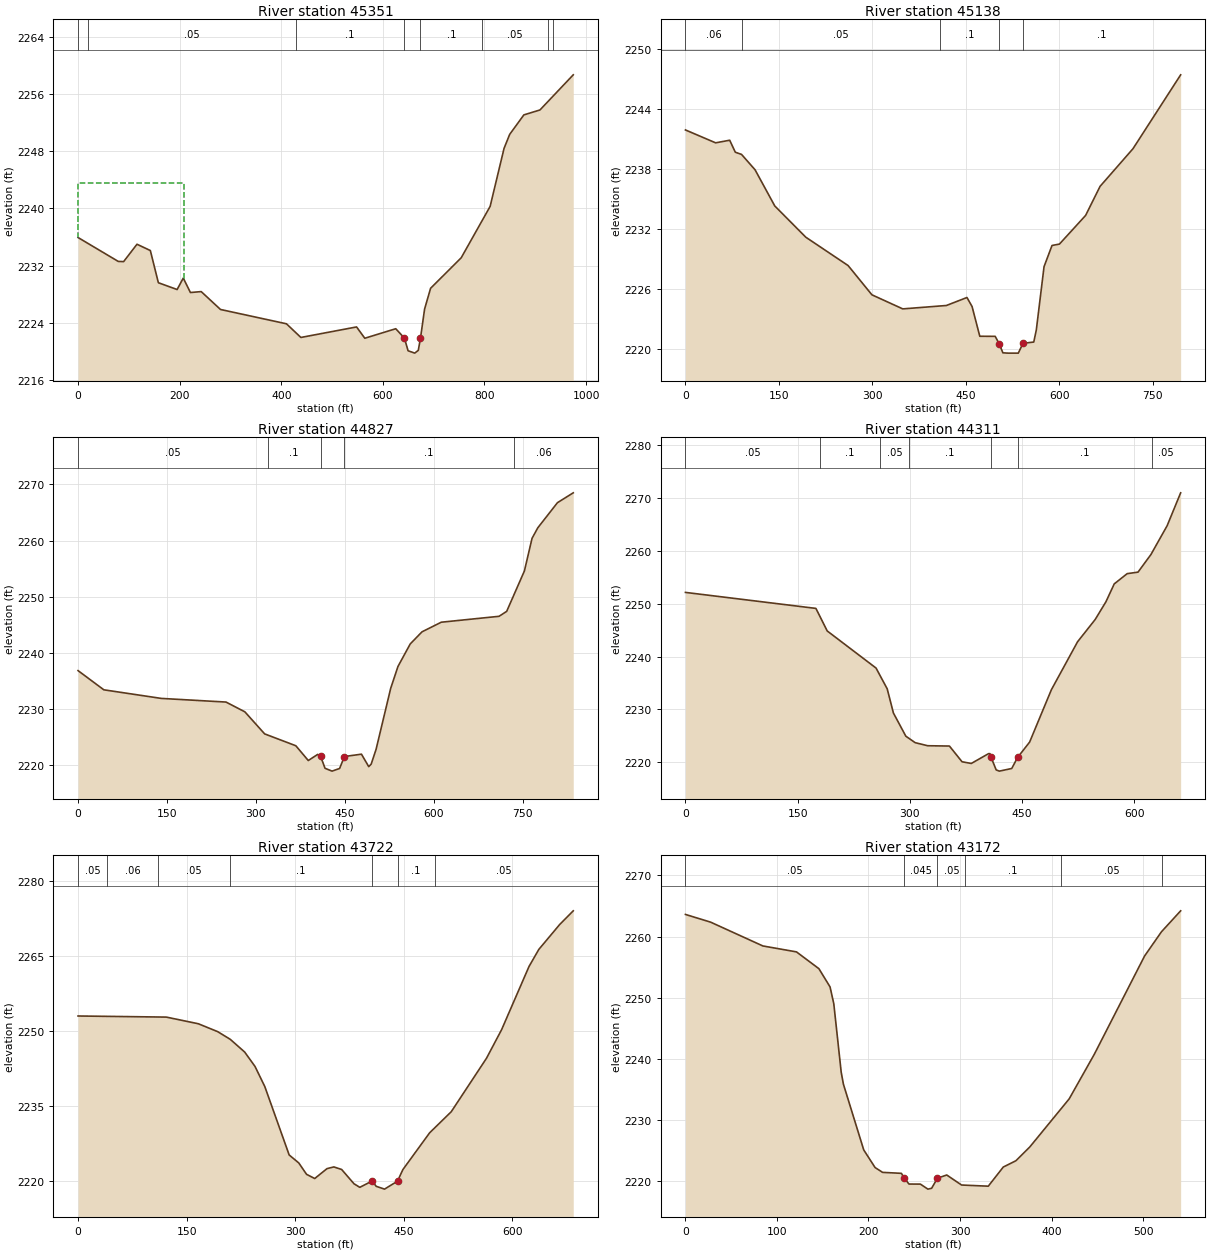
Type RM Length L Ch R = 1 ,45351   ,214.6,212.9,210.9
XS GIS Cut Line= 4
2257888.30731751684569.2839422712258050.27042906 684380.16555167
2257972.25359081683920.0986656312257786.50363692683739.485303738
#Sta/Elev= 30
       0 2235.94    79.1  2232.6    89.7 2232.57     116    2235   142.3 2234.12
   158.1 2229.62     195 2228.67   207.1 2230.27   221.2 2228.25   242.4 2228.38
   280.4 2225.88   410.2 2223.88   438.6 2221.97   548.2 2223.44   564.4 2221.86
   625.3 2223.19  642.332221.888   649.6 2220.11   662.7 2219.78   669.7 2220.17
     674 2221.87   682.1 2225.94   693.9 2228.84   754.2 2233.11   811.1 2240.29
   838.5  2248.4   849.6 2250.36   877.5 2253.08   909.2 2253.77   974.7 2258.68
#Mann= 8 ,-1,0
       0      .1       0      20     .05       0  428.99      .1       0
  642.33    .045       0     674      .1       0  795.63     .05       0
  925.63      .1       0  935.63     .05       0
#XS Ineff= 2 , 0
          207.94 2243.58
Permanent Ineff=
       F       F
Bank Sta=642.33,674
XS Rating Curve= 0 ,0
Exp/Cntr=0.3,0.1

Type RM Length L Ch R = 1 ,45138   ,308.5,311.1,309.8
XS GIS Cut Line= 4
2258369.33467267684439.9866960552258263.14467745684238.554127789
2258167.90210441683855.394351196 2258196.3654021683685.709307277
#Sta/Elev= 30
       0 2241.94    48.4 2240.65      71 2240.91      80 2239.71      90 2239.49
   111.7 2237.95   143.3 2234.33   193.1  2231.2     261 2228.36   299.2 2225.43
   348.7 2224.02   418.7 2224.36   451.7 2225.16   459.9 2224.26   472.3 2221.28
     497 2221.27   503.22220.554   509.4 2219.62   517.6 2219.59   534.1 2219.59
   541.6 2220.57   558.9  2220.7     563 2221.91   575.4 2228.25   588.2 2230.37
   600.1 2230.51   642.1 2233.38   665.3 2236.29   718.1 2240.06   794.6 2247.46
#Mann= 5 ,-1,0
       0     .06       0      90     .05       0  407.71      .1       0
   503.2    .045       0   541.6      .1       0
Bank Sta=503.2,541.6
XS Rating Curve= 0 ,0
Exp/Cntr(USF)=0,0
Exp/Cntr=0.3,0.1

Type RM Length L Ch R = 1 ,44827   ,515.3,516.2,513.7
XS GIS Cut Line= 4
2258523.82903615684385.5631402362258531.27838699  684136.0734851
2258463.75063599683837.9914768792258363.88426349683576.270868255
#Sta/Elev= 30
       0 2236.84    43.5 2233.42   140.4 2231.89   249.6 2231.24   281.4  2229.5
   314.8 2225.57   367.4 2223.46   388.4 2220.83   404.3 2221.92  409.322221.562
   416.6 2219.45   428.5 2218.94   441.2 2219.41   449.4 2221.54   478.1 2221.96
   490.4 2219.74   494.5 2220.19   502.8 2222.83   527.4 2233.67   539.7 2237.58
   560.4 2241.59   580.3 2243.75   612.8 2245.46   710.2 2246.51   723.1 2247.39
     753 2254.59   765.9  2260.4   775.6 2262.27   808.7 2266.74   835.4  2268.5
#Mann= 5 ,-1,0
       0     .05       0   319.6      .1       0  409.32    .045       0
   449.4      .1       0  735.24     .06       0
Bank Sta=409.32,449.4
XS Rating Curve= 0 ,0
Exp/Cntr=0.3,0.1

Type RM Length L Ch R = 1 ,44311   ,569.5,589,605.1
XS GIS Cut Line= 4
2258849.76027743684208.091454183 2259012.3183561683993.958464049
2258949.92887697 683778.423105662258856.10799617683638.146785812
#Sta/Elev= 30
       0 2252.16   174.4 2249.13   189.5 2244.86   254.8 2237.83   269.7  2233.9
     278 2229.32   294.6 2224.93   307.1  2223.7   323.8 2223.12   352.9 2223.06
   369.7 2220.09   382.1 2219.76   405.2 2221.62   407.1 2221.62  408.632220.906
   415.4 2218.54   419.6 2218.31   436.2 2218.81     444  2220.9   460.1 2223.81
   489.2 2233.73   524.2 2242.81   547.7 2247.02   562.1 2250.38   573.2 2253.77
   590.5 2255.71     605    2256   622.3 2259.34   643.9 2264.78     662 2271.02
#Mann= 7 ,-1,0
       0     .05       0     180      .1       0     260     .05       0
  298.85      .1       0  408.63    .045       0     444      .1       0
  623.23     .05       0
Bank Sta=408.63,444
XS Rating Curve= 0 ,0
Exp/Cntr=0.3,0.1

Type RM Length L Ch R = 1 ,43722   ,538.8,550.1,559.4
XS GIS Cut Line= 4
2259212.87816267 684091.045280082259437.42859093683930.926490191
2259576.10487169683777.1029465912259665.20929252683596.376022186
#Sta/Elev= 30
       0 2252.97     122 2252.75   166.2 2251.42     193 2249.84   210.4  2248.3
   230.3 2245.76   244.6 2242.88   258.1 2238.86   291.8 2225.18   305.1 2223.58
   315.8 2221.31   327.1 2220.47   344.1 2222.45   353.5 2222.79   364.3 2222.28
   381.4 2219.42   389.4 2218.71   406.4 2219.97   412.1 2218.91   423.6 2218.35
  441.512219.945   448.9 2222.25   485.9 2229.61   515.8 2233.83   564.5 2244.52
   585.4 2250.24   623.3 2262.88   636.8 2266.28   665.7 2271.27   684.4    2274
#Mann= 7 ,-1,0
       0     .05       0      40     .06       0     110     .05       0
     210      .1       0   406.4    .045       0  441.51      .1       0
   492.9     .05       0
Bank Sta=406.4,441.51
XS Rating Curve= 0 ,0
Exp/Cntr=0.3,0.1

Type RM Length L Ch R = 1 ,43172   ,308.3,310.9,311
XS GIS Cut Line= 4
 2259401.2217541684381.2470591112259583.44021737684344.870068303
2259791.67579239684292.9719920692259914.57851252684224.439903811
#Sta/Elev= 30
       0 2263.62    27.5 2262.36    84.6 2258.47   121.3  2257.5   145.8 2254.76
     158 2251.78   162.1 2249.02   170.2 2237.82   172.6 2235.88   194.8 2225.14
   207.2 2222.26   215.4 2221.47     236 2221.31     239 2220.52   244.3 2219.56
   256.7 2219.55   264.9 2218.73     269 2218.87   275.3 2220.51   285.5 2221.04
   301.7  2219.4   330.9 2219.21   347.3 2222.34   361.1 2223.37   376.2 2225.61
   419.3 2233.48   446.8 2240.78   501.7 2256.83   520.1 2260.78   541.1 2264.21
#Mann= 6 ,-1,0
       0     .05       0     239    .045       0   275.3     .05       0
  305.81      .1       0  410.42     .05       0  520.42     .06       0
Bank Sta=239,275.3
XS Rating Curve= 0 ,0
Exp/Cntr(USF)=0,0
Exp/Cntr=0.3,0.1