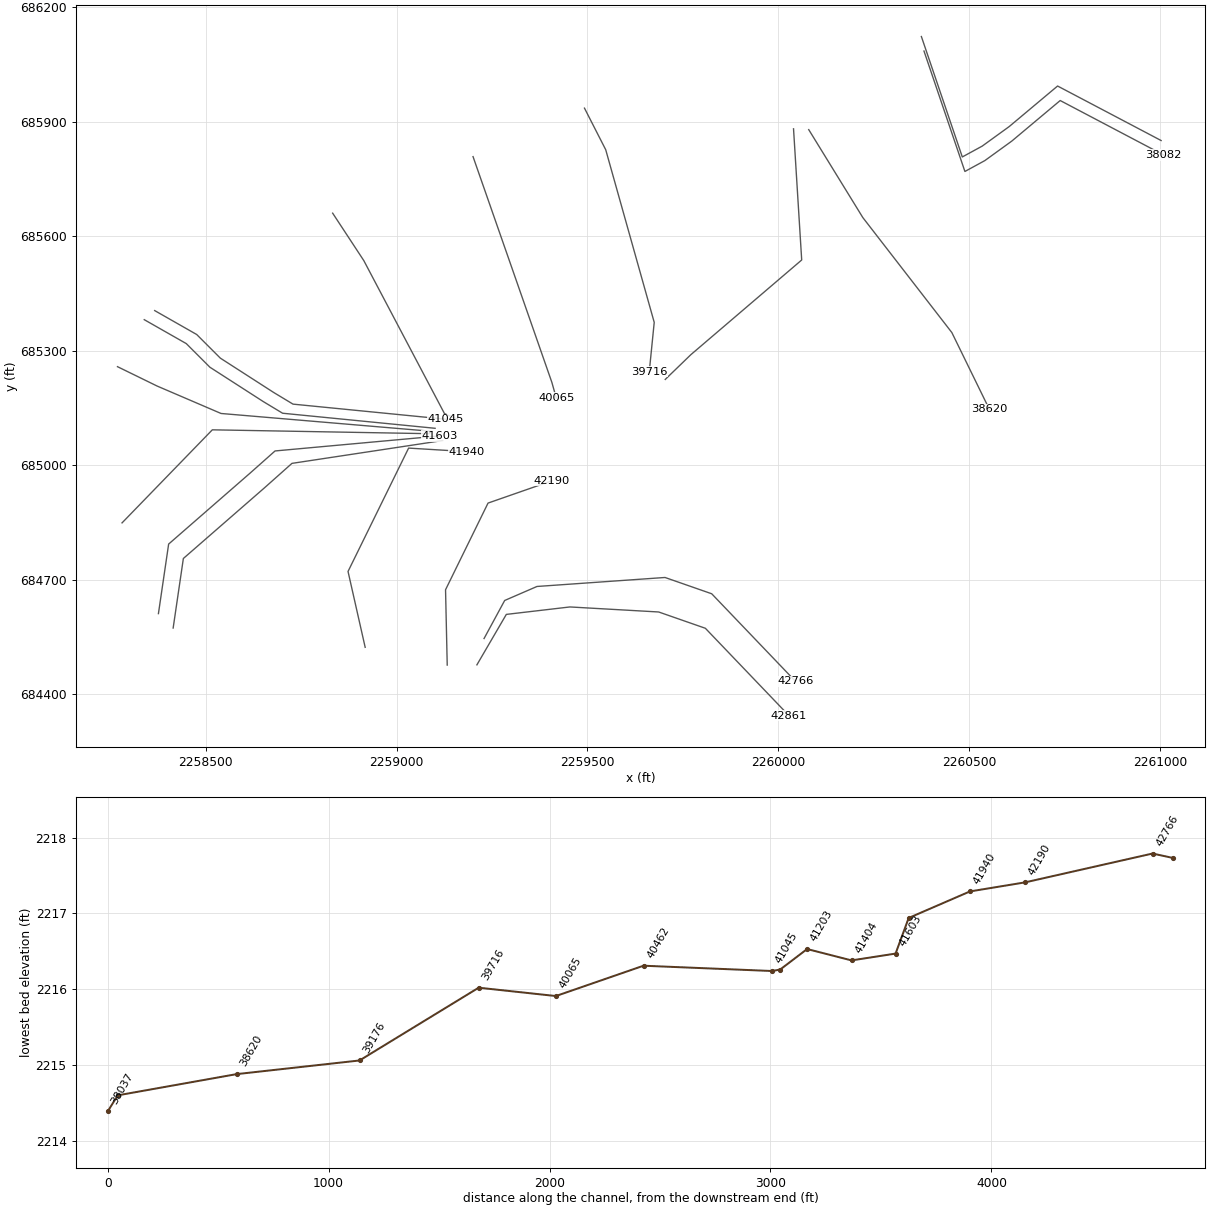
HEC-RAS study ROARCK.prj: ROARCK

--- ROARCK.g01 (geometry) --- (continued)

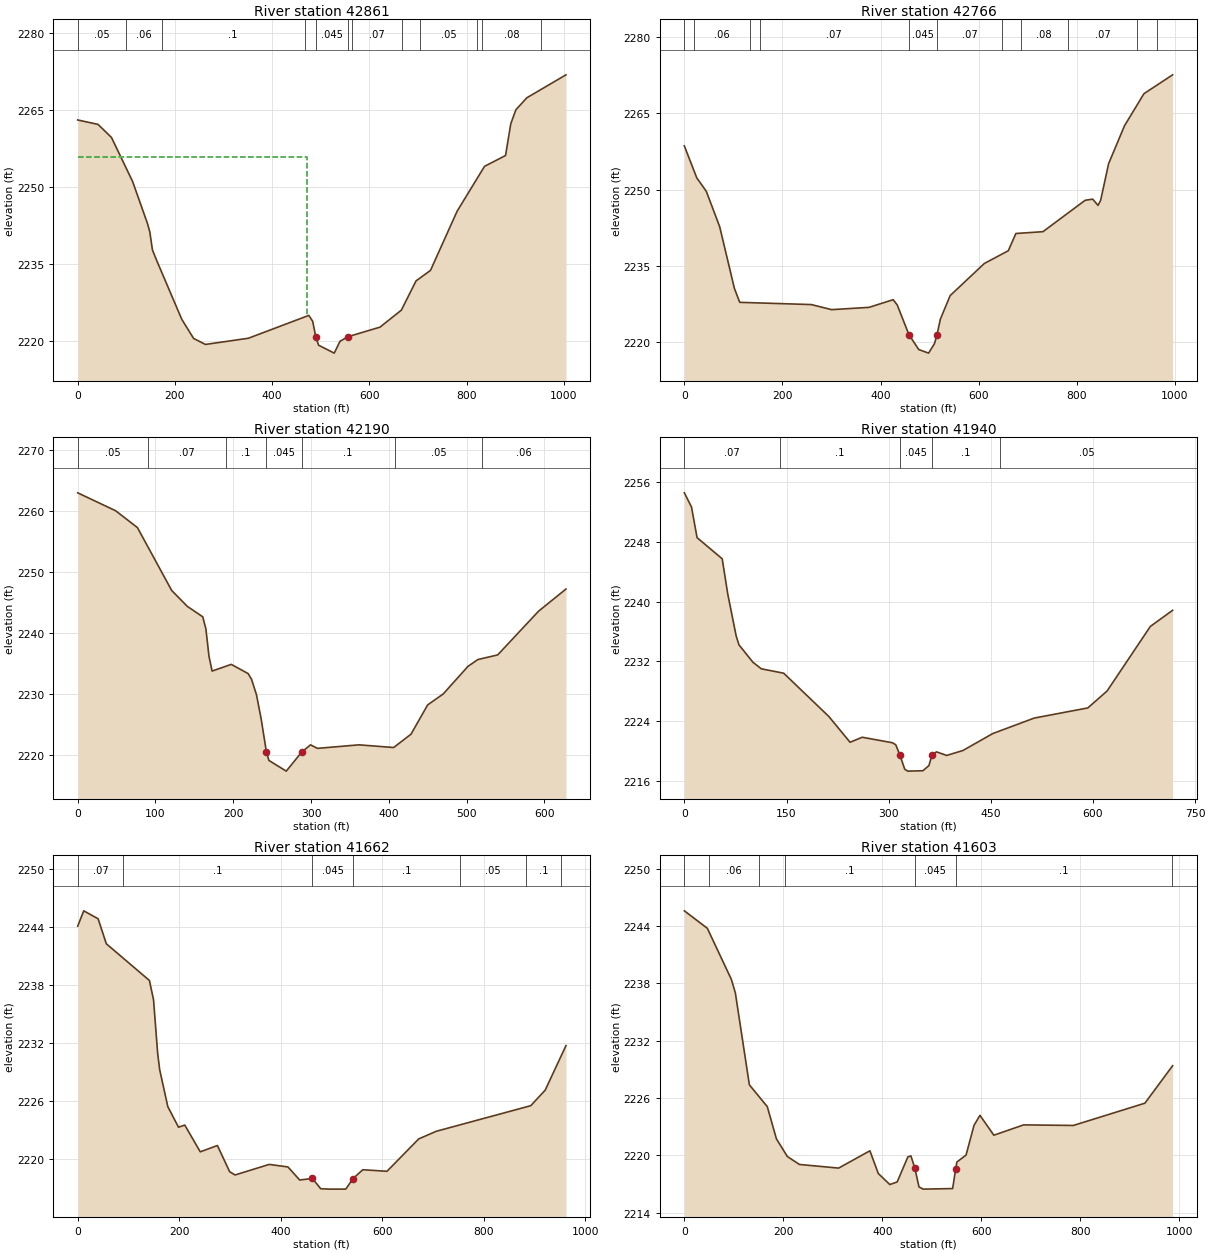
Type RM Length L Ch R = 1 ,42861   ,92.2,94.4,93.6
XS GIS Cut Line= 6
2259210.41386994684476.9462133212259287.49175287684609.121026604
2259454.09512443684628.6283834012259686.60172842684615.447736916
2259808.97349269684572.7498728132260028.22265701684343.602455148
#Sta/Elev= 30
       0 2263.03    41.8 2262.17    69.4 2259.64   112.8  2251.1   143.4 2242.94
   148.3 2241.28   153.7 2237.78   162.7 2235.67   214.1 2224.29   238.4 2220.58
   262.7 2219.42     351 2220.62   475.3 2225.06   483.3 2223.91  489.532220.946
   495.4 2219.27   527.6 2217.73   539.4 2220.02   555.5 2220.91   621.7 2222.78
   665.6 2226.08   695.8 2231.76   725.6 2233.81   780.3  2245.3   836.7 2254.02
   879.9 2256.12   890.7  2262.3   901.1    2265   923.7 2267.34  1004.2  2271.8
#Mann= 12 ,-1,0
       0     .05       0     100     .06       0  173.05      .1       0
  466.64     .05       0  489.53    .045       0   555.5     .05       0
  563.89     .07       0  666.42     .08       0  704.33     .05       0
  821.57     .07       0  832.11     .08       0  952.11     .07       0
#XS Ineff= 2 , 0
          471.34 2255.77
Permanent Ineff=
       F       F
Bank Sta=489.53,555.5
XS Rating Curve= 0 ,0
Exp/Cntr(USF)=0,0
Exp/Cntr=0.3,0.1

Type RM Length L Ch R = 1 ,42766   ,543.9,576.1,613.3
XS GIS Cut Line= 6
 2259229.1423292684545.8803683932259283.18129251684645.591249482
2259367.82974263 684682.280216652259703.23574044 684705.84997618
2259825.60750471684663.1521120772260044.85666904684434.004694412
#Sta/Elev= 30
       0 2258.59    25.3  2252.3    44.7 2249.66      72 2242.68     102 2230.54
   112.9 2227.79   258.8 2227.35   300.1 2226.35   376.4  2226.8   425.6 2228.31
   433.9 2227.27457.70562221.438   477.7  2218.5   497.8 2217.79   509.8 2219.66
514.93552221.389   521.8 2224.47   541.8 2229.12   611.4 2235.44   660.3 2237.95
   675.7 2241.34   730.9  2241.7   816.9 2247.88   832.3 2248.11   843.1 2246.88
   848.5 2247.87   864.7 2255.08   897.1 2262.55   936.8 2268.87   995.2 2272.58
#Mann= 11 ,-1,0
       0     .05       0      20     .06       0  133.41      .1       0
  153.41     .07       0457.7056    .045       0514.9355     .07       0
  647.43     .05       0  685.34     .08       0  781.56     .07       0
  923.12     .05       0  963.12     .07       0
Bank Sta=457.7056,514.9355
XS Rating Curve= 0 ,0
Exp/Cntr(USF)=0,0
Exp/Cntr=0.3,0.1

Type RM Length L Ch R = 1 ,42190   ,250.5,250.6,250.4
XS GIS Cut Line= 4
2259132.65438983684476.3728657892259128.24519663684673.684261347
2259239.57732485684900.7577109842259407.12666633684959.179520842
#Sta/Elev= 30
       0 2263.03    48.8 2260.09    76.8 2257.33   120.8 2247.03   140.8 2244.43
   160.8  2242.7   164.8 2240.72   168.8 2236.21   172.8 2233.81   197.4 2234.91
   219.1  2233.4   223.5 2232.46   229.8 2229.94   235.8    2226   242.6 2220.55
   245.8 2219.16   268.1 2217.41   288.1 2220.55   299.3 2221.72   308.2 2221.14
   361.6 2221.72   406.2 2221.28   428.5 2223.47   449.9 2228.27   469.9 2230.06
   501.7 2234.58   514.4  2235.7   539.9 2236.46   592.4 2243.62   627.7 2247.26
#Mann= 7 ,-1,0
       0     .05       0      90     .07       0     190      .1       0
   242.6    .045       0   288.1      .1       0  407.36     .05       0
  520.26     .06       0
Bank Sta=242.6,288.1
XS Rating Curve= 0 ,0
Exp/Cntr(USF)=0,0
Exp/Cntr=0.3,0.1

Type RM Length L Ch R = 1 ,41940   ,295.1,277.4,264.5
XS GIS Cut Line= 4
2258917.67766018684522.9134534922258872.76921095684721.599319769
2259031.49749875685044.8103415682259184.44126529 685035.55216537
#Sta/Elev= 30
       0 2254.58    10.5 2252.68    18.7 2248.57    55.6 2245.74    63.8 2240.99
    76.1  2235.4    80.2 2234.21   100.7 2231.88     113    2231   145.9 2230.41
   212.1 2224.62   243.3 2221.16   261.2 2221.83   305.7 2221.09   310.5 2220.81
   316.5 2219.45   323.6 2217.55     328 2217.29   350.3 2217.34   359.2 2218.04
   363.7 2219.49   370.3 2219.87   385.2 2219.39   409.2 2220.06   452.8 2222.32
   513.8  2224.4   592.5 2225.76   620.8 2228.03   684.3 2236.68     717 2238.84
#Mann= 5 ,-1,0
       0     .07       0     140      .1       0   316.5    .045       0
   363.7      .1       0   463.7     .05       0
Bank Sta=316.5,363.7
XS Rating Curve= 0 ,0
Exp/Cntr(USF)=0,0
Exp/Cntr=0.3,0.1

Type RM Length L Ch R = 1 ,41662   ,53.9,59.3,54.1
XS GIS Cut Line= 5
2258414.58024904684573.3955386282258441.33820957684755.596629101
2258654.68749423684941.4636330272258725.83450997685004.797777925
2259120.80150724685064.651114181
#Sta/Elev= 30
       0 2244.08    11.9 2245.66    40.2 2244.84    56.4 2242.26   141.3 2238.47
   149.4 2236.47   157.5 2230.96   161.5 2229.26   177.5 2225.45   198.6 2223.33
   210.9 2223.55   241.4 2220.79   275.2 2221.44   299.3 2218.74   309.9  2218.4
   377.2 2219.49   414.1 2219.23   437.3 2217.88   462.3 2218.04   478.7 2216.98
   496.3 2216.94     528 2216.94  542.392218.028   561.5 2218.94   609.2 2218.78
   671.7 2222.12   706.3 2222.91   892.4 2225.55   920.8 2227.15   961.8 2231.75
#Mann= 7 ,-1,0
       0     .07       0      90      .1       0   462.3    .045       0
  542.39      .1       0  752.36     .05       0  882.36      .1       0
  952.36     .05       0
Bank Sta=462.3,542.39
XS Rating Curve= 0 ,0
Exp/Cntr(USF)=0,0
Exp/Cntr=0.3,0.1

Type RM Length L Ch R = 1 ,41603   ,198.2,199.4,230.2
XS GIS Cut Line= 5
2258376.00862696684611.1635852542258402.76658748684793.364675727
2258616.11587214684979.2316796532258681.57357362 685037.34258406
2259111.99193923685076.625380605
#Sta/Elev= 30
       0 2245.58    46.5 2243.75      95 2238.41   103.1 2236.99   131.4 2227.38
   167.6  2225.1     186 2221.74   208.2 2219.88   232.6 2219.05   311.8 2218.67
     375 2220.48     392  2218.1   415.3 2216.95   430.1 2217.22   451.8 2219.85
   457.9 2219.94   465.7 2218.69   474.2  2216.7   482.7 2216.47   542.2 2216.53
   548.4 2218.59   550.7  2219.3   569.3 2220.03   585.4 2223.14   597.4 2224.19
   625.5 2222.11   685.7 2223.19   786.2 2223.13   930.8 2225.46   986.8 2229.38
#Mann= 7 ,-1,0
       0     .07       0      50     .06       0     150     .07       0
  204.16      .1       0   465.7    .045       0   548.4      .1       0
  984.64     .05       0
Bank Sta=465.7,548.4
XS Rating Curve= 0 ,0
Exp/Cntr(USF)=0,0
Exp/Cntr=0.3,0.1

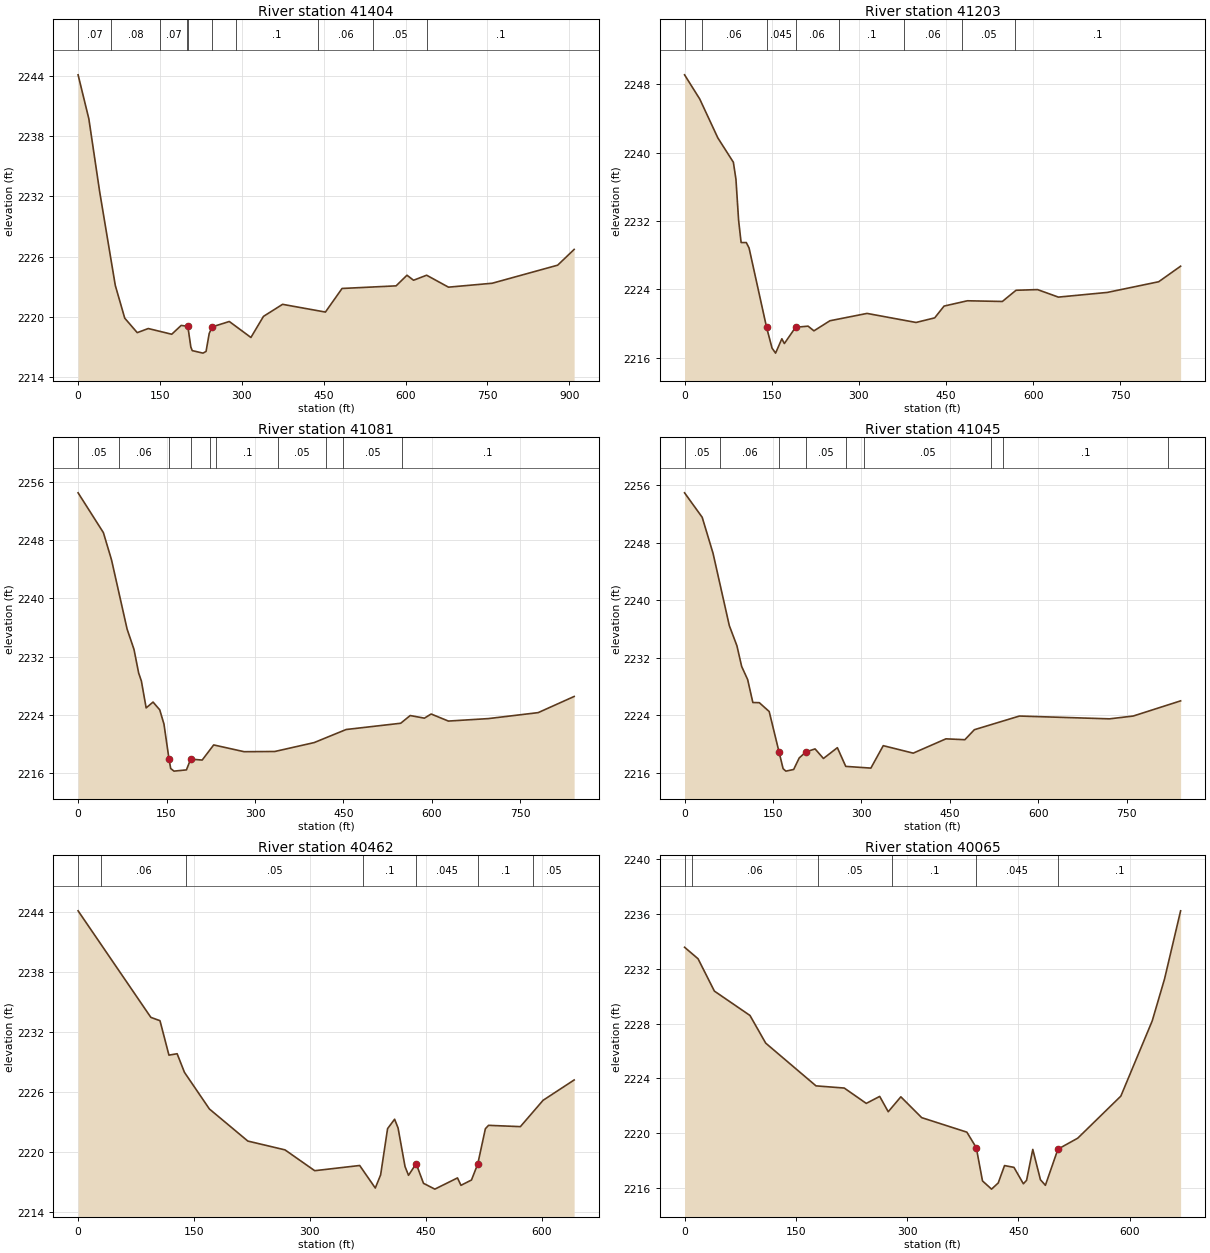
Type RM Length L Ch R = 1 ,41404   ,221,201,164.5
XS GIS Cut Line= 3
2258280.65957033684848.8693777182258517.21278534685092.697761503
2259086.43962705685082.556617151
#Sta/Elev= 30
       0  2244.1    19.7 2239.72    39.5 2232.47    68.2 2223.12    85.5 2219.86
   108.4 2218.42   128.6 2218.83   171.6 2218.26   188.9 2219.14   201.1 2219.05
   206.6 2216.99   209.2 2216.63   228.9 2216.38   234.5 2216.55   240.3 2218.35
     246    2219   277.1 2219.53   316.7 2217.94   339.7 2220.04   374.7 2221.24
   453.2 2220.47   483.7 2222.82   582.7 2223.08   602.7 2224.14   614.7 2223.64
   638.7 2224.14   678.7 2222.95   758.8 2223.34   878.8 2225.14     909 2226.71
#Mann= 10 ,-1,0
       0     .07       0      60     .08       0     150     .07       0
     200     .08       0   201.1    .045       0     246     .08       0
     290      .1       0  439.72     .06       0  539.72     .05       0
  639.72      .1       0
Bank Sta=201.1,246
XS Rating Curve= 0 ,0
Exp/Cntr(USF)=0,0
Exp/Cntr=0.3,0.1

Type RM Length L Ch R = 1 ,41203   ,126.4,121.9,110
XS GIS Cut Line= 4
2258268.73081449685258.1518312282258372.32352999685207.505324929
2258540.06547923 685135.528563392259093.75835546685088.589611781
#Sta/Elev= 30
       0 2249.12    26.1 2246.29    57.3 2241.73      84 2238.88    88.4  2236.9
      93 2232.08    97.3 2229.48   106.2 2229.48     111 2228.84   141.1 2219.56
   150.5 2217.12   156.6 2216.53   167.4 2218.21   171.7 2217.65  191.012219.555
   212.5 2219.69   222.6 2219.14   250.1 2220.32     314 2221.18   398.3 2220.12
   430.4 2220.66   446.5 2222.04   486.6 2222.66   546.8 2222.58   570.3 2223.89
   607.3 2223.97   643.2 2223.09   727.5 2223.64   815.8 2224.89   853.5 2226.71
#Mann= 8 ,-1,0
       0     .05       0      30     .06       0   141.1    .045       0
  191.01     .06       0  265.31      .1       0  377.84     .06       0
  477.84     .05       0  567.84      .1       0
Bank Sta=141.1,191.01
XS Rating Curve= 0 ,0
Exp/Cntr(USF)=0,0
Exp/Cntr=0.3,0.1

Type RM Length L Ch R = 1 ,41081   ,37.2,36.3,40
XS GIS Cut Line= 6
2258338.90935533685381.2632788952258448.99919337685318.584393005
 2258510.8745038685256.7090825762258650.69663386685166.708631042
2258701.32188785685136.1727635572259100.87746385685096.708279849
#Sta/Elev= 30
       0 2254.51    42.9 2249.04    56.7 2245.29    83.1 2235.78    94.8 2232.99
   102.7 2229.74   107.3 2228.65   115.4 2224.95   127.1 2225.75   138.4 2224.69
   145.6 2222.73  154.032217.994     157 2216.62   162.6 2216.26   183.7 2216.43
   190.9 2217.91   210.4 2217.78   229.9 2219.86   281.5 2218.93   333.6 2218.96
   400.2 2220.18   454.5 2221.98     547 2222.84   563.1  2223.9   587.2 2223.54
   598.6 2224.11   627.9 2223.14   695.7 2223.48   780.1  2224.3   841.1 2226.52
#Mann= 10 ,-1,0
       0     .05       0      70     .06       0  154.03    .045       0
   190.9     .06       0  224.19     .05       0  234.19      .1       0
  339.64     .05       0  420.48     .06       0  449.61     .05       0
  549.61      .1       0
Bank Sta=154.03,190.9
XS Rating Curve= 0 ,0
Exp/Cntr(USF)=0,0
Exp/Cntr=0.3,0.1

Type RM Length L Ch R = 1 ,41045   ,573.1,582.5,579.9
XS GIS Cut Line= 6
2258366.19803859685405.0928332872258476.28787663685342.413947398
2258538.16318705685280.5386369682258677.98531712685190.538185435
 2258728.6105711 685160.002317952259128.16614711685120.537834242
#Sta/Elev= 30
       0 2254.94    29.9 2251.54    48.3 2246.53    75.9 2236.47    88.8 2233.67
    96.8  2230.8     107 2228.97   115.8 2225.78   126.7 2225.76   143.5 2224.53
  160.092218.946   167.1 2216.58   171.8 2216.24     185 2216.47   194.4 2218.07
   205.7 2218.91   221.3 2219.33   235.5    2218   259.1  2219.5   273.3  2216.9
   315.9 2216.66   336.9 2219.78   387.7 2218.74   443.2 2220.73   475.3 2220.61
   491.4    2222   567.8  2223.9   720.5 2223.51   760.7  2223.9   841.1 2226.01
#Mann= 9 ,-1,0
       0     .05       0      60     .06       0  160.09    .045       0
   205.7     .05       0  274.19      .1       0  304.19     .05       0
  519.61     .06       0  539.61      .1       0  819.61     .05       0
Bank Sta=160.09,205.7
XS Rating Curve= 0 ,0
Exp/Cntr(USF)=0,0
Exp/Cntr=0.3,0.1

Type RM Length L Ch R = 1 ,40462   ,368.1,396.6,357.1
XS GIS Cut Line= 4
2258832.48506598 685660.318402882258914.11834382685536.014616624
2259125.51337003685135.117855478 2259162.4819368685119.389652035
#Sta/Elev= 30
       0  2244.1    94.2 2233.46     106 2233.13   117.6 2229.69   128.2 2229.83
   137.7 2227.97     170 2224.31   219.7 2221.11   267.8 2220.23   306.3 2218.15
   364.5 2218.67   384.7 2216.42   391.6 2217.73   400.6 2222.35   409.7 2223.29
   414.2 2222.41   423.2 2218.56   427.7 2217.69   437.6 2218.85   447.1 2216.89
   461.8 2216.31   491.1 2217.43   495.6 2216.69   509.2 2217.22  517.332218.818
   527.2 2222.34   531.3 2222.68   572.5 2222.55   601.9 2225.18   642.1 2227.21
#Mann= 7 ,-1,0
       0     .05       0      30     .06       0     140     .05       0
  368.71      .1       0   437.6    .045       0  517.33      .1       0
  588.71     .05       0
Bank Sta=437.6,517.33
XS Rating Curve= 0 ,0
Exp/Cntr=0.3,0.1

Type RM Length L Ch R = 1 ,40065   ,344.1,349.6,336
XS GIS Cut Line= 3
2259200.27469856685808.464717067 2259406.7677897  685217.1346028
2259418.25694445685176.311997579
#Sta/Elev= 30
       0 2233.57    18.2 2232.73    40.2 2230.37    88.2 2228.59   109.4 2226.57
   177.2 2223.45   215.3 2223.29     245 2222.17   263.1 2222.68   274.6 2221.56
   291.6 2222.65   319.7 2221.13   380.6 2220.07   393.3 2218.94   401.7 2216.51
   413.9 2215.91   422.9 2216.36   431.4 2217.63   444.1  2217.5   456.8  2216.3
   461.1 2216.55   469.5 2218.81   479.8  2216.6   486.5 2216.19   503.4 2218.83
   530.1 2219.63   588.2  2222.7   630.5 2228.19   647.1 2231.25   668.8 2236.23
#Mann= 6 ,-1,0
       0      .1       0      10     .06       0     180     .05       0
     280      .1       0   393.3    .045       0   503.4      .1       0
Bank Sta=393.3,503.4
XS Rating Curve= 0 ,0
Exp/Cntr=0.3,0.1

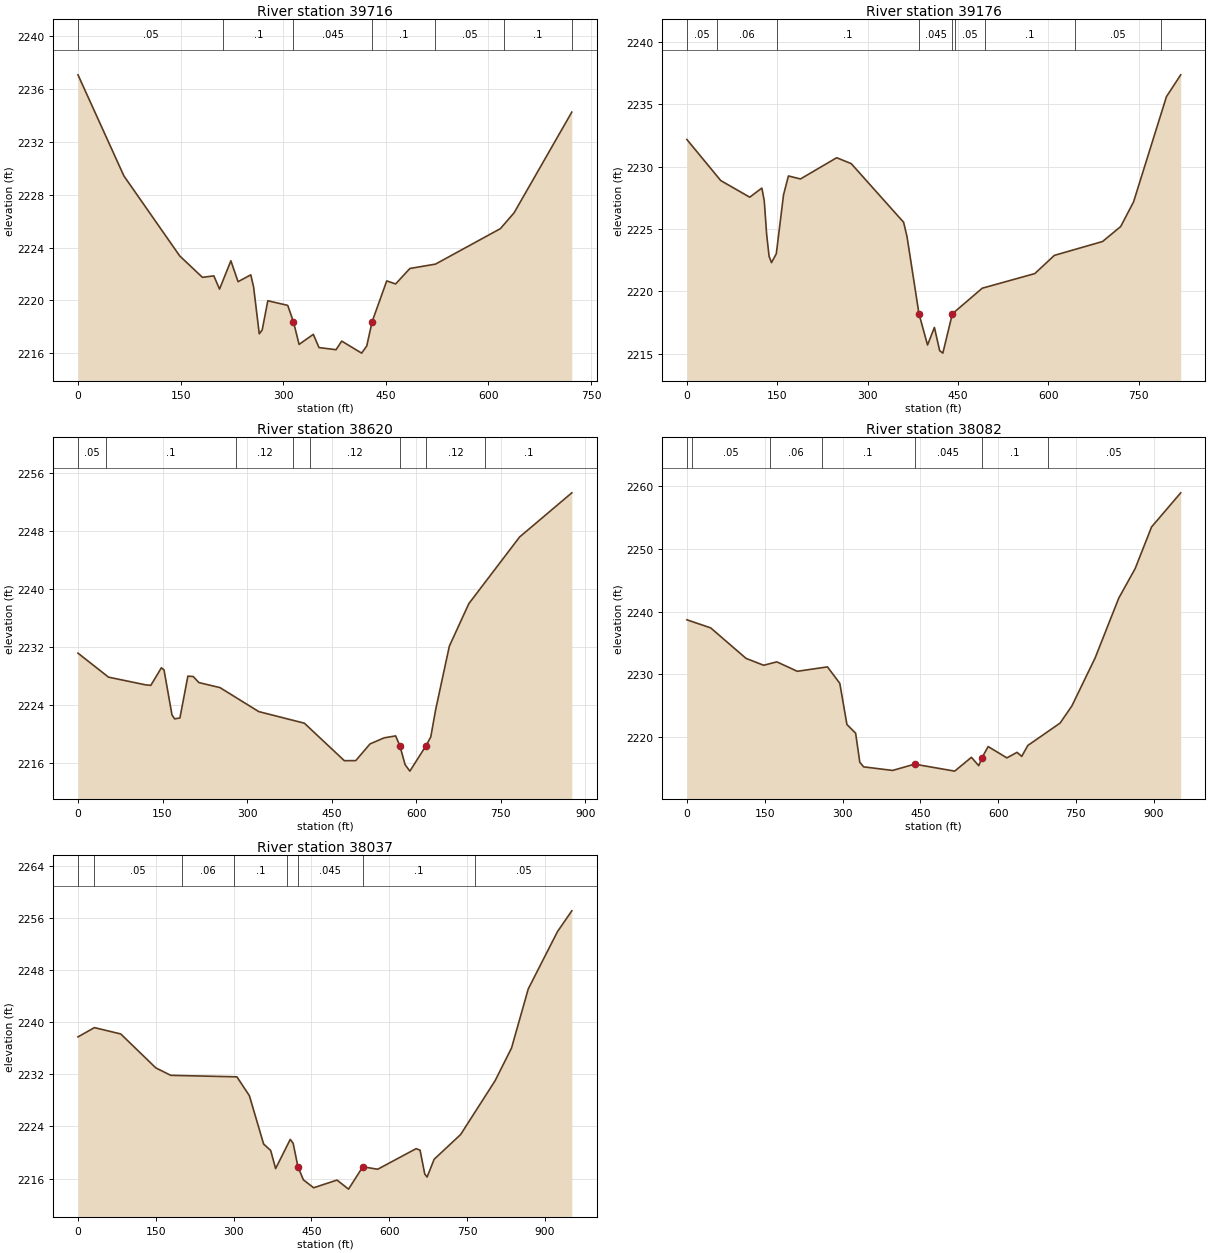
Type RM Length L Ch R = 1 ,39716   ,570.5,539.3,472.5
XS GIS Cut Line= 4
 2259492.2348332685935.4960295812259547.90632511685826.510754659
2259674.97503636685374.2436853312259662.01478814685245.213182926
#Sta/Elev= 30
       0 2237.06    67.1 2229.42   148.7 2223.37   181.9 2221.75   198.6 2221.86
   206.9 2220.86   223.5    2223     234 2221.42   252.6 2221.94   256.7 2221.02
     265 2217.48   269.2 2217.76   277.5 2219.98   306.6 2219.63   314.9  2218.4
   323.2 2216.68     344 2217.44   352.3 2216.44   377.2 2216.28   385.5 2216.93
   414.6 2216.02   422.1 2216.56  429.96  2218.4   451.3 2221.48   464.3 2221.25
   485.2 2222.42   522.6 2222.75   617.4 2225.43   637.5 2226.63   721.8 2234.24
#Mann= 7 ,-1,0
       0     .05       0  212.38      .1       0   314.9    .045       0
  429.96      .1       0  522.38     .05       0  622.16      .1       0
  721.84     .05       0
Bank Sta=314.9,429.96
XS Rating Curve= 0 ,0
Exp/Cntr=0.3,0.1

Type RM Length L Ch R = 1 ,39176   ,532.1,556.1,605.3
XS GIS Cut Line= 4
2260039.96574445685881.3148299082260061.35840953685537.654274688
2259770.87142896685289.5038380172259703.89347493685224.721092033
#Sta/Elev= 30
       0 2232.17    56.2 2228.88   104.3 2227.55   124.4 2228.28   128.4 2227.26
   132.4 2224.56   136.4 2222.82   140.4 2222.31   148.4 2223.02   160.4 2227.74
   168.5 2229.25   188.5 2229.01   248.6 2230.71   272.7 2230.24   359.7 2225.54
   365.4 2224.38   385.2 2218.21   399.4 2215.71   410.8 2217.12   419.5 2215.26
   424.8 2215.06   440.6 2218.21   490.2 2220.26   577.4 2221.43   609.9 2222.89
   689.9    2224     720  2225.2   741.3 2227.17   795.9  2235.6   819.6 2237.35
#Mann= 9 ,-1,0
       0     .05       0      50     .06       0     150      .1       0
   385.2    .045       0   440.6      .1       0  444.33     .05       0
  494.33      .1       0  644.33     .05       0  786.37     .08       0
Bank Sta=385.2,440.6
XS Rating Curve= 0 ,0
Exp/Cntr=0.3,0.1

Type RM Length L Ch R = 1 ,38620   ,488.8,538.2,615.7
XS GIS Cut Line= 4
 2260079.7893091685879.1883753062260221.60021914685648.679761744
2260454.77993379685347.4865869442260553.26258629685145.979589637
#Sta/Elev= 30
       0 2231.15    54.2 2227.84   119.8 2226.78   129.2 2226.71   147.9 2229.13
   152.6 2228.84   166.7 2222.64   171.4 2222.09   180.8 2222.21   194.9 2227.98
   204.3 2227.93   214.5 2227.09   251.8  2226.4   320.6 2223.09   401.5 2221.49
   472.4 2216.32   492.6 2216.33   517.9 2218.63     543 2219.47   563.4 2219.74
   570.92218.367   580.1 2215.78   588.6 2214.88   617.1 2218.37   625.7  2219.6
   634.2 2223.31   658.6 2232.11   693.2 2237.98   783.2 2247.17   875.8 2253.26
#Mann= 8 ,-1,0
       0     .05       0      50      .1       0  280.64     .12       0
  380.64      .1       0  410.64     .12       0   570.9    .045       0
   617.1     .12       0  721.54      .1       0
Bank Sta=570.9,617.1
XS Rating Curve= 0 ,0
Exp/Cntr=0.3,0.1

Type RM Length L Ch R = 1 ,38082   ,35.3,45.4,33.3
XS GIS Cut Line= 6
2260381.75260463686085.1213856132260488.98251387 685769.58340626
2260541.17787395685798.0536026672260611.82613911685849.194511028
2260738.62818964685955.4347530442261009.86183929685812.643749197
#Sta/Elev= 30
       0  2238.7    45.9 2237.41   114.1 2232.55     148 2231.46   173.4    2232
   212.8  2230.5     271  2231.2   294.8 2228.58   308.5 2222.03   325.3 2220.64
   333.3 2216.02   340.7 2215.28   396.5 2214.71     439 2215.71   516.3  2214.6
   548.5  2216.8   562.6 2215.46   568.9 2216.76   580.8 2218.51   616.9 2216.71
   636.4 2217.59   645.5 2216.95   657.2 2218.68   719.4 2222.25   742.1 2224.97
     787 2232.63   832.6 2242.16   864.2 2246.86   895.8 2253.49     952 2258.92
#Mann= 7 ,-1,0
       0      .1       0      10     .05       0     160     .06       0
     260      .1       0     439    .045       0   568.9      .1       0
  695.47     .05       0
Bank Sta=439,568.9
XS Rating Curve= 0 ,0
Exp/Cntr=0.3,0.1

Type RM Length L Ch R = 1 ,38037   ,412.2,358.6,293.6
XS GIS Cut Line= 6
 2260374.9197575686123.1290978162260482.14966674685807.591118463
2260534.34502681 685836.061314872260604.99329197685887.202223231
2260731.79534251685993.4424652472261003.02899215  685850.6514614
#Sta/Elev= 30
       0 2237.75    31.7 2239.17    82.4  2238.2   150.1 2232.99   178.8 2231.85
   306.4 2231.62   330.4 2228.73   357.9 2221.31   371.5 2220.32     381 2217.54
   409.2 2222.02   414.8 2221.42     4242217.843   434.5 2215.82   454.3  2214.6
   499.4 2215.78   521.6 2214.39   549.1 2217.82   577.8 2217.44   651.9  2220.6
   659.5 2220.36   668.5 2216.71     673 2216.24   686.6 2218.97   737.7 2222.77
   804.1 2231.02   835.8 2236.04     868  2245.1   924.3 2253.89     952 2257.09
#Mann= 8 ,-1,0
       0      .1       0      30     .05       0     200     .06       0
  300.96      .1       0  402.77     .05       0     424    .045       0
   549.1      .1       0  765.47     .05       0
Bank Sta=424,549.1
XS Rating Curve= 0 ,0
Exp/Cntr=0.3,0.1