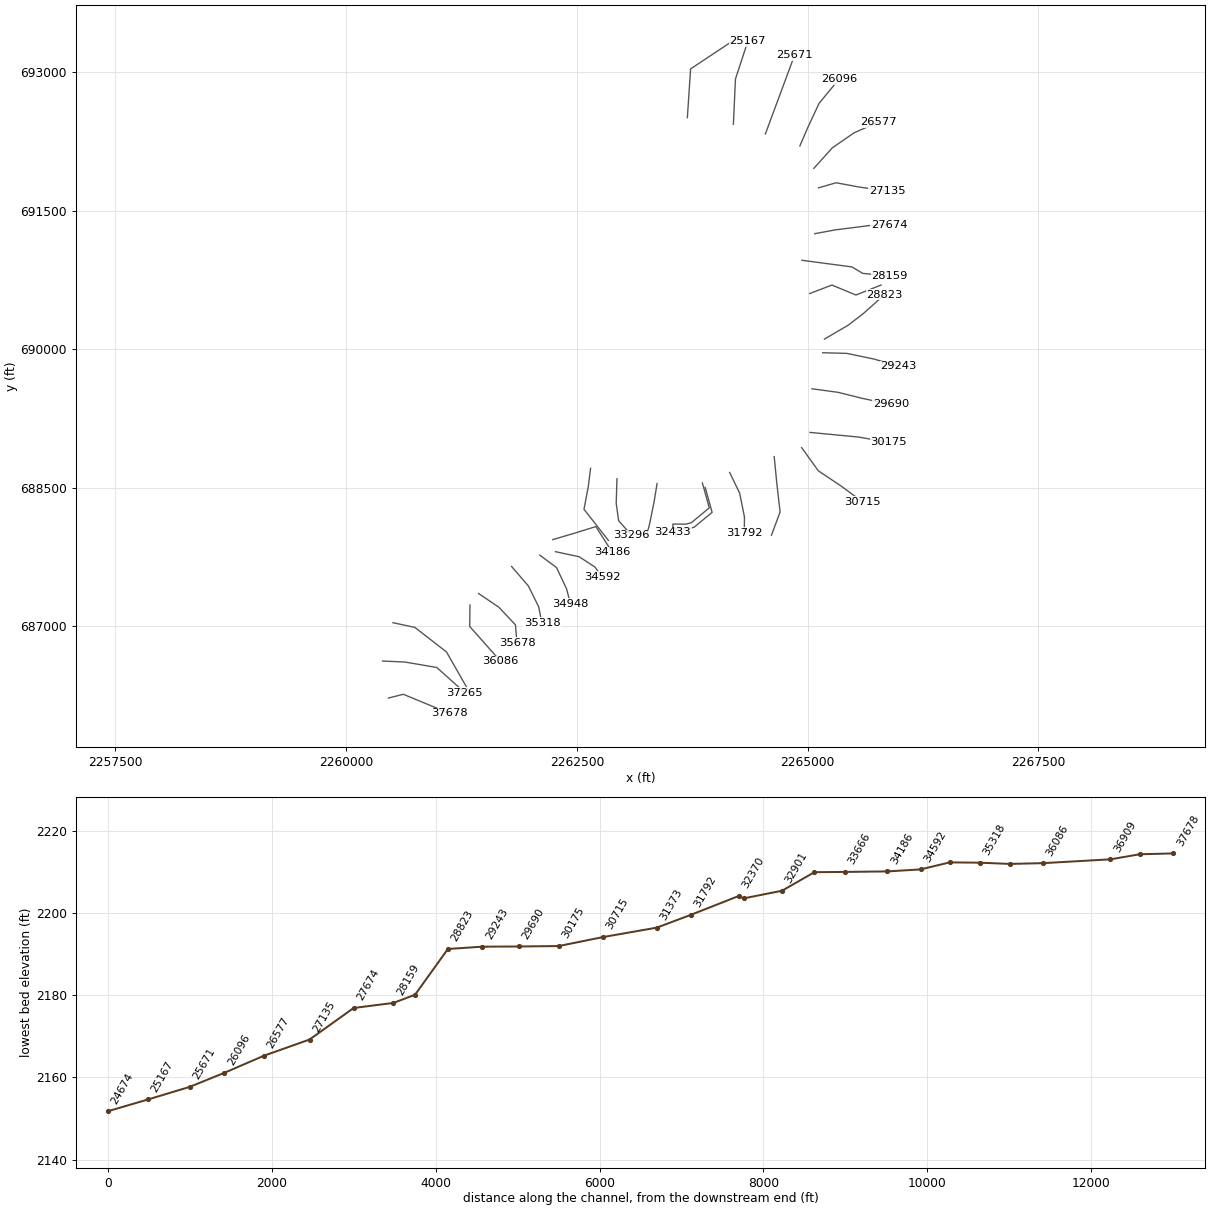
HEC-RAS study ROARCK.prj: ROARCK

--- ROARCK.g01 (geometry) --- (continued)

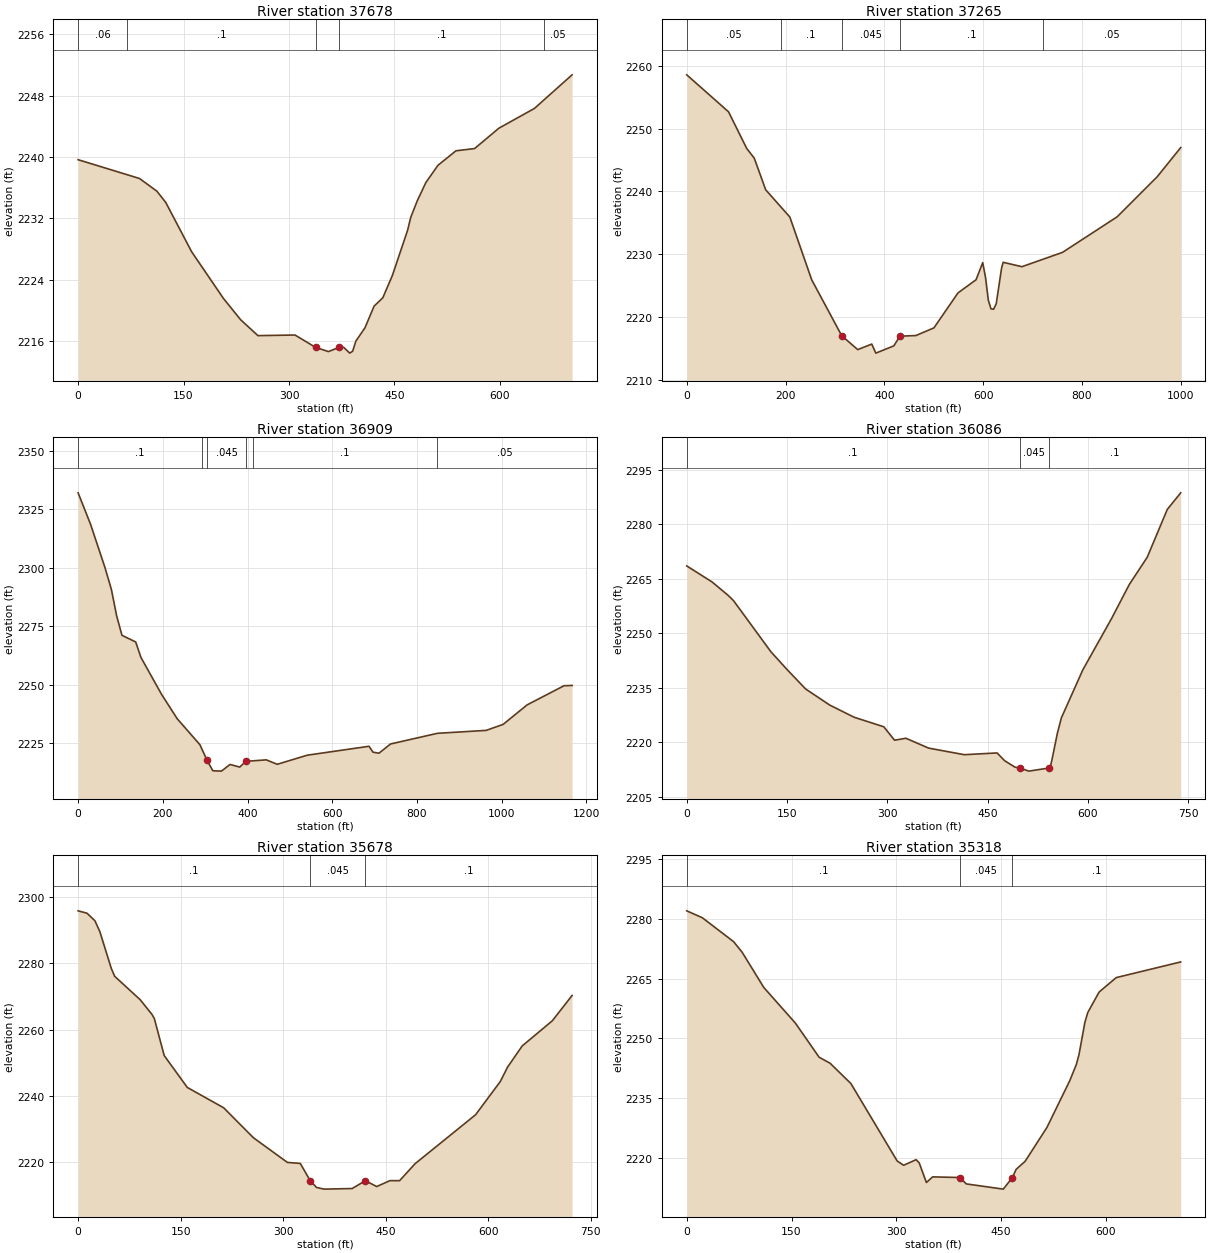
Type RM Length L Ch R = 1 ,37678   ,426.6,413.3,407.3
XS GIS Cut Line= 4
2260459.53996051686218.5345824312260620.22260006 686258.97969817
2260968.51634334686114.9121269762261115.83693632 686052.14421761
#Sta/Elev= 30
       0 2239.64    87.3 2237.19     112 2235.54   124.6 2234.08   161.5 2227.64
   206.8 2221.55   231.3 2218.77   255.8 2216.71   308.5 2216.79   337.8 2215.18
   356.1 2214.63371.35912215.188   377.7 2215.19   386.4 2214.43   390.6 2214.69
   395.1    2216     408 2217.72     421 2220.55   433.4 2221.64     447 2224.54
   468.7 2230.44   473.2 2232.13   482.4 2234.27   494.6 2236.65   511.9 2238.91
   537.5  2240.8     564 2241.09   598.5 2243.74   649.1 2246.32   702.7  2250.7
#Mann= 5 ,-1,0
       0     .06       0      70      .1       0   337.8    .045       0
371.3591      .1       0  662.61     .05       0
Bank Sta=337.8,371.3591
XS Rating Curve= 0 ,0
Exp/Cntr=0.3,0.1

Type RM Length L Ch R = 1 ,37265   ,369.6,355.7,324.4
XS GIS Cut Line= 4
2260395.67838674686619.4493127912260636.19985942686608.815619807
 2260982.2701304686549.6753875442261286.42419337686277.536386744
#Sta/Elev= 30
       0 2258.56    84.6 2252.67   121.5 2246.82   136.6  2245.3   159.9 2240.24
   208.7 2235.91   252.9 2225.92   313.8 2216.99   346.2 2214.78   374.6 2215.66
   382.8 2214.22   419.3 2215.38   431.5 2216.92   463.9 2217.02   500.4 2218.24
   549.1 2223.81   585.7 2225.91   599.2 2228.64   604.9 2226.27   610.5 2222.68
   615.9 2221.28   621.2 2221.21   626.6  2222.1   637.3 2227.73   640.6 2228.69
   678.5 2227.99   760.7 2230.27   871.2 2235.93   952.5 2242.33    1000 2246.97
#Mann= 5 ,-1,0
       0     .05       0     190      .1       0   313.8    .045       0
   431.5      .1       0  721.84     .05       0
Bank Sta=313.8,431.5
XS Rating Curve= 0 ,0
Exp/Cntr=0.3,0.1

Type RM Length L Ch R = 1 ,36909   ,828.2,823,761.2
XS GIS Cut Line= 4
 2260507.1798751 687035.003200492260744.87972413686984.360441618
2261087.45968884686718.067915945     2261330.029      686292.911
#Sta/Elev= 30
       0 2331.93    29.6 2318.38    63.1 2300.18    78.7 2290.55      91 2279.37
   103.5 2271.04     136 2268.19   148.2 2261.63   197.3 2245.72   234.1 2235.36
   287.6 2224.28   304.7 2217.54   318.1 2213.15   338.4 2212.99   358.7 2215.84
   381.6 2214.71   395.9 2217.16   444.3 2217.81   470.1 2215.91   541.1  2219.8
   686.9 2223.61   696.4 2221.08   710.4 2220.66   737.8  2224.6   848.4 2229.15
   963.5  2230.4  1003.6 2232.97  1060.2  2241.3  1147.3 2249.48  1166.4 2249.61
#Mann= 6 ,-1,0
       0      .1       0  293.03     .12       0   304.7    .045       0
   395.9     .12       0  413.03      .1       0  846.94     .05       0
Bank Sta=304.7,395.9
XS Rating Curve= 0 ,0
Exp/Cntr=0.3,0.1

Type RM Length L Ch R = 1 ,36086   ,407.3,407.7,398.9
XS GIS Cut Line= 3
2261341.89231269687227.0933316952261339.00736941686994.318251644
2261674.98208973686615.712254766
#Sta/Elev= 30
       0  2268.5    37.9 2264.09    61.9 2260.41    69.9 2258.97   125.9  2244.9
   149.9 2240.04   177.9 2234.65   213.9 2230.23   250.4 2226.88   294.8 2224.26
   310.9 2220.56   327.9  2221.1   361.9 2218.39   415.3 2216.58   464.3 2217.06
   475.6 2214.92     491 2213.16   497.9 2212.93   511.8 2212.06  542.172212.921
   544.5 2213.74   546.1 2214.93   554.6 2222.57   560.5 2226.72   592.6 2239.93
   635.4 2253.97   662.1 2263.39   688.9 2270.88   718.9 2284.03     739  2288.6
#Mann= 3 ,-1,0
       0      .1       0   497.9    .045       0  542.17      .1       0
Bank Sta=497.9,542.17
XS Rating Curve= 0 ,0
Exp/Cntr=0.3,0.1

Type RM Length L Ch R = 1 ,35678   ,371.5,360.5,347.7
XS GIS Cut Line= 4
2261435.85058295687350.9686192512261653.12872198687204.041536302
2261834.26434685687012.091583785 2261850.8944407686816.491159561
#Sta/Elev= 30
       0 2295.85      13 2295.13    24.5 2292.88    31.8 2289.57    48.7 2278.37
    53.5 2276.09    90.8 2269.03   108.1 2264.57   111.5 2263.33   125.9 2252.19
   159.7 2242.56   212.9 2236.42   256.3  2227.4   306.1 2219.94     325 2219.63
  339.392214.439   348.7 2212.39   359.8 2211.88   400.8 2212.06   420.2 2214.42
   436.7 2212.66   456.1 2214.44   470.2 2214.43   492.8 2219.54   581.3 2234.31
   617.5 2244.35   628.2 2248.72   649.6  2255.1   693.5 2262.66   722.5 2270.31
#Mann= 3 ,-1,0
       0      .1       0  339.39    .045       0   420.2      .1       0
Bank Sta=339.39,420.2
XS Rating Curve= 0 ,0
Exp/Cntr=0.3,0.1

Type RM Length L Ch R = 1 ,35318   ,368.4,370,373.6
XS GIS Cut Line= 4
2261792.38823673687644.8000901392261974.92466537687432.766513443
2262085.57699694687208.2439027392262121.37128389687034.740006737
#Sta/Elev= 30
       0 2282.03    22.3  2280.3    67.1 2274.29    79.4 2271.62   110.3  2262.8
   155.6 2253.84   189.5 2245.29   205.3 2243.76     235 2238.68   301.3 2219.23
   310.5 2218.16   328.4 2219.56   332.8 2218.77   343.1 2213.83   352.1 2215.25
   391.2 2215.08   400.2 2213.48   453.2 2212.17  466.172215.066   471.6 2217.14
   484.5 2219.16   515.7 2227.66   548.4  2239.4   557.7 2243.42   561.6 2245.95
     570 2254.03   574.1 2256.48   590.4 2261.65   614.9 2265.27   707.2  2269.2
#Mann= 3 ,-1,0
       0      .1       0   391.2    .045       0  466.17      .1       0
Bank Sta=391.2,466.17
XS Rating Curve= 0 ,0
Exp/Cntr=0.3,0.1

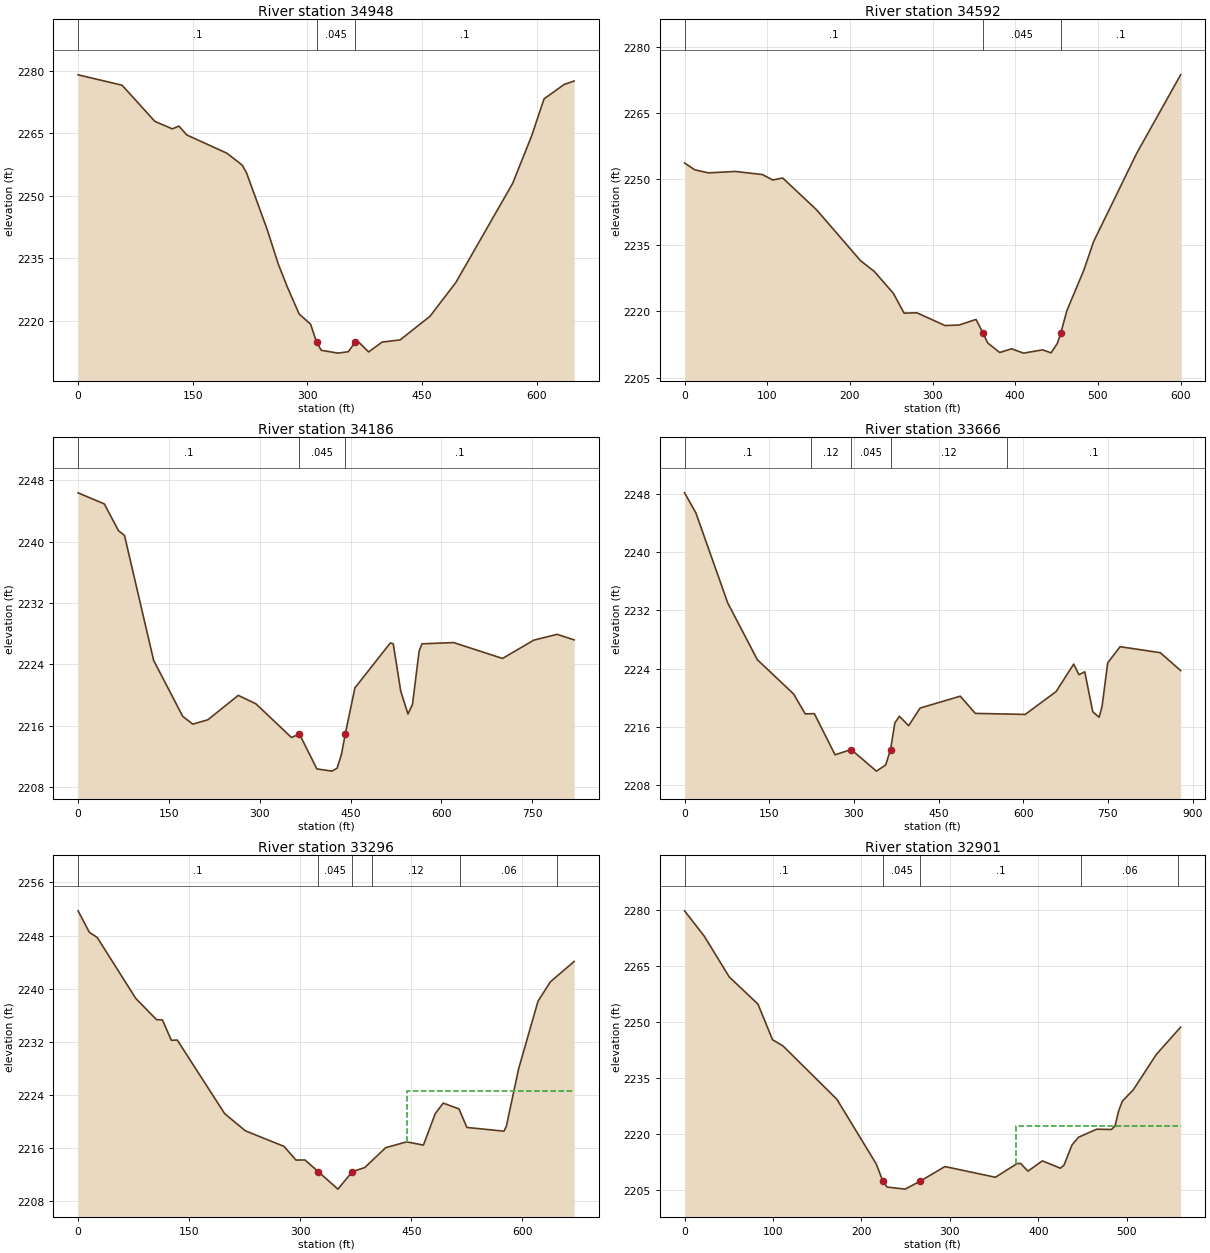
Type RM Length L Ch R = 1 ,34948   ,324.7,355.6,379.1
XS GIS Cut Line= 4
2262098.10781333687767.6323278162262279.13217297687632.714269995
2262388.27243555687402.1433833022262430.11499848687239.223970283
#Sta/Elev= 30
       0 2279.05    57.5 2276.56   100.4 2267.89   123.3 2266.08   131.9 2266.75
   142.3 2264.61   194.7 2260.24   214.8 2257.37   220.5 2255.47   247.4 2241.94
   262.2 2233.51   273.9 2228.08   289.3 2221.64   304.3 2219.18  312.172214.834
   318.2 2212.93   340.2 2212.25   353.6 2212.59   362.4 2214.82   366.9 2214.95
   380.1 2212.53   397.9 2214.91   421.4 2215.42   460.5  2221.1   494.3  2229.2
   568.6 2252.98   593.4 2264.36   609.7 2273.27     636 2276.74   649.1 2277.56
#Mann= 3 ,-1,0
       0      .1       0  312.17    .045       0   362.4      .1       0
Bank Sta=312.17,362.4
XS Rating Curve= 0 ,0
Exp/Cntr=0.3,0.1

Type RM Length L Ch R = 1 ,34592   ,362.1,406.7,441.4
XS GIS Cut Line= 4
2262268.01519721 687804.918889072262524.85565382687749.901140578
2262696.18132004687637.9491211012262773.11534977687529.776464534
#Sta/Elev= 30
       0 2253.72    12.4 2252.16    28.8 2251.47    61.5 2251.79    94.2 2251.09
   106.5 2249.86   118.8  2250.3   159.7 2243.08   212.9 2231.53   229.6 2229.08
   252.6 2224.12   265.6 2219.62     281  2219.7   315.2  2216.8   332.1 2216.92
   352.6 2218.19   361.12215.077   366.7 2212.85   381.3 2210.68   395.7 2211.53
     410 2210.54   433.2 2211.28   443.4  2210.6   450.9 2212.72  455.112215.077
   462.5 2220.18     483 2229.36   494.9 2235.89   546.8 2255.85   600.1 2273.73
#Mann= 3 ,-1,0
       0      .1       0   361.1    .045       0  455.11      .1       0
Bank Sta=361.1,455.11
XS Rating Curve= 0 ,0
Exp/Cntr=0.3,0.1

Type RM Length L Ch R = 1 ,34186   ,586.9,519.3,440.7
XS GIS Cut Line= 4
 2262238.6276578687935.5643081662262484.89470701688008.623000736
2262705.42986386688076.7764139852262884.08509839687797.518897897
#Sta/Elev= 30
       0 2246.38    43.3 2244.93    66.9 2241.42    76.6 2240.83   124.8  2224.5
   172.7 2217.21   189.4 2216.18   214.4 2216.76   264.5 2219.94   293.8 2218.83
   352.4 2214.44   365.5  2214.9   394.3 2210.34   419.4 2210.05   427.8 2210.44
   434.9 2212.23  441.272214.914   457.1 2220.91   515.7 2226.79   520.5 2226.66
   532.8  2220.5   544.8  2217.5   552.2 2218.75   563.2 2225.71   567.9 2226.67
   620.2 2226.83   700.9 2224.76   752.6 2227.15   791.1 2227.91   819.2 2227.18
#Mann= 3 ,-1,0
       0      .1       0   365.5    .045       0  441.27      .1       0
Bank Sta=365.5,441.27
XS Rating Curve= 0 ,0
Exp/Cntr=0.3,0.1

Type RM Length L Ch R = 1 ,33666   ,372.3,369.8,378.8
XS GIS Cut Line= 4
2262648.39098767688709.0722758142262623.00205081688507.192208854
 2262576.8397242688264.4614111982262841.06953547687927.574135581
#Sta/Elev= 30
       0 2248.11      20 2245.37    76.5    2233   128.9 2225.22   193.4  2220.5
   213.7 2217.78   229.9 2217.82   266.6 2212.17   295.1 2212.89   339.9 2209.93
   356.2 2210.77  364.852212.879   372.5 2216.54   380.6 2217.46   396.9 2216.16
   417.2 2218.58   488.4 2220.21   515.1 2217.85   603.4 2217.71   658.1 2220.84
   689.3 2224.61   698.7 2223.16   708.9 2223.56   723.1 2218.08   734.3 2217.32
   739.4 2218.73   749.6 2224.79   771.5    2227   842.7 2226.18   878.7 2223.73
#Mann= 5 ,-1,0
       0      .1       0  223.47     .12       0   295.1    .045       0
  364.85     .12       0  570.55      .1       0
Bank Sta=295.1,364.85
XS Rating Curve= 0 ,0
Exp/Cntr=0.3,0.1

Type RM Length L Ch R = 1 ,33296   ,402.4,395.6,388
XS GIS Cut Line= 4
2262933.96442235688595.0188668842262926.00258066688328.899540798
2262952.01324662688140.9542161952263093.39585209687980.511433035
#Sta/Elev= 30
       0 2251.73    15.2  2248.5    25.9 2247.71    77.9 2238.55   105.9 2235.36
   113.9 2235.31   125.9 2232.25   133.9 2232.29   197.9 2221.22   225.9 2218.63
   278.1 2216.29   294.2 2214.23   306.3 2214.25   324.3 2212.49   350.8 2209.86
  370.322212.486   387.1 2213.11   415.4  2216.1   443.6 2216.97   466.3 2216.49
   482.3 2221.23     493  2222.8   514.3 2221.93     525 2219.14     575 2218.58
   578.3 2219.34   594.8 2227.95     621 2238.13   637.7 2241.05   669.8 2244.11
#Mann= 6 ,-1,0
       0      .1       0   324.3    .045       0  370.32      .1       0
  396.24     .12       0  515.98     .06       0  645.98      .1       0
#XS Ineff= 2 , 0
                          444.19         2224.68
Permanent Ineff=
       F       F
Bank Sta=324.3,370.32
XS Rating Curve= 0 ,0
Exp/Cntr=0.3,0.1

Type RM Length L Ch R = 1 ,32901   ,481,467.6,449.7
XS GIS Cut Line= 4
2263368.53705315688543.0764697682263336.02000985688344.253075953
2263286.99529862688102.1161743712263257.98897808687993.575181848
#Sta/Elev= 30
       0 2279.69    22.2 2272.95    50.6 2262.01      83 2254.78    99.5 2245.25
   111.4 2243.58   172.2 2229.36   216.8 2212.06  224.18 2207.49   229.1  2205.9
   249.5 2205.35  266.522207.492   294.4 2211.38   351.5 2208.52     376 2212.18
   380.1 2212.19   388.3 2210.15   404.6  2212.9     425 2210.94   429.1 2211.78
   438.1 2217.16   445.4  2219.2     466 2221.36   482.6 2221.28   486.7 2222.18
   490.9  2226.3     495 2228.83   507.5 2231.91   533.3 2241.29   560.9 2248.61
#Mann= 5 ,-1,0
       0      .1       0  224.18    .045       0  266.52      .1       0
  448.51     .06       0  558.51      .1       0
#XS Ineff= 2 , 0
                          374.91         2222.18
Permanent Ineff=
       F       F
Bank Sta=224.18,266.52
XS Rating Curve= 0 ,0
Exp/Cntr=0.3,0.1

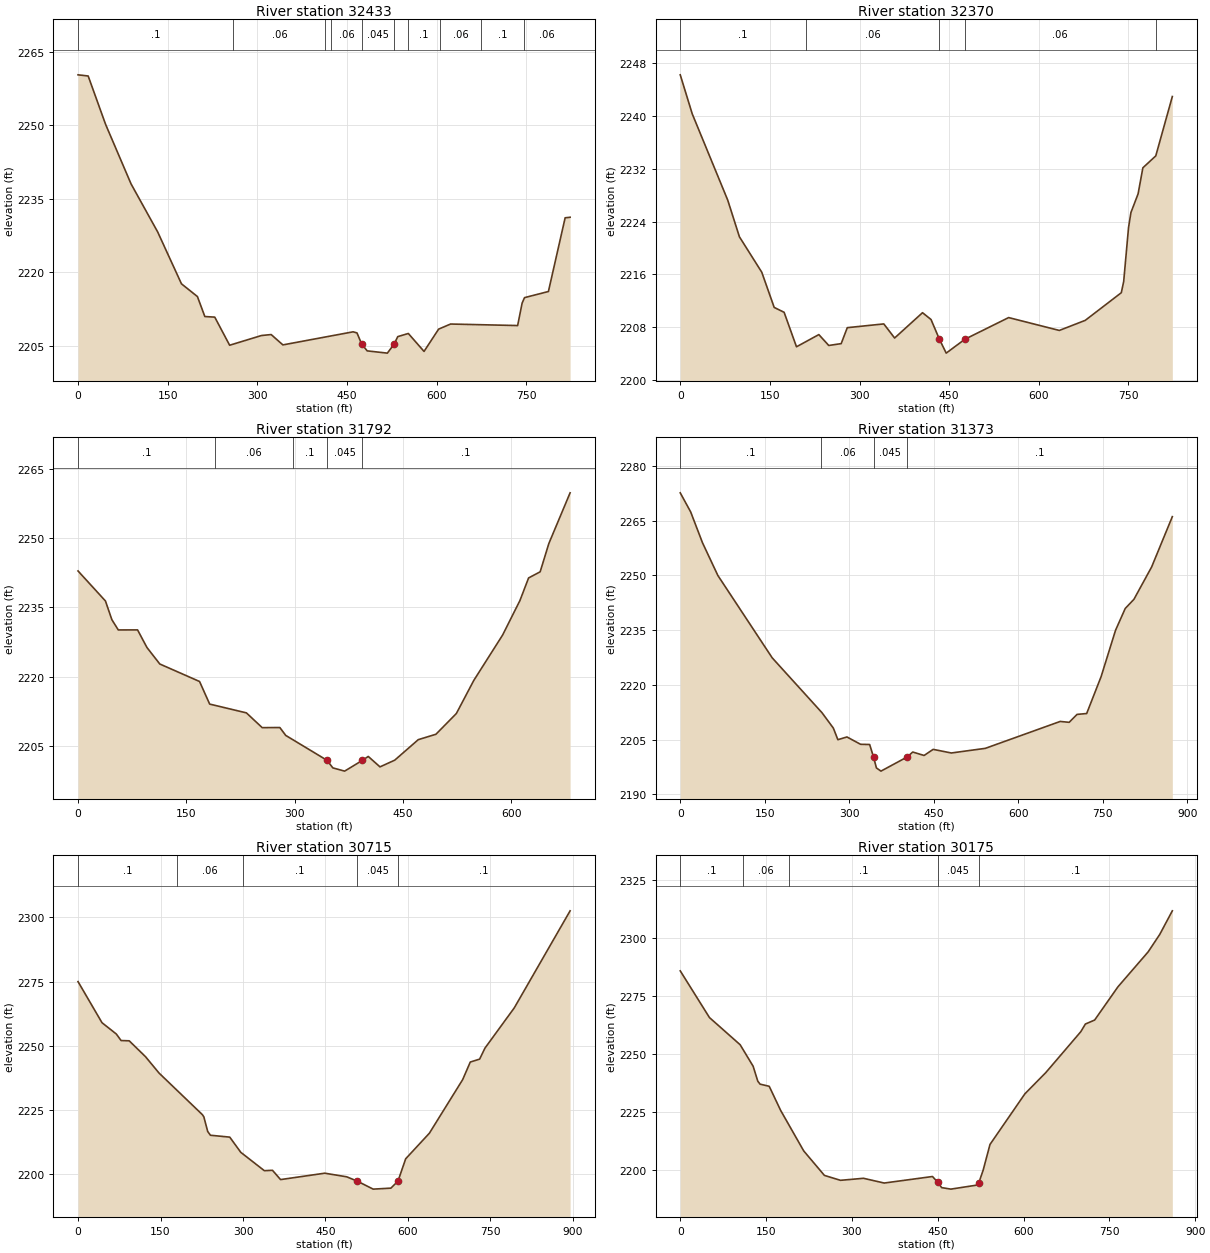
Type RM Length L Ch R = 1 ,32433   ,62.1,63.1,70.5
XS GIS Cut Line= 6
2263859.24086493688549.5719944152263934.42150614688280.378800396
2263740.45446158688119.6074580872263679.92112217688103.335055019
2263539.97845578688104.6368472652263539.27531251688016.838808867
#Sta/Elev= 30
       0 2260.32      17 2260.08    46.1 2250.22    88.7 2238.06   133.3 2228.24
   173.1 2217.65   199.8 2215.05   212.2 2210.97   228.8 2210.85   253.7 2205.11
   307.1  2207.1   323.2 2207.29   342.8 2205.18   460.3 2207.85   466.8 2207.63
  474.472205.396   483.8 2203.96   517.6  2203.5   529.1 2205.36     535 2206.87
   552.7 2207.51     579 2203.85   603.4  2208.4   623.4 2209.44   735.6 2209.13
   743.1 2213.71   747.1 2214.83   787.1 2216.08   815.1 2231.13   823.4 2231.24
#Mann= 10 ,-1,0
       0      .1       0     260     .06       0  413.76      .1       0
  423.76     .06       0  474.47    .045       0   529.1     .06       0
  552.89      .1       0  605.66     .06       0  674.48      .1       0
  745.63     .06       0
Bank Sta=474.47,529.1
XS Rating Curve= 0 ,0
Exp/Cntr=0.3,0.1

Type RM Length L Ch R = 1 ,32370   ,554.6,577.8,590.9
XS GIS Cut Line= 6
2263889.51942522688500.5375211722263964.70006643688231.344327153
2263770.73302187688070.5729848442263710.19968245688054.300581776
2263570.25701607688055.602374022 2263569.5538728687967.804335624
#Sta/Elev= 30
       0 2246.25    20.1 2240.32    79.5 2227.24      99 2221.69   136.4 2216.32
   157.2 2210.98   173.8 2210.24   194.5 2205.01   231.9 2206.86   248.5 2205.21
   269.3 2205.49   279.5 2207.91   340.6 2208.48   358.7 2206.34   405.4 2210.18
   419.6 2209.15   433.7 2206.15     445 2204.05   476.2 2206.15   549.5 2209.44
   634.3 2207.49   677.7 2209.02     738 2213.21     742 2214.91   750.1 2223.08
   754.1 2225.36   766.1  2228.2   774.1 2232.15   795.7 2233.96   823.4 2242.96
#Mann= 5 ,-1,0
       0      .1       0     210     .06       0   433.7    .045       0
   476.2     .06       0  795.63      .1       0
Bank Sta=433.7,476.2
XS Rating Curve= 0 ,0
Exp/Cntr=0.3,0.1

Type RM Length L Ch R = 1 ,31792   ,419.9,419.6,412.9
XS GIS Cut Line= 4
 2264154.8021077688663.4180810412264262.84581443688440.166039458
2264315.20139669688181.1786900632264312.94512805688011.611829745
#Sta/Elev= 30
       0 2242.85      38 2236.35    46.9  2232.3    55.8 2230.08    82.5 2230.09
    95.5 2226.28   113.3 2222.71   168.4 2218.92   182.4 2214.03   233.3 2212.13
   255.2 2208.93   279.6 2208.96   287.8 2207.25   344.9 2201.87   353.1 2200.22
   369.4 2199.52   393.9 2201.84   402.1  2202.7   418.4 2200.44   438.8 2201.89
   471.4 2206.33   495.9  2207.5   524.2 2211.99   548.3 2219.14   588.3 2228.98
   612.3 2236.45   624.3 2241.34   640.3 2242.66   652.3 2248.77   681.8 2259.76
#Mann= 5 ,-1,0
       0      .1       0     190     .06       0  298.02      .1       0
   344.9    .045       0   393.9      .1       0
Bank Sta=344.9,393.9
XS Rating Curve= 0 ,0
Exp/Cntr=0.3,0.1

Type RM Length L Ch R = 1 ,31373   ,623.9,657.7,686.5
XS GIS Cut Line= 4
2264637.19225131688835.5666894632264665.98984149 688541.63472204
2264701.11842943688234.7834122472264607.00590672687982.726417054
#Sta/Elev= 30
       0 2272.62    18.5 2267.39    39.4 2258.97    66.7 2249.99   163.2 2227.41
   251.6 2212.37   271.7 2208.16   279.7 2204.99   295.8 2205.74     320 2203.73
   336.1 2203.67  343.03 2200.23   348.1 2197.25   356.2 2196.38  402.342200.229
   412.6 2201.61   432.7 2200.67   448.8 2202.34     481 2201.35   541.4 2202.62
   674.2 2209.99   690.1 2209.75   704.1 2211.92   721.2 2212.16   746.8 2222.26
   772.4 2234.96   789.6 2240.93   805.1 2243.46   836.5 2252.32   873.2 2266.09
#Mann= 4 ,-1,0
       0      .1       0     250     .06       0  343.03    .045       0
  402.34      .1       0
Bank Sta=343.03,402.34
XS Rating Curve= 0 ,0
Exp/Cntr=0.3,0.1

Type RM Length L Ch R = 1 ,30715   ,522.1,540.3,557.9
XS GIS Cut Line= 4
2264934.76241306688932.8254820542265115.03999535688681.713277849
 2265360.9069347688517.0963531172265594.43385922688345.438068068
#Sta/Elev= 30
       0 2274.97    43.6 2258.95    69.6 2254.55    78.3    2252    93.1 2251.89
   122.7 2245.71   147.3 2239.33   226.1 2223.12   228.8 2222.26   235.8 2216.56
   240.8 2215.08   275.9 2214.35     296 2208.42   338.8 2201.27   353.6 2201.42
   368.3  2197.8   448.7 2200.29   488.6 2198.88  507.882197.183   536.7 2194.08
   568.9 2194.46   581.82197.184   595.8  2205.9   638.9 2215.87   699.4 2236.75
   713.3 2243.62   730.3 2244.76   739.9 2249.02   793.3 2264.74   894.8 2302.56
#Mann= 5 ,-1,0
       0      .1       0     180     .06       0     300      .1       0
  507.88    .045       0   581.8      .1       0
Bank Sta=507.88,581.8
XS Rating Curve= 0 ,0
Exp/Cntr=0.3,0.1

Type RM Length L Ch R = 1 ,30175   ,485.5,484.7,464.2
XS GIS Cut Line= 3
     2265025.338      689097.8042265554.99644923689047.009827413
 2265877.7891469688988.856263824
#Sta/Elev= 30
       0 2285.82    51.1 2265.71   104.7 2254.03   127.4 2244.78   135.5 2238.37
   139.5 2237.07   155.5 2236.15   175.6 2225.72   215.8 2208.35     252  2197.8
   280.1 2195.69   320.3 2196.56   356.5 2194.52   440.9 2197.33   450.32194.762
   456.9 2192.55     473  2191.9   517.2 2193.58  521.932194.694   529.3 2199.94
   541.4 2211.12   602.4 2232.91     639 2242.06     700 2259.61   708.1 2262.93
   724.3 2264.65     765 2278.94   817.8 2293.98   838.1 2301.49   860.1 2311.65
#Mann= 5 ,-1,0
       0      .1       0     110     .06       0     190      .1       0
   450.3    .045       0  521.93      .1       0
Bank Sta=450.3,521.93
XS Rating Curve= 0 ,0
Exp/Cntr=0.3,0.1

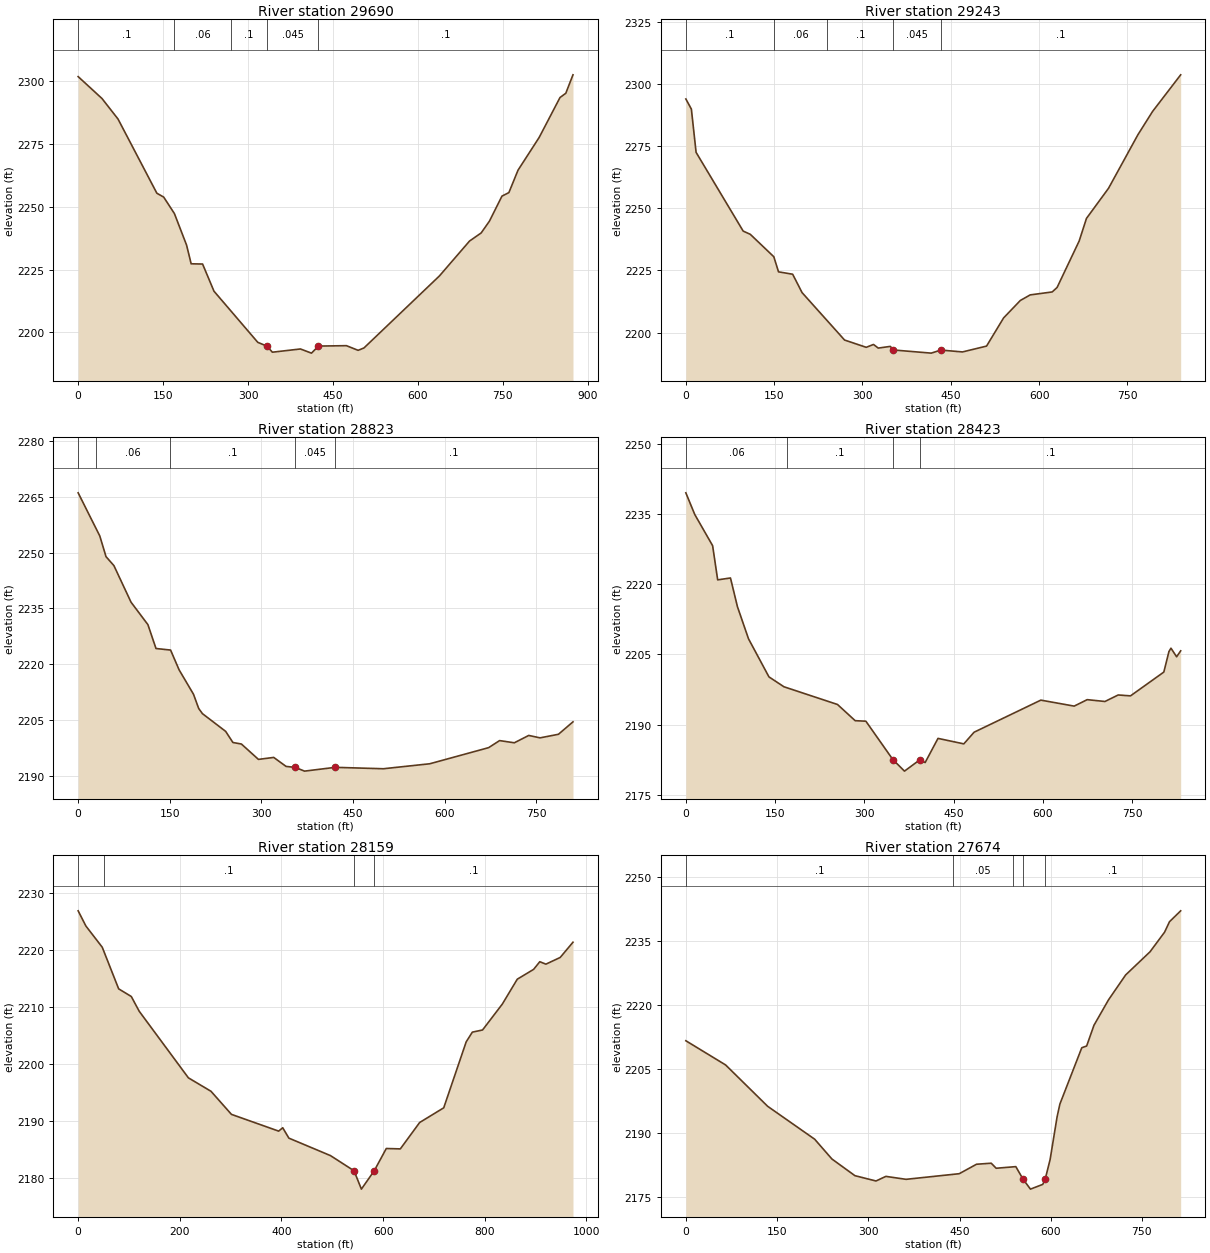
Type RM Length L Ch R = 1 ,29690   ,440.8,446.5,443.5
XS GIS Cut Line= 4
2265046.46500633689571.0531895342265328.42888191  689532.2777933
2265591.87503186689466.885004913     2265902.905689400.743042635
#Sta/Elev= 30
       0 2301.63    42.1 2292.93    70.4 2284.79     139 2255.32   151.1 2253.77
     170 2247.24   191.5 2234.71   199.6 2227.28   219.8 2227.19   239.9  2216.4
   317.3 2196.08  333.092194.616   343.1 2192.17   392.6 2193.45   412.1  2191.8
   424.5  2194.6   473.9 2194.76   494.5 2192.91   504.8 2193.85   638.2 2222.48
   691.3 2236.32   711.8 2239.53   726.4 2244.21   748.6 2254.17   760.8 2255.56
   776.9 2264.45   814.3 2277.48   851.1 2293.33   861.3 2295.01     874 2302.34
#Mann= 5 ,-1,0
       0      .1       0     170     .06       0     270      .1       0
  333.09    .045       0   424.5      .1       0
Bank Sta=333.09,424.5
XS Rating Curve= 0 ,0
Exp/Cntr=0.3,0.1

Type RM Length L Ch R = 1 ,29243   ,389,420.1,450
XS GIS Cut Line= 4
2265162.80503552689961.1955854572265423.26382407689954.516999163
 2265712.6176273689894.2652911742265985.98872336689816.269240283
#Sta/Elev= 30
       0 2294.02     9.4 2289.95    17.4 2272.54    97.4 2240.85   109.4 2239.57
   149.4 2230.54   157.4 2224.46   181.4  2223.5   197.4  2216.1   269.6 2197.01
   306.4 2194.09   318.7 2195.24   326.8 2193.78   347.3 2194.46  352.642193.013
   416.7 2191.75   433.1 2192.98   469.9 2192.23   510.7 2194.58   539.7 2205.93
   568.1 2212.94   584.8 2215.18   622.2 2216.37   630.5 2218.16     668 2236.86
   680.4 2245.96   717.9 2258.09   767.8 2279.64   792.7 2289.01   840.4 2303.74
#Mann= 5 ,-1,0
       0      .1       0     150     .06       0     240      .1       0
  352.64    .045       0   433.1      .1       0
Bank Sta=352.64,433.1
XS Rating Curve= 0 ,0
Exp/Cntr=0.3,0.1

Type RM Length L Ch R = 1 ,28823   ,419.6,400.6,367.2
XS GIS Cut Line= 4
2265181.65536583690109.3390561842265437.30797001690259.278433655
2265597.96688639690382.0410418522265830.51566246690588.961656022
#Sta/Elev= 30
       0 2266.13    35.4 2254.52    45.6 2248.95    58.6 2246.51    86.5  2236.7
   114.2 2230.63   127.4 2224.21   151.3 2223.79   165.2 2218.47   188.8 2211.89
   197.3 2208.06   203.4 2206.67   241.4  2201.9   253.3  2198.9   267.2 2198.49
   295.1 2194.35   320.1 2194.88   340.3 2192.46   355.4 2192.19   370.5 2191.19
   420.8 2192.21   499.5 2191.83   575.5 2193.17   671.8 2197.51   689.8 2199.41
   713.9 2198.82   737.5  2200.8     756 2200.15   786.1 2201.11   809.9 2204.46
#Mann= 5 ,-1,0
       0      .1       0      30     .06       0     150      .1       0
   355.4    .045       0   420.8      .1       0
Bank Sta=355.4,420.8
XS Rating Curve= 0 ,0
Exp/Cntr=0.3,0.1

Type RM Length L Ch R = 1 ,28423   ,265.5,264.2,260.7
XS GIS Cut Line= 4
 2265022.1863191690603.1000094762265262.13488932690695.223121257
2265522.43624005690587.032024863 2265794.5207795690695.223121257
#Sta/Elev= 30
       0 2239.49      15 2234.86      45 2228.21    53.5 2220.91      75 2221.31
    86.7 2215.19   105.3 2208.33   139.7 2200.19   164.9 2198.08   254.9  2194.3
   284.6 2190.84   302.6 2190.73  348.032182.521   367.5 2180.07   393.5 2182.51
   402.2  2181.9   423.8 2187.06   467.2 2185.89   484.5 2188.38   596.7 2195.23
   652.7 2193.95   674.6 2195.33   704.4 2194.94   726.7 2196.33   747.4 2196.14
   803.4 2201.22     812 2205.61   815.4 2206.32   824.9 2204.48   831.7 2205.75
#Mann= 4 ,-1,0
       0     .06       0     170      .1       0  348.03    .045       0
   393.5      .1       0
Bank Sta=348.03,393.5
XS Rating Curve= 0 ,0
Exp/Cntr(USF)=0,0
Exp/Cntr=0.3,0.1

Type RM Length L Ch R = 1 ,28159   ,473.2,484.9,496.4
XS GIS Cut Line= 4
2264937.14574309690963.6223856332265479.06885003690891.749951724
2265596.52789883 690821.602723082265885.21068088690792.457067959
#Sta/Elev= 30
       0 2226.92    15.2 2224.26    47.4 2220.53    79.7 2213.23   104.6 2211.88
   120.1  2209.3   216.9 2197.61   261.4 2195.25   301.6  2191.2   394.5 2188.26
   402.5 2188.85   414.6 2187.03   496.5 2183.96   542.8  2181.3   557.3 2178.08
  582.592181.306   606.3 2185.21   633.9 2185.14   671.9 2189.77   719.3 2192.35
   763.5 2203.93   775.6 2205.63   795.7 2206.01   834.7 2210.57     864 2214.92
   896.2 2216.65   908.3 2217.99   920.3 2217.56   948.5 2218.74   973.6 2221.41
#Mann= 4 ,-1,0
       0     .06       0      50      .1       0   542.8    .045       0
  582.59      .1       0
Bank Sta=542.8,582.59
XS Rating Curve= 0 ,0
Exp/Cntr=0.3,0.1

Type RM Length L Ch R = 1 ,27674   ,553,538.8,512
XS GIS Cut Line= 4
2265075.90589511 691251.897724012265300.88075998691293.445592133
2265677.07258694691341.0610689982265882.56361633691350.504793007
#Sta/Elev= 30
       0 2211.66    65.4 2205.98   134.5 2196.28   211.8 2188.56   240.2 2183.91
     278    2180   312.7 2178.75   328.9 2179.83   362.1 2179.14   449.6 2180.46
     478 2182.68   502.2 2182.92   510.3 2181.74   542.6 2182.12   554.7 2179.13
   566.7 2176.84   586.9 2177.95   590.9 2179.17     599 2183.78   610.5 2193.82
   615.1 2196.81   651.1 2210.02   659.1 2210.43   671.1 2215.29     695 2221.25
   723.2  2227.1   763.2 2232.52   787.2 2237.13   795.3 2239.59   813.7 2242.15
#Mann= 5 ,-1,0
       0      .1       0  438.78     .05       0  538.78      .1       0
   554.7    .045       0   590.9      .1       0
Bank Sta=554.7,590.9
XS Rating Curve= 0 ,0
Exp/Cntr=0.3,0.1

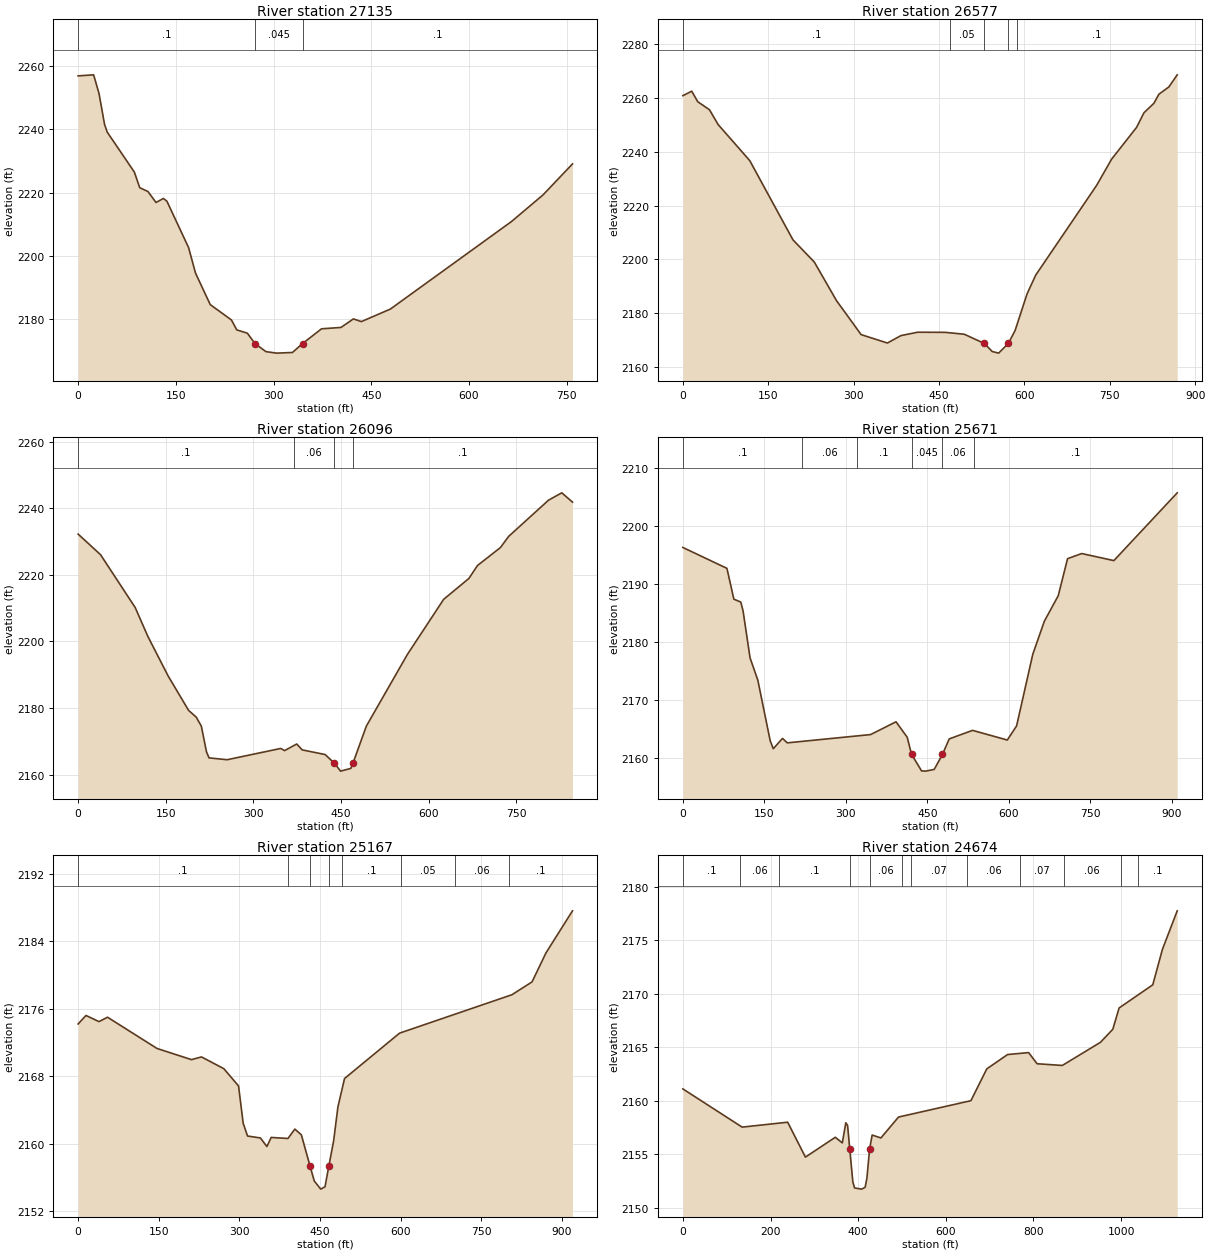
Type RM Length L Ch R = 1 ,27135   ,532.8,558.1,567.6
XS GIS Cut Line= 4
2265117.31033812691748.656361757 2265308.0380294691804.092116961
2265553.56471737691758.1689345922265860.79899367691713.133293797
#Sta/Elev= 30
       0 2256.93    23.8 2257.26    32.1 2251.33    40.5 2241.63    44.6 2239.15
    86.3 2226.48    94.6 2221.52   107.1 2220.34   119.6 2216.85   130.9 2218.13
   136.3 2217.25   169.6 2202.56   180.2  2194.5   202.8 2184.53   235.4 2179.66
   243.5 2176.53   259.8 2175.48  271.412172.207   288.3 2169.64   304.6 2169.17
     329 2169.37  344.522172.208   373.7 2176.87   403.5  2177.3   422.6    2180
   434.8 2179.15   479.3 2183.11   665.3 2210.83   713.8 2219.28   758.9 2229.06
#Mann= 3 ,-1,0
       0      .1       0  271.41    .045       0  344.52      .1       0
Bank Sta=271.41,344.52
XS Rating Curve= 0 ,0
Exp/Cntr=0.3,0.1

Type RM Length L Ch R = 1 ,26577   ,469.1,480.7,489.4
XS GIS Cut Line= 4
2265066.70982909691960.5658249032265266.87427338692182.724421855
2265503.75722458692345.9879529942265761.66171085692459.600872095
#Sta/Elev= 30
       0 2260.79    15.6 2262.46    26.1 2258.56    46.8 2255.56    61.9 2250.09
   117.6 2236.66   193.4 2207.28   230.9 2199.05     270 2184.69   313.2  2172.1
   359.3 2168.98   383.2 2171.74   412.3 2172.99   460.9 2172.94   494.4 2172.24
  529.252168.862   543.5 2165.83   554.8 2165.23  571.912168.861   583.6 2173.59
   604.6 2187.16   619.8 2194.16   727.1 2227.56   753.2 2237.23     797 2248.99
   810.1 2254.46   827.6 2257.97   836.3 2261.33   853.8 2264.03   868.5 2268.53
#Mann= 5 ,-1,0
       0      .1       0  469.03     .05       0  529.25    .045       0
  571.91     .05       0  586.73      .1       0
Bank Sta=529.25,571.91
XS Rating Curve= 0 ,0
Exp/Cntr=0.3,0.1

Type RM Length L Ch R = 1 ,26096   ,426.1,425.3,427.6
XS GIS Cut Line= 4
2264915.55041399692203.4086209782264998.19847926692396.042927284
2265123.82480993692665.5951011682265339.62986108692927.221137065
#Sta/Elev= 30
       0 2232.24    38.4 2226.05    97.7 2210.19   119.4 2201.51   154.1 2189.64
   189.1 2179.31   202.1  2177.3   210.9 2174.59   219.7 2166.87   224.1 2165.06
     255  2164.5   346.9 2167.89   353.4 2167.24   374.2 2169.22   383.5 2167.46
   422.7 2166.06  438.772163.449   449.2 2161.08   466.8  2161.9   470.42163.448
   493.3 2174.58   563.5 2196.08   625.7 2212.66   668.9 2218.93   683.6 2222.81
   722.9 2228.21   737.1 2231.58   805.3 2242.44   827.9 2244.63   846.2 2241.84
#Mann= 4 ,-1,0
       0      .1       0  369.62     .06       0  438.77    .045       0
   470.4      .1       0
Bank Sta=438.77,470.4
XS Rating Curve= 0 ,0
Exp/Cntr=0.3,0.1

Type RM Length L Ch R = 1 ,25671   ,495.8,503.6,508.3
XS GIS Cut Line= 3
     2264541.625      692333.162     2264699.653      692759.837
     2264857.682      693186.513
#Sta/Elev= 30
       0 2196.33    81.1 2192.72    93.9 2187.39   106.7 2186.88   110.9 2185.31
   123.7 2177.23     138 2173.38   160.7 2162.93   166.4 2161.52   183.4 2163.31
   192.2 2162.54   345.5 2163.97   392.4 2166.18   412.9 2163.52     4212160.544
   439.4 2157.69   447.1 2157.65   462.7 2157.95  477.912160.546   490.3 2163.22
   533.2  2164.7   597.2 2163.03   614.3 2165.46   644.1 2177.85   665.4 2183.57
     691 2187.99   708.1 2194.39   734.2 2195.28   793.4 2194.06     910 2205.78
#Mann= 6 ,-1,0
       0      .1       0     220     .06       0     320      .1       0
     421    .045       0  477.91     .06       0     535      .1       0
Bank Sta=421,477.91
XS Rating Curve= 0 ,0
Exp/Cntr=0.3,0.1

Type RM Length L Ch R = 1 ,25167   ,493.6,493,492.8
XS GIS Cut Line= 3
     2264195.038      692438.5582264217.67724815692928.926036977
     2264351.001      693336.036
#Sta/Elev= 30
       0 2174.21    14.6 2175.22    38.7 2174.49    54.7 2175.01   146.8  2171.3
   210.8 2169.98   229.4  2170.3   270.9 2168.91   298.3 2166.86   306.9 2162.44
     315 2160.92     339 2160.69     351 2159.67     359 2160.75   390.2 2160.63
     403 2161.74   415.1 2161.06  431.222157.362   439.1 2155.59   451.1 2154.62
   459.1  2154.9  466.262157.362   475.1 2160.34   483.1 2164.37   495.4 2167.74
   597.7 2173.12   806.8 2177.68   844.1  2179.2     870 2182.64   919.3 2187.63
#Mann= 8 ,-1,0
       0      .1       0     390     .06       0  431.22    .045       0
  466.26     .06       0     490      .1       0  600.89     .05       0
  700.89     .06       0  800.89      .1       0
Bank Sta=431.22,466.26
XS Rating Curve= 0 ,0
Exp/Cntr=0.3,0.1

Type RM Length L Ch R = 1 ,24674   ,519.1,531.9,531.8
XS GIS Cut Line= 3
2263696.65125555692510.1285036982263731.76751109693038.353366478
     2264230.619      693369.533
#Sta/Elev= 30
       0  2161.1   135.3 2157.53   239.2 2157.99   279.7 2154.73   347.8 2156.58
   363.9 2156.06   371.9 2157.94   375.9 2157.69  380.912155.485   387.9 2152.41
   391.9 2151.85   407.9 2151.74     416 2151.91     420 2152.76  426.192155.499
     432 2156.79     452 2156.52   492.1 2158.47   657.4    2160   693.6 2162.97
   741.1 2164.31   789.1 2164.49   808.4 2163.45     866 2163.29     953 2165.45
   981.2 2166.67   995.6 2168.66  1072.4 2170.82  1094.4 2174.13  1128.2 2177.73
#Mann= 12 ,-1,0
       0      .1       0     130     .06       0     220      .1       0
  380.91    .045       0  426.19     .06       0     500     .05       0
     520     .07       0  649.39     .06       0  769.39     .07       0
  869.39     .06       0  999.39     .07       0 1039.39      .1       0
Bank Sta=380.91,426.19
XS Rating Curve= 0 ,0
Exp/Cntr=0.3,0.1