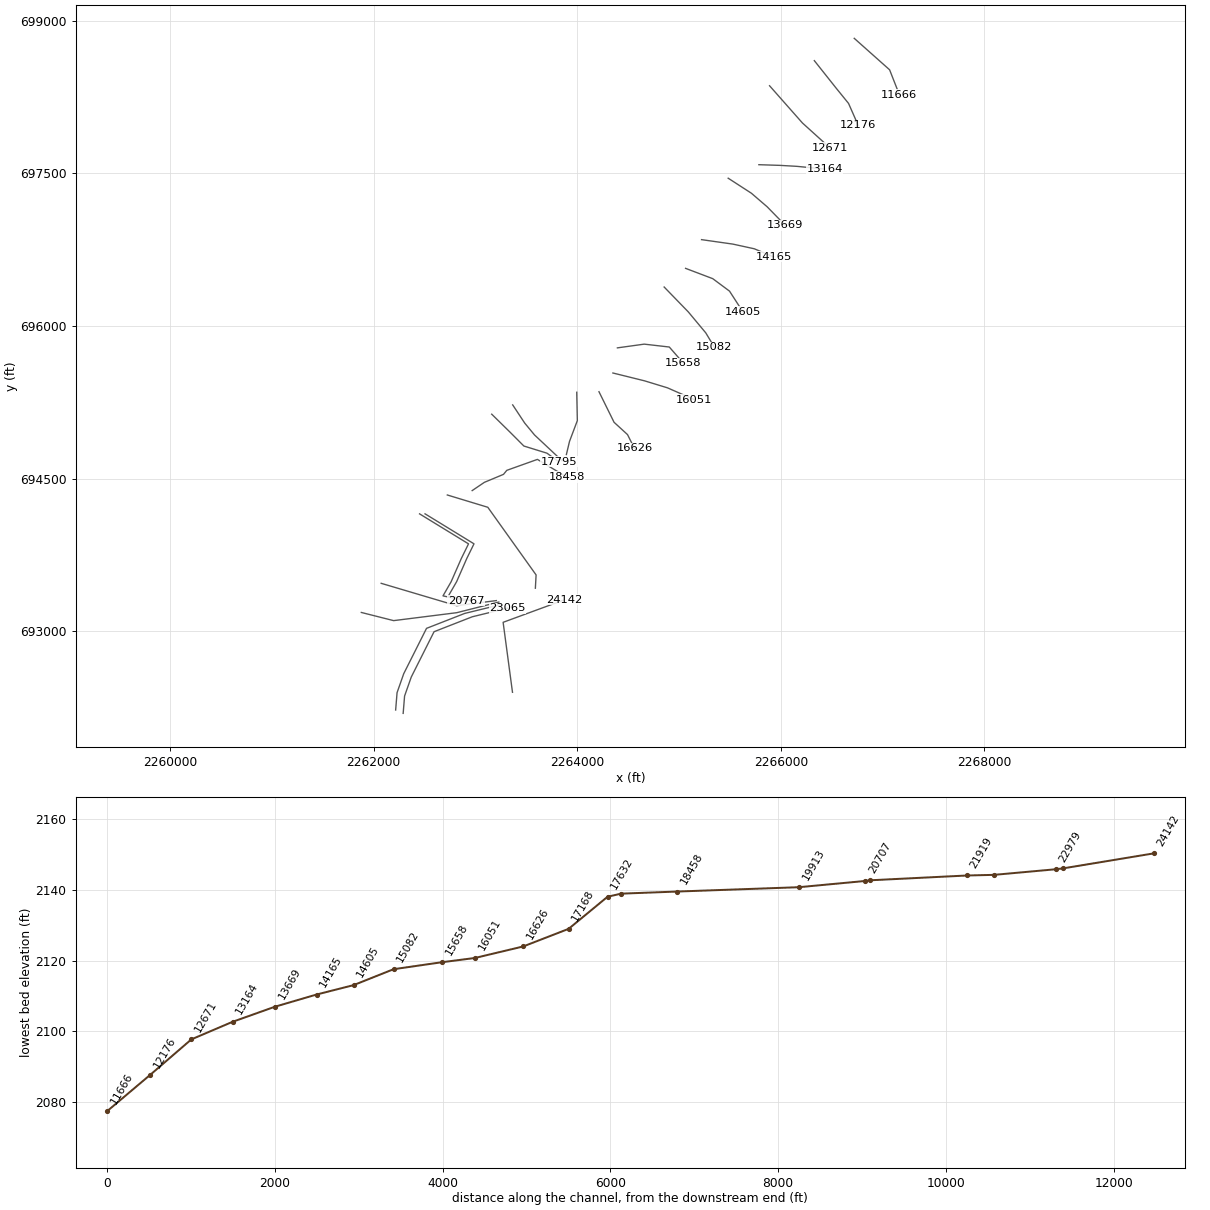
HEC-RAS study ROARCK.prj: ROARCK

--- ROARCK.g01 (geometry) --- (continued)

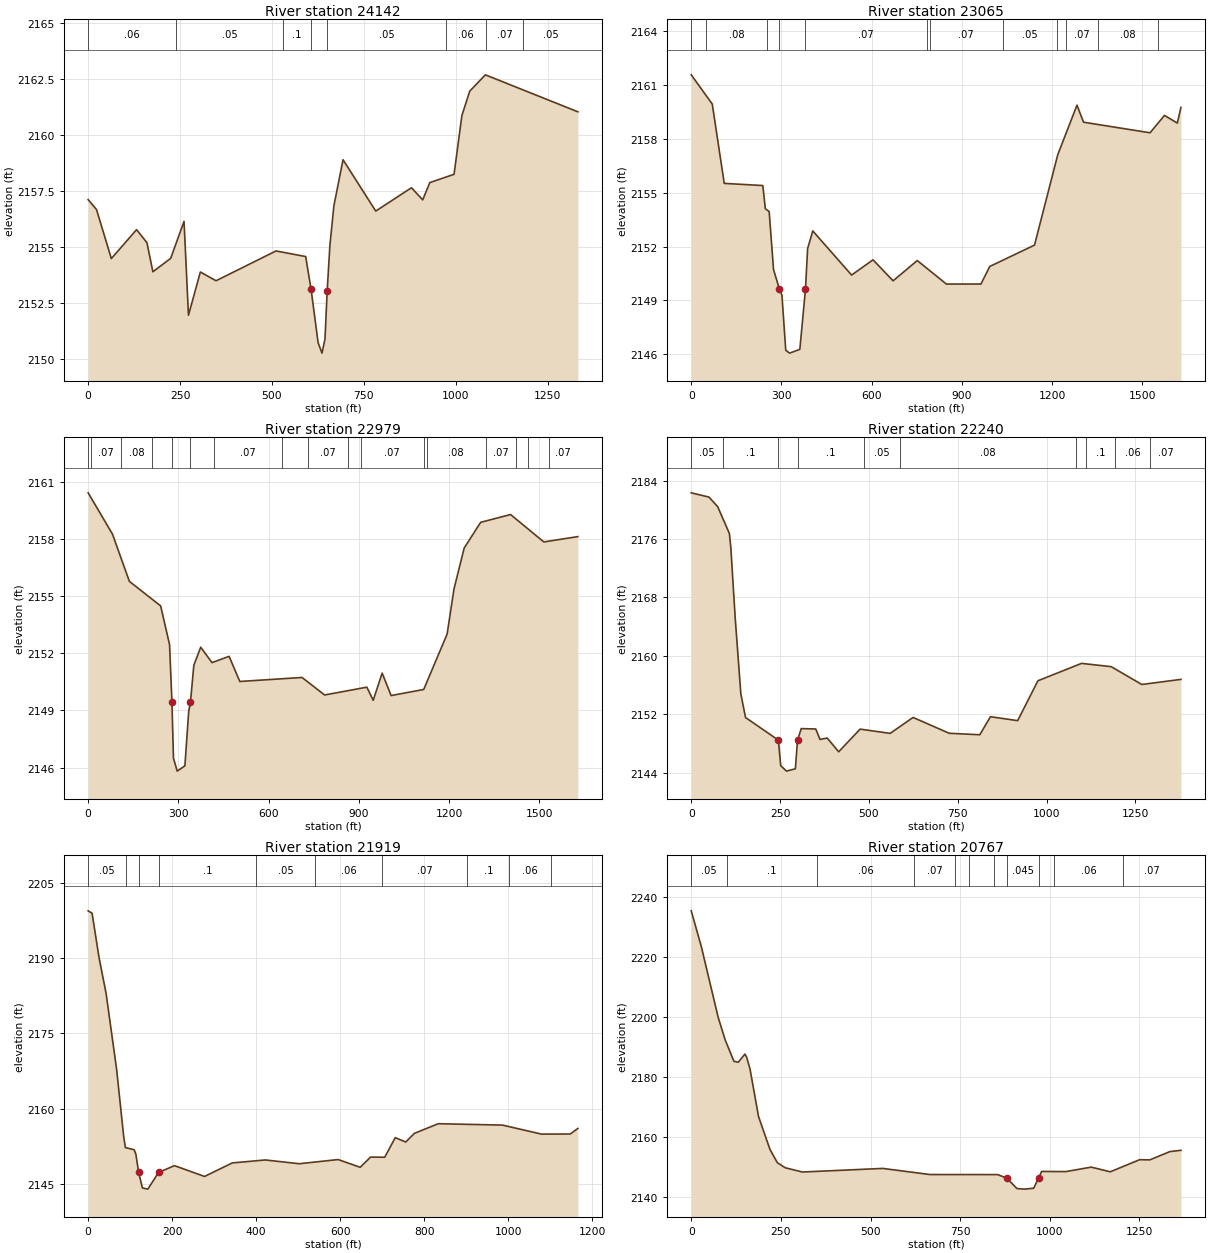
Type RM Length L Ch R = 1 ,24142   ,1096.4,1077,1046.1
XS GIS Cut Line= 3
 2263364.6006454692402.6687700972263272.66071487693089.871299919
2263872.25723007693309.918152011
#Sta/Elev= 30
       0 2157.13    22.7 2156.69    63.1  2154.5   131.7 2155.79   159.9 2155.21
   176.1 2153.91   224.5 2154.51   260.8 2156.16   272.9 2151.97   305.2  2153.9
   347.9 2153.51     511 2154.84   591.7 2154.59   606.5 2153.12   625.5 2150.75
     636 2150.28   644.2  2150.9  650.152153.046   657.5 2155.07   668.4 2156.85
   693.3 2158.91   782.3 2156.62   879.4 2157.66   910.1 2157.12   929.3 2157.89
   995.3 2158.26  1016.6 2160.88  1037.9 2161.97  1080.5  2162.7    1332 2161.05
#Mann= 8 ,-1,0
       0     .06       0     240     .05       0     530      .1       0
   606.5    .045       0  650.15     .05       0  973.33     .06       0
 1083.33     .07       0 1183.33     .05       0
Bank Sta=606.5,650.15
XS Rating Curve= 0 ,0
Exp/Cntr=0.3,0.1

Type RM Length L Ch R = 1 ,23065   ,81.6,86,88.3
XS GIS Cut Line= 6
2262290.95775011692195.5272775712262304.87980004  692365.8574958
 2262370.4216775692552.2157767532262594.29270562692997.422689702
2262969.28581702693144.0933824672263315.81808148693228.781716951
#Sta/Elev= 30
       0 2161.57    69.9 2159.94   109.7 2155.52   237.9  2155.4   246.3 2154.11
     259 2153.95   273.6 2150.72  292.952149.633   301.5 2149.29   314.2 2146.22
     327 2146.06     361 2146.27   379.82149.634   386.8 2151.88     404 2152.87
   533.1 2150.41   604.3 2151.26     671 2150.09   751.4 2151.22   848.1 2149.91
     963 2149.91   992.4 2150.89  1141.1 2152.08  1218.4 2157.12  1282.3 2159.88
  1304.1 2158.93  1525.2 2158.34  1573.2 2159.31  1615.8 2158.88  1627.8 2159.75
#Mann= 12 ,-1,0
       0     .07       0      50     .08       0   250.9     .07       0
  292.95    .045       0   379.8     .07       0  782.26     .06       0
  792.26     .07       0  1035.5     .05       0  1215.5     .08       0
  1245.5     .07       0 1351.07     .08       0 1551.07     .07       0
Bank Sta=292.95,379.8
XS Rating Curve= 0 ,0
Exp/Cntr=0.3,0.1

Type RM Length L Ch R = 1 ,22979   ,773.1,738.7,685.4
XS GIS Cut Line= 6
2262217.10376406692228.5962265482262231.02581399692398.926444777
2262296.56769145692585.2847257312262520.43871957693030.491638679
2262895.43183097693177.1623314442263241.96409543693261.850665928
#Sta/Elev= 30
       0 2160.43    80.9 2158.26     137 2155.78     241 2154.49   270.6 2152.46
  278.532149.443   283.6 2146.49   296.1 2145.81   321.6 2146.09   334.3 2148.95
  340.172149.446   351.3 2151.37   374.2 2152.32   411.7 2151.51   468.6 2151.84
   504.1 2150.52     711 2150.73   786.1 2149.81   926.4 2150.22   947.6 2149.53
   977.3 2150.96  1007.1 2149.78  1115.5  2150.1  1193.3 2153.01    1216 2155.37
    1250 2157.53  1304.8 2158.88  1404.1 2159.29  1514.8 2157.85  1627.8 2158.13
#Mann= 17 ,-1,0
       0     .08       0      10     .07       0     110     .08       0
   210.9     .07       0  278.53    .045       0  340.17     .08       0
  418.45     .07       0  645.96     .06       0  732.26     .07       0
  862.78     .08       0   905.5     .07       0  1115.5     .05       0
  1125.5     .08       0 1321.07     .07       0 1421.07     .08       0
 1461.07     .06       0 1531.07     .07       0
Bank Sta=278.53,340.17
XS Rating Curve= 0 ,0
Exp/Cntr=0.3,0.1

Type RM Length L Ch R = 1 ,22240   ,321.6,321,319.8
XS GIS Cut Line= 4
2261880.03310928693186.6221432332262197.38510147693106.399463356
2262816.87555738693184.3181214482263230.43524779693288.678525024
#Sta/Elev= 30
       0 2182.32    49.7 2181.74    74.4 2180.43   107.4 2176.75   111.5 2174.78
   123.9 2165.08   139.6  2154.8   152.8 2151.56  245.242148.458   251.8 2144.97
   268.1 2144.22   293.1 2144.54  299.072148.457   309.6 2150.04   350.4 2149.99
   362.4 2148.56   382.6 2148.75     415 2146.87   475.3 2149.97   559.9 2149.39
   624.4 2151.57   726.2  2149.4   812.2  2149.2   842.1 2151.67   918.7 2151.13
   975.7 2156.59  1098.5 2158.97    1182 2158.52  1268.1 2156.08  1378.2 2156.78
#Mann= 10 ,-1,0
       0     .05       0      90      .1       0  245.24    .045       0
  299.07      .1       0  487.33     .05       0  587.33     .08       0
 1081.71     .07       0 1111.71      .1       0 1191.71     .06       0
 1291.71     .07       0
Bank Sta=245.24,299.07
XS Rating Curve= 0 ,0
Exp/Cntr=0.3,0.1

Type RM Length L Ch R = 1 ,21919   ,1156,1153,1116.8
XS GIS Cut Line= 3
2262075.12006544693472.737774901 2262816.0417561693253.000801528
2263205.98731935 693303.10718671
#Sta/Elev= 30
       0 2199.38     9.4  2198.9    26.1 2189.99    42.8 2182.93    67.9 2167.79
    84.5  2154.6    88.7  2152.3   109.6 2151.87   113.7 2150.97  120.122147.407
   129.2 2144.27   142.1 2144.04   167.8 2147.36   205.5 2148.71   277.2 2146.56
   343.2 2149.25     422 2149.84   502.5 2149.09   595.3 2149.92   647.8 2148.38
   672.4 2150.41   706.2 2150.38   731.2 2154.28   756.3 2153.41     777 2155.14
   833.8 2157.05   986.7 2156.77  1079.5 2154.98    1148    2155    1166 2156.11
#Mann= 10 ,-1,0
       0     .05       0      90      .1       0  120.12    .045       0
   167.8      .1       0     400     .05       0     540     .06       0
     700     .07       0  902.82      .1       0 1002.82     .06       0
 1102.82     .07       0
Bank Sta=120.12,167.8
XS Rating Curve= 0 ,0
Exp/Cntr(USF)=0,0
Exp/Cntr=0.3,0.1

Type RM Length L Ch R = 1 ,20767   ,74.6,59.2,50.6
XS GIS Cut Line= 6
2262452.08922027694154.9094755712262932.80778848693860.424751905
2262861.77078698693715.901197116 2262762.2745255693488.816479535
2262682.08270679693349.4882426152262908.89305643693301.102034693
#Sta/Elev= 30
       0 2235.55    28.2 2223.58      75 2200.06    94.5 2192.53     119 2185.34
   131.1 2185.04   149.8 2187.75   154.5 2186.73   163.8 2182.84   187.7  2166.9
   219.7 2155.91   240.1 2151.51   262.1 2149.82     310  2148.4   534.2  2149.6
   665.3 2147.56   854.6 2147.54  880.052146.352   908.4 2142.88   928.8 2142.69
     955 2142.99  968.612146.353   977.1 2148.59  1044.7 2148.54  1115.4 2150.03
  1168.5 2148.47  1250.4 2152.51    1279 2152.45  1334.6 2155.21  1365.6 2155.64
#Mann= 11 ,-1,0
       0     .05       0     100      .1       0     350     .06       0
  622.55     .07       0  734.98     .06       0  774.98     .07       0
  844.98     .06       0  880.05    .045       0  968.61     .07       0
  1012.9     .06       0 1203.67     .07       0
Bank Sta=880.05,968.61
XS Rating Curve= 0 ,0
Exp/Cntr(USF)=0,0
Exp/Cntr=0.3,0.1

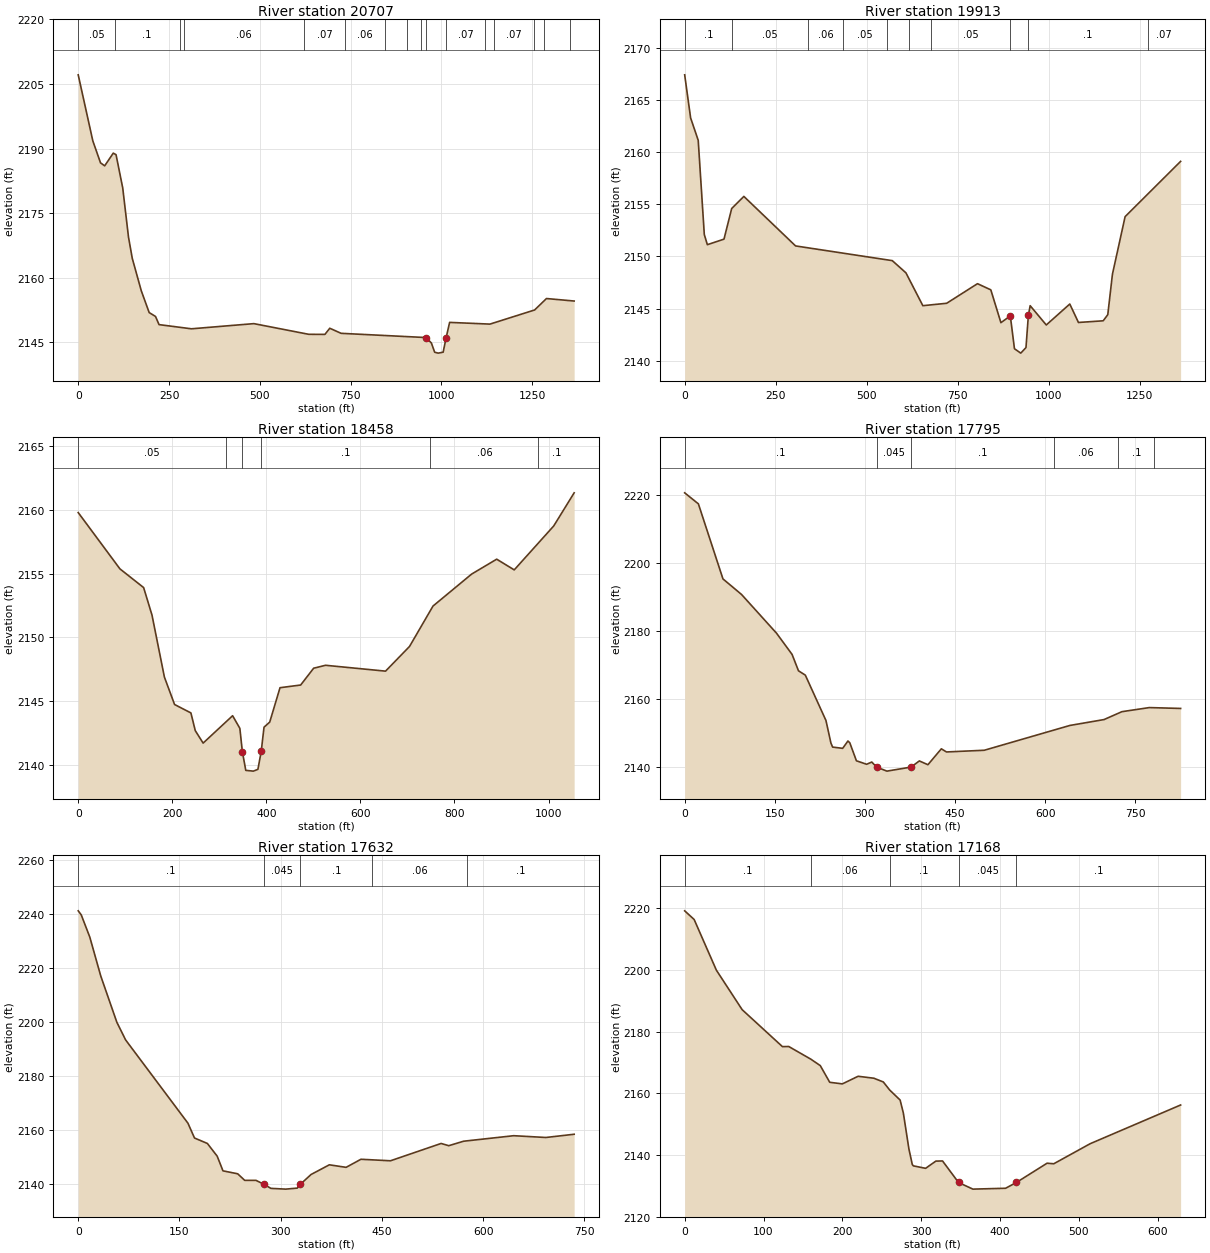
Type RM Length L Ch R = 1 ,20707   ,759.2,794.5,817.7
XS GIS Cut Line= 6
2262505.83212589694155.201431059 2262986.5506941693860.716707393
 2262915.5136926693716.1931526042262816.01743112693489.108435023
2262735.82561241693349.7801981032262962.63596205693301.393990181
#Sta/Elev= 30
       0 2207.14    40.2 2191.81    61.4  2186.7    72.9    2186    96.5 2188.95
   104.2 2188.59   122.6 2180.86   138.4 2169.49   148.8 2164.53   173.6    2157
   195.4 2151.92   212.8 2151.02   222.6 2149.12   311.9 2148.15   483.7 2149.35
   634.7 2146.87   679.3 2146.85   692.7 2148.28   723.9  2147.1  957.912146.115
   972.5 2144.85   981.5 2142.71   991.2  2142.5  1004.9 2142.72  1013.22146.118
  1022.7 2149.64  1133.7 2149.24  1256.7 2152.52  1289.4 2155.18  1365.6  2154.6
#Mann= 16 ,-1,0
       0     .05       0     100      .1       0     280     .05       0
     290     .06       0  622.55     .07       0  734.98     .06       0
  844.98     .05       0  904.98     .06       0  944.98     .07       0
  957.91    .045       0  1013.2     .07       0 1119.68     .06       0
 1143.67     .07       0 1253.67     .05       0 1283.67     .07       0
 1353.67      .1       0
Bank Sta=957.91,1013.2
XS Rating Curve= 0 ,0
Exp/Cntr(USF)=0,0
Exp/Cntr=0.3,0.1

Type RM Length L Ch R = 1 ,19913   ,1407.9,1454.6,1492.3
XS GIS Cut Line= 4
2262724.57953187694340.2525531162263122.13711475694219.607469613
2263596.43605273693555.2475294952263589.34561756693424.574191643
#Sta/Elev= 30
       0 2167.42    16.3 2163.29    37.2 2161.14    53.9 2152.11    62.3 2151.13
     108 2151.66   129.2  2154.6   162.6 2155.76   304.7 2151.01   570.4  2149.6
   607.9 2148.43   654.4 2145.28   719.8 2145.51   804.5 2147.39   841.1  2146.8
   868.9 2143.65   894.7  2144.3   906.1 2141.15   923.4 2140.73   937.7 2141.26
   944.3 2144.34   949.2 2145.28   993.5 2143.43  1058.1 2145.44  1081.9 2143.67
  1149.9 2143.83  1162.5 2144.42  1175.3  2148.3  1210.1 2153.82  1362.6 2159.12
#Mann= 10 ,-1,0
       0      .1       0     130     .05       0     340     .06       0
  435.46     .05       0  555.46     .06       0  615.46     .03       0
  675.46     .05       0   894.7    .045       0   944.3      .1       0
 1271.75     .07       0
Bank Sta=894.7,944.3
XS Rating Curve= 0 ,0
Exp/Cntr=0.3,0.1

Type RM Length L Ch R = 1 ,18458   ,695.7,663.7,622.5
XS GIS Cut Line= 6
2262968.71400479694383.4746559782263088.10380173 694464.27356536
2263276.48363389694543.0560308982263308.65143857694582.369824836
2263609.50438478694689.8888958942263897.38565733694516.858710929
#Sta/Elev= 30
       0  2159.8    88.7 2155.38   139.1 2153.91   156.9 2151.75   183.3 2146.88
   204.9 2144.73   239.6 2144.07   248.9 2142.68   265.6  2141.7   328.3 2143.85
   343.7 2142.86     3492141.037   356.3 2139.56   372.4  2139.5   382.1 2139.64
  389.142141.051   395.1 2142.95   407.2 2143.35   429.1 2146.05     473 2146.26
   500.6 2147.58   525.9 2147.81   653.5 2147.35   704.5 2149.29   754.4 2152.46
   836.5 2154.97   889.8 2156.14   927.1  2155.3  1011.1 2158.75  1054.5 2161.35
#Mann= 6 ,-1,0
       0     .05       0  314.16      .1       0     349    .045       0
  389.14      .1       0  748.64     .06       0  978.64      .1       0
Bank Sta=349,389.14
XS Rating Curve= 0 ,0
Exp/Cntr=0.3,0.1

Type RM Length L Ch R = 1 ,17795   ,163.3,162.3,157.4
XS GIS Cut Line= 5
2263160.64537566 695133.832962562263342.11926847694955.720199589
2263476.40465371694821.0921159312263703.17635851 694750.90803993
2263819.22398521694666.486740581
#Sta/Elev= 30
       0 2220.51    22.8 2217.28    63.7 2195.27    94.6 2190.71   152.9 2179.34
   178.7 2173.14   189.4 2168.33   200.8 2167.05   235.1 2153.76   243.4 2147.12
   246.2 2145.96   262.9 2145.59   271.7 2147.74   274.8 2147.21   285.8 2141.94
   302.8 2140.92   311.3 2141.57   319.5  2140.1   336.5 2138.91  376.682140.092
   390.5  2141.9   404.8 2140.79   427.1 2145.45   435.7 2144.53   498.6 2145.03
     641  2152.3   697.9 2154.03   727.6 2156.34   773.1 2157.54   825.3 2157.29
#Mann= 6 ,-1,0
       0      .1       0   319.5    .045       0  376.68      .1       0
  614.43     .06       0  721.81      .1       0  781.81     .06       0
Bank Sta=319.5,376.68
XS Rating Curve= 0 ,0
Exp/Cntr=0.3,0.1

Type RM Length L Ch R = 1 ,17632   ,490.5,464.1,427.8
XS GIS Cut Line= 4
2263366.69243164695224.9444114922263484.72012633 695046.30089781
2263581.27863704694929.6198907772263850.76004312694677.201599951
#Sta/Elev= 30
       0 2241.13     4.5 2239.63    17.2 2231.38    33.3 2217.07    57.2 2199.88
    70.2 2193.32   162.6 2162.45   172.3 2156.97   191.4 2154.94   205.9 2150.25
   214.5  2144.8   236.3 2143.71   246.7 2141.28   263.4 2141.28  275.312139.808
   285.5 2138.31   307.4 2138.03   324.6 2138.41  329.062139.809     345 2143.45
   372.1 2147.04   396.9  2146.1   418.9 2149.09   462.7 2148.53   537.7 2154.95
     549 2154.12     571 2155.78   645.3 2157.82   692.9 2157.16   734.8 2158.36
#Mann= 5 ,-1,0
       0      .1       0  275.31    .045       0  329.06      .1       0
  435.57     .06       0  575.57      .1       0
Bank Sta=275.31,329.06
XS Rating Curve= 0 ,0
Exp/Cntr=0.3,0.1

Type RM Length L Ch R = 1 ,17168   ,493.1,542,575
XS GIS Cut Line= 4
2263995.59099849695349.1274992472264001.56045708695070.815004157
2263924.64194747694866.6697218522263894.02530409694737.712569525
#Sta/Elev= 30
       0 2219.17      12 2216.37    40.2 2199.94    72.9 2187.13     124 2175.15
     132 2175.19     160 2171.09     172    2169     184 2163.59     200 2163.07
     220 2165.54     240 2164.91     252 2163.69     260  2161.1   273.3 2157.83
   277.4 2153.61   284.4 2142.04   288.7 2136.97     290 2136.51   305.6  2135.7
   318.6 2138.04   327.1 2138.09   347.4 2131.11   365.6 2128.96   407.1 2129.24
  420.742131.111   459.7 2137.36   468.2 2137.18   514.5  2143.7   629.1 2156.23
#Mann= 5 ,-1,0
       0      .1       0     160     .06       0     260      .1       0
   347.4    .045       0  420.74      .1       0
Bank Sta=347.4,420.74
XS Rating Curve= 0 ,0
Exp/Cntr=0.3,0.1

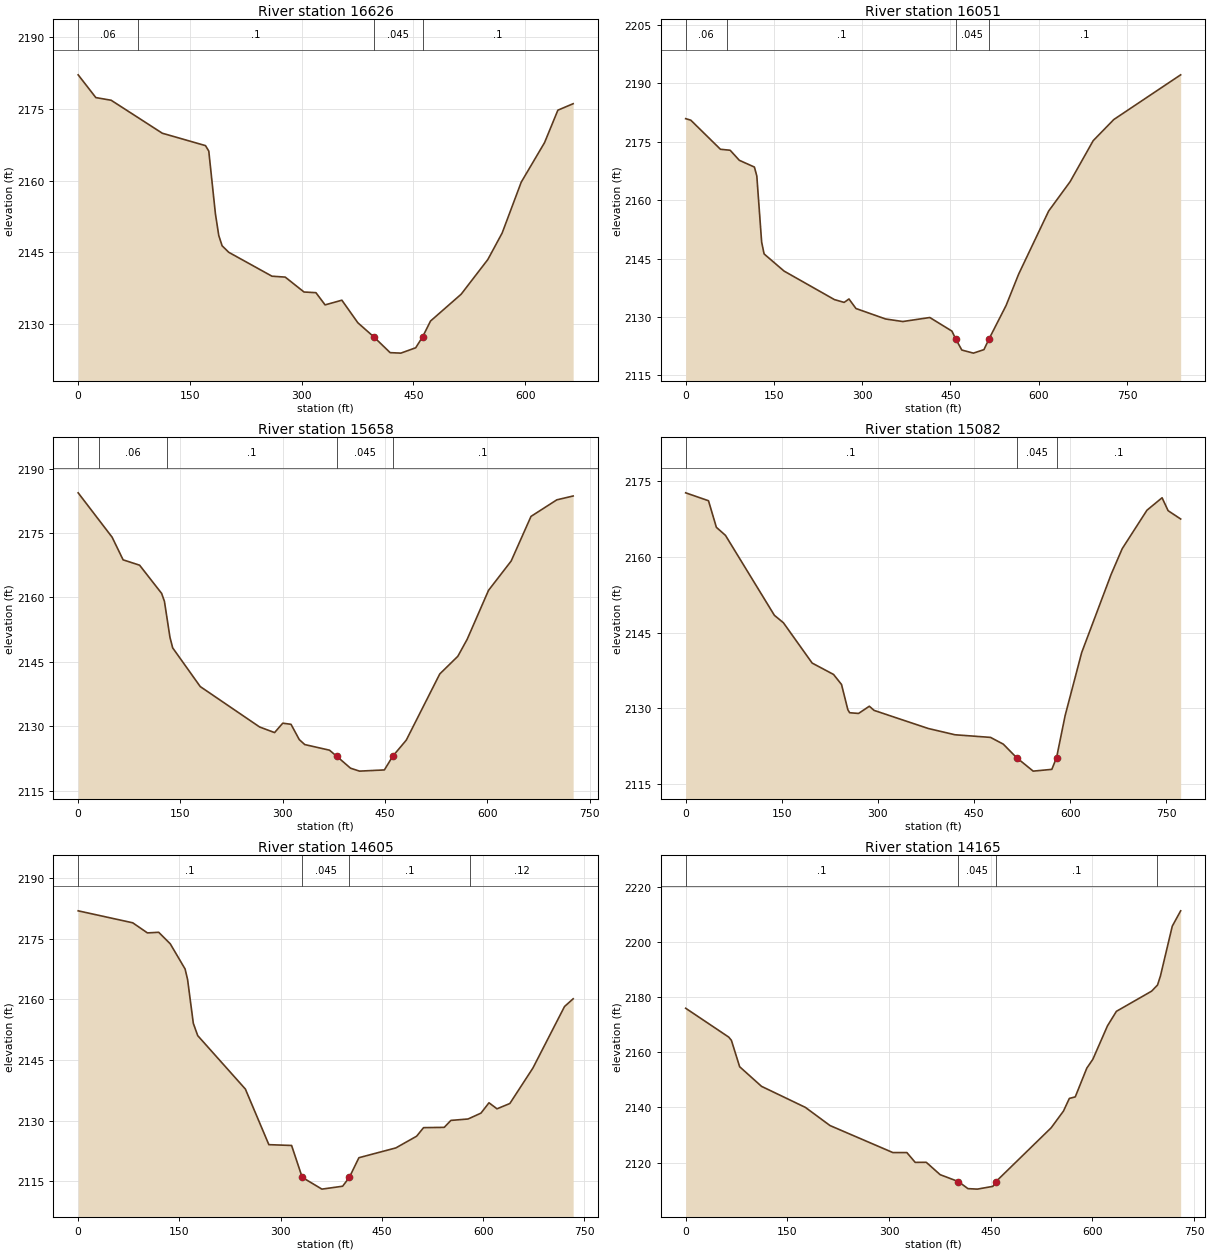
Type RM Length L Ch R = 1 ,16626   ,568.8,575.7,593.2
XS GIS Cut Line= 4
2264214.07638332695354.4098567762264362.08217313695054.366040129
2264494.28417657694933.3894256142264561.82899083694798.841094208
#Sta/Elev= 30
       0 2182.08    23.7 2177.33    44.3 2176.77   112.9 2169.89   170.9  2167.3
   175.3 2166.16   184.2 2153.06   188.7 2148.53   193.2 2146.39   202.1 2145.03
   260.1 2140.04   277.9 2139.85   303.1 2136.74   319.1  2136.6   331.4 2134.05
   353.9 2135.03   375.4 2130.31  396.412127.425   418.7 2124.08   433.1 2123.98
     453  2125.1  462.422127.426   472.9 2130.68     514 2136.28   549.8 2143.52
     569 2149.05   594.6 2159.67   625.9 2167.92   643.8  2174.7   664.3 2176.05
#Mann= 4 ,-1,0
       0     .06       0      80      .1       0  396.41    .045       0
  462.42      .1       0
Bank Sta=396.41,462.42
XS Rating Curve= 0 ,0
Exp/Cntr=0.3,0.1

Type RM Length L Ch R = 1 ,16051   ,394.1,392.7,400.3
XS GIS Cut Line= 4
2264350.81244822695538.3177063512264661.65703251 695461.34143423
2264887.37866511695392.3851385662265148.21074187695277.555763401
#Sta/Elev= 30
       0 2180.91     8.7 2180.52    59.1 2173.05    75.6  2172.8    91.2 2170.22
   116.8 2168.49   120.9 2166.19   129.1 2149.22   133.3 2146.19   167.2 2141.79
   252.8 2134.47   269.3 2133.75   277.5 2134.63   289.4 2132.18   339.6  2129.5
   368.9 2128.84   414.9 2129.87   452.5 2126.38  459.052124.328   469.3 2121.52
     489 2120.73   506.9 2121.63  515.382124.329   544.5 2132.95   565.9 2141.02
   616.9 2157.21   653.3 2164.73   692.6 2175.27   727.6 2180.69   841.2 2192.16
#Mann= 4 ,-1,0
       0     .06       0      70      .1       0  459.05    .045       0
  515.38      .1       0
Bank Sta=459.05,515.38
XS Rating Curve= 0 ,0
Exp/Cntr=0.3,0.1

Type RM Length L Ch R = 1 ,15658   ,617.2,576.2,550.2
XS GIS Cut Line= 4
2264394.89016872695785.1343990712264658.49956562695821.724191018
2264904.72451704695793.4183390412265043.92509093695633.705979189
#Sta/Elev= 30
       0 2184.36    49.8 2174.02    65.9 2168.75    90.1  2167.5   122.4 2160.93
   126.5 2159.08   134.6 2150.71   138.6 2148.24     179 2139.23   266.1 2129.81
     288 2128.51     300  2130.7   312.1 2130.44   324.2 2126.88   332.2 2125.72
   368.5 2124.41  379.032123.007   399.4 2120.21   412.6 2119.53     449 2119.81
  461.322123.008   481.1 2126.75   530.2 2142.16   556.7 2146.28   570.5 2150.27
   601.7 2161.64   634.9 2168.47     664 2178.87   701.9 2182.73   725.8 2183.62
#Mann= 5 ,-1,0
       0      .1       0      30     .06       0     130      .1       0
  379.03    .045       0  461.32      .1       0
Bank Sta=379.03,461.32
XS Rating Curve= 0 ,0
Exp/Cntr=0.3,0.1

Type RM Length L Ch R = 1 ,15082   ,469.4,476.6,482.5
XS GIS Cut Line= 4
2264854.00013174696382.7500947662265091.46637304696138.074059248
2265262.80935326695932.3271513282265347.33481895695792.425896749
#Sta/Elev= 30
       0 2172.75    35.6 2171.18    47.9 2165.91    62.1 2164.31   138.4 2148.46
   152.5 2146.98   197.3 2138.99   230.7 2136.73   243.1 2134.75     253 2129.74
   255.8 2129.14   269.7    2129   286.5 2130.43     294  2129.6   378.6 2126.01
   420.2 2124.77   475.6 2124.25   495.5 2122.91  516.142120.246   542.1 2117.56
   571.2 2117.91  578.612120.248     592  2128.6   617.8 2141.08   663.8  2156.6
     681 2161.67   719.6  2169.3   743.2 2171.77   752.6 2169.21   772.2 2167.56
#Mann= 3 ,-1,0
       0      .1       0  516.14    .045       0  578.61      .1       0
Bank Sta=516.14,578.61
XS Rating Curve= 0 ,0
Exp/Cntr=0.3,0.1

Type RM Length L Ch R = 1 ,14605   ,429.7,440.4,453.4
XS GIS Cut Line= 4
2265064.61307104 696565.91687944 2265331.3487805696464.772702798
2265496.09912154696342.2480161432265627.89210361696138.460313392
#Sta/Elev= 30
       0 2181.91    80.8 2178.95   102.6 2176.45   119.3  2176.6   136.4 2173.76
   158.4 2167.52   162.1 2164.92   170.6 2154.08   177.1 2151.04   247.7 2137.82
   282.5 2124.06   316.2 2123.86  331.892115.977   361.1 2113.06   391.8 2113.78
  401.762115.977   415.9 2120.83   470.7 2123.26   501.4 2126.15   511.7 2128.27
   542.3 2128.34   552.2 2130.06   577.6 2130.41   596.7 2131.86   608.6 2134.42
   620.5 2132.93   639.5 2134.24   673.7 2143.02   720.5 2158.23   733.3 2160.15
#Mann= 4 ,-1,0
       0      .1       0  331.89    .045       0  401.76      .1       0
  580.59     .12       0
Bank Sta=331.89,401.76
XS Rating Curve= 0 ,0
Exp/Cntr=0.3,0.1

Type RM Length L Ch R = 1 ,14165   ,507.1,495.8,480.5
XS GIS Cut Line= 4
2265221.35667488696847.9917449982265528.59544122696804.222152394
2265739.22677569696758.299133567 2265927.6196957696679.367061629
#Sta/Elev= 30
       0 2175.95    63.5  2165.5    67.5  2164.3    79.6 2154.76   111.9 2147.65
   176.6 2140.03   212.9 2133.45   305.6 2123.66   326.3 2123.66   338.6  2120.1
   354.9 2120.13   375.4 2115.65   402.32113.146   416.4 2110.59   430.2 2110.41
   453.2 2111.41  457.722113.146   539.2 2132.64   557.3 2138.69     566 2143.28
   574.7 2143.83   591.7 2154.23   600.7 2157.48   622.2 2169.56   635.4 2174.83
   687.4 2182.15   696.1 2184.38   700.4 2187.68   717.8 2205.68   730.2 2211.25
#Mann= 4 ,-1,0
       0      .1       0   402.3    .045       0  457.72      .1       0
  695.92     .12       0
Bank Sta=402.3,457.72
XS Rating Curve= 0 ,0
Exp/Cntr=0.3,0.1

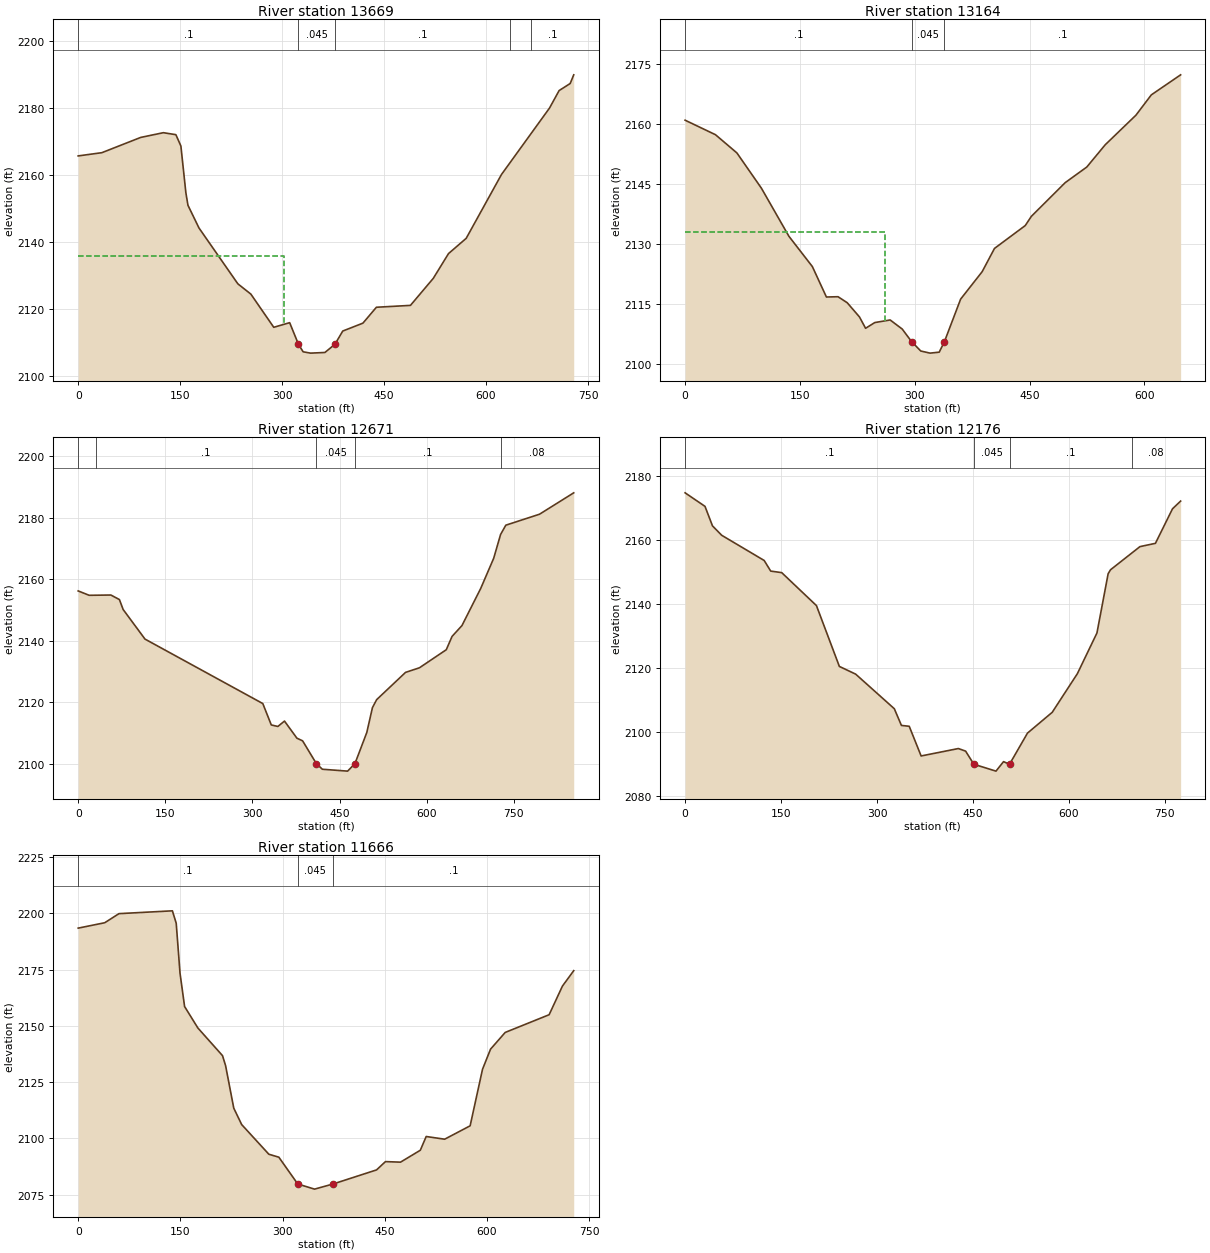
Type RM Length L Ch R = 1 ,13669   ,487.3,504.8,513.5
XS GIS Cut Line= 4
2265482.98205916697451.2661668012265711.18278674697303.535721765
 2265865.8037189697170.4863099422266042.75713722696989.487314711
#Sta/Elev= 30
       0 2165.83    34.8 2166.79      92 2171.35   125.3 2172.76   143.7 2172.17
   151.1 2168.78   158.4 2154.85   161.5 2151.09   177.7 2144.32   234.9 2127.65
     254 2124.59   287.7 2114.68   311.1 2116.06  324.062109.601   330.9 2107.37
   341.8 2106.97   362.9 2107.16   377.7  2109.6   389.2 2113.56   418.9 2115.92
   438.7 2120.66   488.8 2121.22   522.4 2129.29   544.8 2136.68   570.8 2141.23
   622.7 2160.28   693.4 2180.12   707.5 2185.33   723.8 2187.44     729 2190.03
#Mann= 5 ,-1,0
       0      .1       0  324.06    .045       0   377.7      .1       0
  635.83     .12       0  665.83      .1       0
#XS Ineff= 2 , 0
          302.09 2136.09
Permanent Ineff=
       F       F
Bank Sta=324.06,377.7
XS Rating Curve= 0 ,0
Exp/Cntr=0.3,0.1

Type RM Length L Ch R = 1 ,13164   ,518.1,493.1,468.1
XS GIS Cut Line= 4
2265784.51793808697584.0116415072265994.49934611697577.247692303
2266158.91761666697567.6948948982266430.29208198697541.361349322
#Sta/Elev= 30
       0 2160.94    39.7 2157.31    67.7 2152.75    99.7 2143.94   135.7  2131.9
   166.3 2124.34   184.6 2116.74   199.8 2116.81   211.8 2115.31   227.8 2111.76
   235.8 2108.92   247.8 2110.35   267.9    2111   283.7 2108.72  295.822105.605
   307.9 2103.24     320 2102.71     332 2102.95  338.872105.607     360 2116.22
   388.1 2123.07   404.2 2128.88   444.4  2134.6   452.4 2136.91   496.6 2145.33
   524.8 2149.23   548.9  2154.8     589 2162.19   609.1 2167.27   647.4 2172.28
#Mann= 3 ,-1,0
       0      .1       0  295.82    .045       0  338.87      .1       0
#XS Ineff= 2 , 0
          261.11 2132.96
Permanent Ineff=
       F       F
Bank Sta=295.82,338.87
XS Rating Curve= 0 ,0
Exp/Cntr=0.3,0.1

Type RM Length L Ch R = 1 ,12671   ,497.9,494.8,491.9
XS GIS Cut Line= 3
     2265889.174      698359.3712266211.90375578697993.875051023
2266482.89601684697748.720839936
#Sta/Elev= 30
       0  2156.2    18.9 2154.78    56.3 2154.87      71 2153.39    77.4 2150.17
     115 2140.57   317.8 2119.65   332.4 2112.71   343.7 2112.22   355.1 2113.97
   376.5 2108.42   386.3 2107.56  409.99 2100.17   420.3 2098.34   463.8 2097.73
  476.412100.171   496.8 2110.27   506.5 2118.33   513.8 2120.93   563.5 2129.77
   587.4 2131.26   633.6 2137.12   643.6 2141.45   660.6 2144.96   692.9 2157.01
   715.2 2166.78   727.1 2174.52   736.1 2177.53   794.1 2181.09     853 2188.03
#Mann= 5 ,-1,0
       0     .06       0      30      .1       0  409.99    .045       0
  476.41      .1       0  727.59     .08       0
Bank Sta=409.99,476.41
XS Rating Curve= 0 ,0
Exp/Cntr=0.3,0.1

Type RM Length L Ch R = 1 ,12176   ,505.2,509.8,513.9
XS GIS Cut Line= 4
2266328.82243742698605.961227212 2266545.3414232698333.296132917
2266664.91594898698186.0145765342266760.43070802 697969.50260477
#Sta/Elev= 30
       0 2174.63    31.1  2170.4    42.8  2164.3    57.2 2161.36   123.6 2153.48
   133.8 2150.16     151 2149.68   205.3 2139.37   241.1 2120.36   266.6 2117.94
     327 2107.13   338.1 2101.91   350.3 2101.64   368.9 2092.36   427.1 2094.68
   438.4 2093.88  451.312089.769   485.9 2087.62   497.7 2090.59  507.092089.769
   535.1  2099.5   573.8 2106.01   613.1 2118.09   643.7 2130.81   661.2 2149.34
   664.9 2150.57   710.9 2157.81   735.1 2158.84   761.8 2169.64   774.5 2172.05
#Mann= 4 ,-1,0
       0      .1       0  451.31    .045       0  507.09      .1       0
  697.89     .08       0
Bank Sta=451.31,507.09
XS Rating Curve= 0 ,0
Exp/Cntr=0.3,0.1

Type RM Length L Ch R = 1 ,11666   ,502.2,490.1,473.7
XS GIS Cut Line= 3
 2266720.8598332698824.9908567762267068.19136765698516.088727862
2267164.09340016698271.583839936
#Sta/Elev= 30
       0 2193.44      39 2195.84    59.9 2199.88   138.3 2201.13   143.9 2195.63
   149.5 2173.41   156.2  2158.6   175.7 2149.06   211.9 2136.75   216.4 2132.32
   228.4 2113.42     240 2106.13   279.9 2092.94   294.6 2091.62  322.342079.716
     347 2077.43  374.162079.713     438 2085.97   451.1 2089.66   473.2 2089.42
   502.3 2094.72   510.9 2100.82     538 2099.62   575.4 2105.57   593.6 2130.72
   605.4 2139.66   626.9 2147.08   691.4 2154.95   710.9 2167.67   727.5 2174.53
#Mann= 3 ,-1,0
       0      .1       0  322.34    .045       0  374.16      .1       0
Bank Sta=322.34,374.16
XS Rating Curve= 0 ,0
Exp/Cntr=0.3,0.1