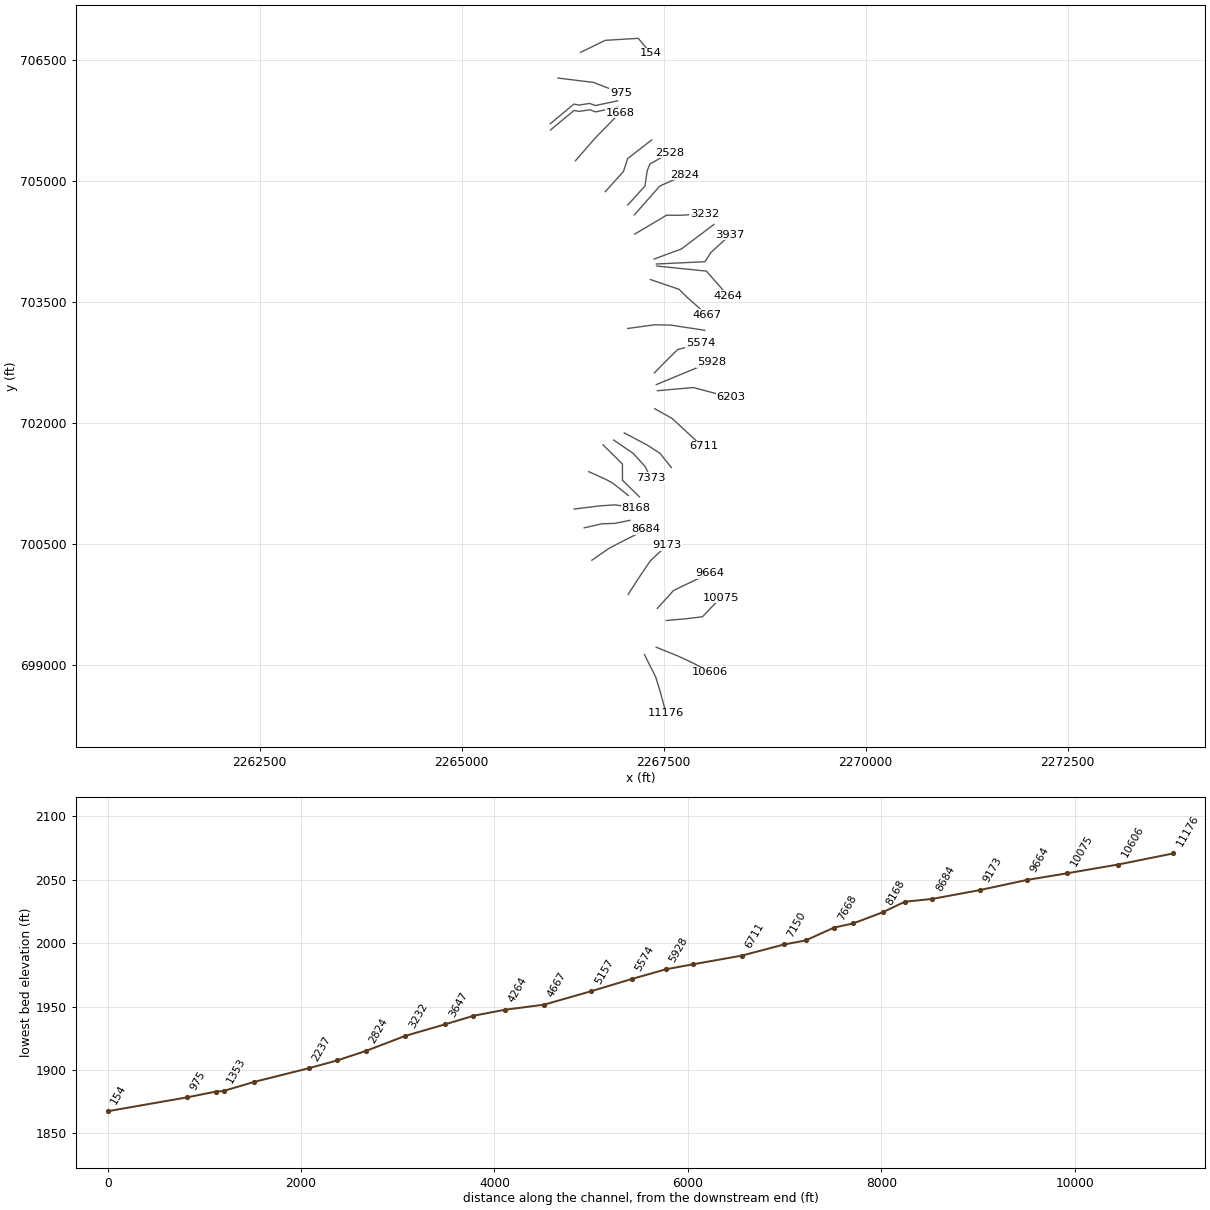
HEC-RAS study ROARCK.prj: ROARCK

--- ROARCK.g01 (geometry) --- (continued)

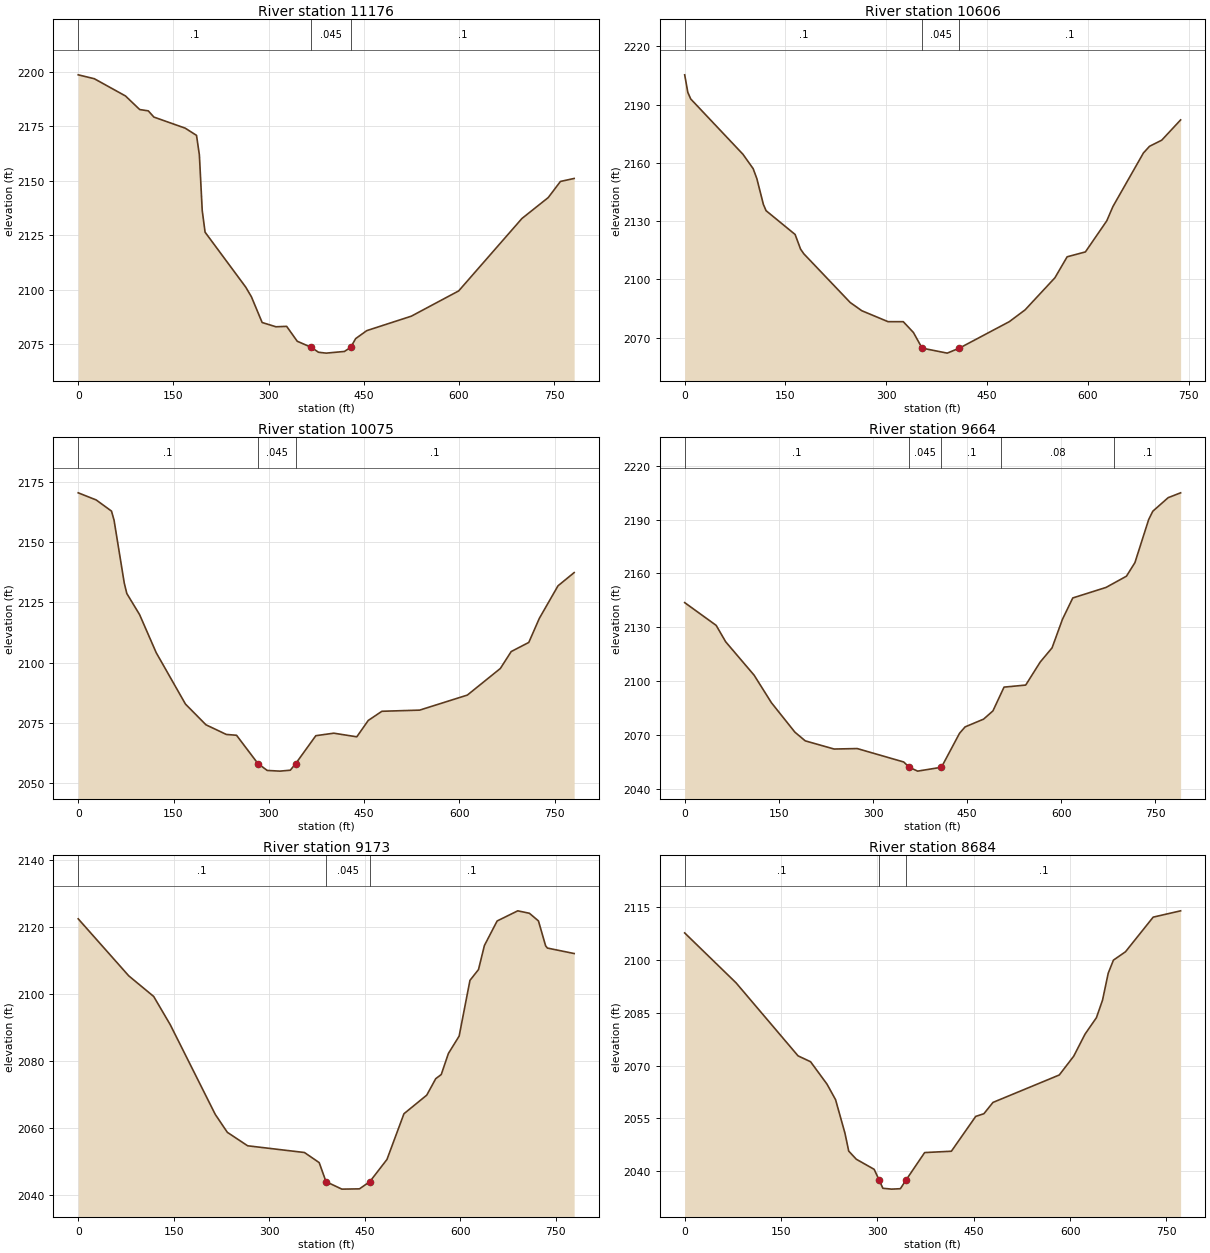
Type RM Length L Ch R = 1 ,11176   ,538.9,570.6,589.1
XS GIS Cut Line= 4
2267261.73538332 699131.802316762267400.73054338  698854.9748332
2267453.94513464698682.8436186732267531.43570008698401.857759904
#Sta/Elev= 30
       0 2198.66    25.3 2196.88    74.5 2188.95    96.9 2182.71   110.4 2182.11
   119.3 2179.24   168.5 2174.17   186.4 2170.85   190.9 2161.89   195.4 2136.34
   199.9 2126.37     264 2101.11   272.9 2096.69   289.8 2084.88   311.6 2082.91
   328.4 2083.12   345.1 2076.27  367.182073.478   378.6 2071.21   390.7 2070.81
   419.5 2071.58  429.292073.479   437.2  2077.5   454.7 2081.15   524.9 2087.79
   599.5  2099.4   699.1 2132.65   740.6 2142.28   759.8 2149.68   781.4 2151.05
#Mann= 3 ,-1,0
       0      .1       0  367.18    .045       0  429.29      .1       0
Bank Sta=367.18,429.29
XS Rating Curve= 0 ,0
Exp/Cntr=0.3,0.1

Type RM Length L Ch R = 1 ,10606   ,512.4,530.4,543.9
XS GIS Cut Line= 4
2267407.86060658699221.5311600642267680.92851043699110.767630678
2267861.90938645699027.1629521752268076.95571692698911.459860144
#Sta/Elev= 30
       0 2205.28     4.7 2196.23       9 2192.86    86.7 2164.41   101.9 2157.01
   107.4  2151.9   117.2 2138.56   121.2 2135.35   164.4 2123.12   172.5 2115.59
   177.3 2113.19   246.4 2088.11   263.6 2083.89   302.7 2078.25   325.4 2078.24
   340.5 2072.67  353.392064.632   390.8 2062.06  408.922064.632   483.3 2078.27
   506.7 2084.32   551.1 2100.84   569.3 2111.63   596.5 2114.15   628.3 2130.15
   637.4 2137.48   682.8 2165.05   691.9 2168.49   710.1 2171.65   738.2 2182.08
#Mann= 3 ,-1,0
       0      .1       0  353.39    .045       0  408.92      .1       0
Bank Sta=353.39,408.92
XS Rating Curve= 0 ,0
Exp/Cntr=0.3,0.1

Type RM Length L Ch R = 1 ,10075   ,399.3,411.8,418.4
XS GIS Cut Line= 4
2267531.98070307699552.665674219  2267773.932973699573.780998776
2267979.88476987699598.3249397492268208.56972196699836.697166423
#Sta/Elev= 30
       0 2170.36    28.3 2167.41    52.4 2162.79    56.4 2159.06    72.5 2132.98
    76.5 2128.67    96.6 2119.94   122.8 2104.15   168.8 2082.89     201 2074.32
   233.1 2070.31   249.2 2069.97  282.872058.256   297.5  2055.4   317.6 2055.12
   333.8  2055.5  342.392058.257     374 2069.79   402.2 2070.83   438.5 2069.33
   456.5  2076.1     478  2079.9   537.4 2080.38   612.5 2086.61   664.5 2097.64
   681.5 2104.63   709.2 2108.41   725.8 2118.38   755.2 2131.86   780.6 2137.33
#Mann= 3 ,-1,0
       0      .1       0  282.87    .045       0  342.39      .1       0
Bank Sta=282.87,342.39
XS Rating Curve= 0 ,0
Exp/Cntr=0.3,0.1

Type RM Length L Ch R = 1 ,9664    ,476.4,490.6,502.1
XS GIS Cut Line= 4
2267422.54665684699702.5168284182267621.13909623699922.745461928
2267744.76082842699983.0480695372268066.12234467700136.264463725
#Sta/Elev= 30
       0 2143.73    50.2 2131.05    65.3 2121.93   110.7 2103.29   138.2    2088
   175.6  2071.6   192.1 2066.76   238.1 2062.21   274.9 2062.47   348.9 2055.01
  357.812052.066   371.1 2049.91  409.062052.064   437.9 2070.98   446.7 2074.53
   476.2 2078.85   491.1 2083.45   508.8 2096.68   543.3 2097.82   566.4 2110.64
   585.3 2118.54   601.8  2134.4   618.3 2146.32   671.4  2152.2   703.8 2158.44
   717.3 2165.99   739.2 2189.96   745.8 2194.61   770.2 2202.14   790.1 2204.85
#Mann= 5 ,-1,0
       0      .1       0  357.81    .045       0  409.06      .1       0
  504.09     .08       0  684.09      .1       0
Bank Sta=357.81,409.06
XS Rating Curve= 0 ,0
Exp/Cntr=0.3,0.1

Type RM Length L Ch R = 1 ,9173    ,498.4,489.1,481.7
XS GIS Cut Line= 4
2267061.09796597699876.2738969692267213.28034313700111.984411195
2267334.14224007700290.5031188922267540.86372401700483.781135205
#Sta/Elev= 30
       0 2122.56    79.4 2105.54   118.6 2099.38   144.7 2090.92   215.3 2064.18
   234.3 2058.82   266.2  2054.8   355.5 2052.79   378.6 2049.78  389.35 2044.09
   414.2 2041.86   441.9 2041.94  458.182044.091   485.1 2050.72   511.8 2064.37
   547.6 2069.92   561.7 2074.83   570.4 2076.08   581.6 2082.35   598.5 2087.55
   615.5 2104.19   628.9 2107.41   638.2  2114.6   658.2 2121.92   690.6 2124.95
   708.9 2124.22   723.1 2121.94   734.4 2114.49   737.2 2113.83   779.2  2112.2
#Mann= 3 ,-1,0
       0      .1       0  389.35    .045       0  458.18      .1       0
Bank Sta=389.35,458.18
XS Rating Curve= 0 ,0
Exp/Cntr=0.3,0.1

Type RM Length L Ch R = 1 ,8684    ,296.9,286.2,276.6
XS GIS Cut Line= 4
2266611.23095454700298.781518489 2266817.5522056700442.095740366
2266940.55779381700507.9195277132267280.68862558700680.518744998
#Sta/Elev= 30
       0 2107.63      80 2093.47   176.5 2072.76     196 2071.09   221.6 2064.73
   234.9 2060.33   249.5 2050.84   255.4 2045.74   267.2 2043.43     295 2040.57
   302.82037.505   308.6 2035.19   322.2 2034.95   335.8 2035.07  344.552037.508
   373.6 2045.32   415.2  2045.7   453.1 2055.58   465.8 2056.34     480 2059.55
   583.2 2067.33   605.7 2072.67   623.3 2078.92     641 2083.58   650.5 2088.54
   659.4 2096.21   667.5 2099.91   686.3 2102.29   729.4 2112.11   772.1  2113.9
#Mann= 3 ,-1,0
       0      .1       0   302.8    .045       0  344.55      .1       0
Bank Sta=302.8,344.55
XS Rating Curve= 0 ,0
Exp/Cntr=0.3,0.1

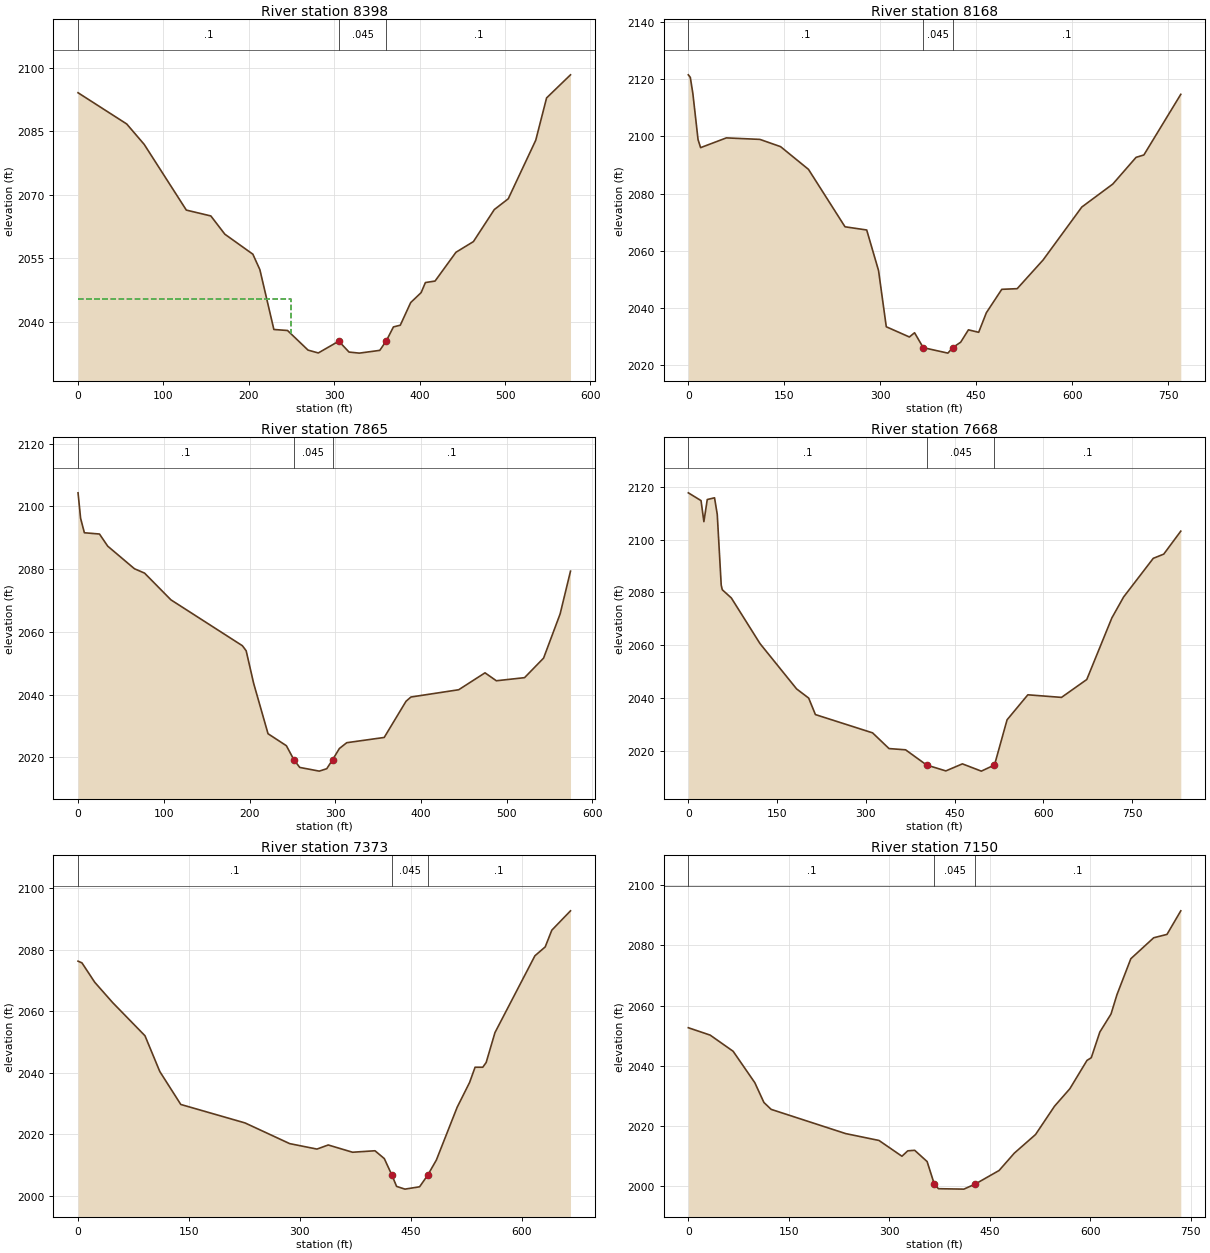
Type RM Length L Ch R = 1 ,8398    ,232.1,230.1,237.4
XS GIS Cut Line= 4
 2266516.5442286700700.5295283752266738.77689903700750.887670443
2266892.04080967700755.2666393182267083.62069797700793.582616978
#Sta/Elev= 30
       0 2094.12      57 2086.75    77.5 2081.92   126.8 2066.42   155.5 2065.04
   171.9 2060.73   204.7 2056.01   212.9 2052.36   229.3 2038.24   245.3    2038
   269.3 2033.37   281.3  2032.7   305.3 2035.48   317.3 2032.91   329.3 2032.66
   353.3 2033.31  360.94 2035.57   369.3 2038.85   377.3 2039.25   389.5  2044.6
   401.7 2046.94   406.7 2049.32     418 2049.67   442.5 2056.47   462.9 2058.98
   487.4 2066.55   503.7 2069.09   535.9 2082.91   548.6  2092.9   576.6 2098.35
#Mann= 3 ,-1,0
       0      .1       0   305.3    .045       0  360.94      .1       0
#XS Ineff= 2 , 0
          249.17 2045.42
Permanent Ineff=
       F       F
Bank Sta=305.3,360.94
XS Rating Curve= 0 ,0
Exp/Cntr(USF)=0,0
Exp/Cntr=0.3,0.1

Type RM Length L Ch R = 1 ,8168    ,320.7,302.8,294.9
XS GIS Cut Line= 4
2266393.09284388      700933.3272266703.25845137700971.784911905
2266897.29043172700985.2152085672267157.37265222700948.261793937
#Sta/Elev= 30
       0 2121.53     3.1 2120.64     7.1 2114.99    15.2 2098.89    19.2 2096.09
    59.5  2099.5   111.9 2098.97   144.2 2096.44   187.8  2088.5   244.9 2068.44
   278.8 2067.32   297.3 2053.16   309.4 2033.51   345.5 2029.94   353.6 2031.42
  367.152026.219   405.7  2024.3  413.222026.217   425.7 2028.13   437.8 2032.44
   453.8 2031.57   465.8 2038.41   489.9 2046.59     514 2046.82   554.4 2056.82
     615 2075.34   663.5 2083.38   699.8  2092.7     712 2093.53   769.7 2114.72
#Mann= 3 ,-1,0
       0      .1       0  367.15    .045       0  413.22      .1       0
Bank Sta=367.15,413.22
XS Rating Curve= 0 ,0
Exp/Cntr=0.3,0.1

Type RM Length L Ch R = 1 ,7865    ,245.8,196.7,169.1
XS GIS Cut Line= 4
 2266573.4190152701396.2363063032266783.28109855701301.650578594
2266872.94048628701252.387178745 2267062.1119417701101.641175208
#Sta/Elev= 30
       0 2104.29       3 2096.16     7.4 2091.56      25 2091.16    34.6  2087.3
    65.8 2080.09    77.6  2078.7   108.3 2070.19   191.7 2055.56   196.1 2053.95
   204.8  2043.6   221.6 2027.51     243 2023.69   251.8 2019.21   258.6 2016.77
   281.4 2015.59   290.1 2016.37  296.842019.196   304.8 2022.79   313.4 2024.65
   357.1 2026.32   382.6 2037.87   388.3 2039.21     444 2041.53   474.7 2046.92
   487.9 2044.39   520.8 2045.38     543 2051.61   562.3  2065.7   574.4 2079.33
#Mann= 3 ,-1,0
       0      .1       0   251.8    .045       0  296.84      .1       0
Bank Sta=251.8,296.84
XS Rating Curve= 0 ,0
Exp/Cntr(USF)=0,0
Exp/Cntr=0.3,0.1

Type RM Length L Ch R = 1 ,7668    ,245.4,295.5,321.2
XS GIS Cut Line= 4
2266750.13965315701728.3317572062266990.13014071701490.593439569
 2266990.2821379701289.7000676952267200.53889343701084.720380696
#Sta/Elev= 30
       0 2117.72    21.5 2114.77    26.3  2106.8      32 2115.18    44.3 2115.84
    48.9 2109.55    55.6 2082.76    57.4 2081.02    72.7 2077.91   121.1 2060.65
     183 2043.47   203.4    2040   214.8 2033.75   311.4 2026.83   339.2 2020.88
   367.2 2020.41  402.682014.663   435.2 2012.42   463.2 2015.09   495.2 2012.34
  517.452014.664   538.7 2031.77   573.8 2041.24   630.7 2040.26   673.4 2047.03
   715.8 2070.35   735.6 2078.26   785.8 2092.92   803.5 2094.51   832.3 2103.21
#Mann= 3 ,-1,0
       0      .1       0  402.68    .045       0  517.45      .1       0
Bank Sta=402.68,517.45
XS Rating Curve= 0 ,0
Exp/Cntr=0.3,0.1

Type RM Length L Ch R = 1 ,7373    ,216.5,223,229.5
XS GIS Cut Line= 4
2266881.50027777 701788.153101822267122.40494717701623.474339742
2267271.04218346 701460.316802392267337.64286896701322.414622042
#Sta/Elev= 30
       0 2076.25     5.3 2075.69    22.6 2069.38    46.8 2062.78    90.5    2052
   110.5 2040.39   138.9 2029.67   225.7 2023.67   286.1 2016.94     323 2015.17
   338.2  2016.5   371.1 2014.14   401.4 2014.62     414 2012.08  424.322006.691
   430.6 2003.04   441.9 2002.15   461.7 2002.91   472.6 2006.66   484.4 2011.62
   512.5 2028.77   529.3 2036.83   536.7 2041.77   547.1 2041.77   551.7 2043.31
   563.6 2053.04   617.6    2078   631.5 2080.88   640.4 2086.31   665.7 2092.61
#Mann= 3 ,-1,0
       0      .1       0  424.32    .045       0   472.6      .1       0
Bank Sta=424.32,472.6
XS Rating Curve= 0 ,0
Exp/Cntr(USF)=0,0
Exp/Cntr=0.3,0.1

Type RM Length L Ch R = 1 ,7150    ,445.1,438.8,434.5
XS GIS Cut Line= 4
2267012.31699326701876.4027733762267293.51069864701728.085704758
2267455.41569326701623.1074236562267595.71579358701447.787229992
#Sta/Elev= 30
       0 2052.62    32.6 2050.17    66.9  2044.8    99.3 2034.35   112.9 2027.77
   123.7 2025.48     235 2017.43   284.7 2015.15     319  2009.9   327.7  2011.7
     338 2011.88   356.6 2008.13  367.282000.654   373.5 1999.11   411.5 1998.97
  428.452000.657   464.1 2005.17   486.8 2010.93   518.5 2017.12   546.9 2026.55
   569.7 2032.33   595.3 2041.75   601.7 2042.65   614.5 2051.18   631.2 2057.17
   640.1 2063.62   660.8 2075.56   694.9 2082.52   714.8 2083.65   735.4 2091.48
#Mann= 3 ,-1,0
       0      .1       0  367.28    .045       0  428.45      .1       0
Bank Sta=367.28,428.45
XS Rating Curve= 0 ,0
Exp/Cntr=0.3,0.1

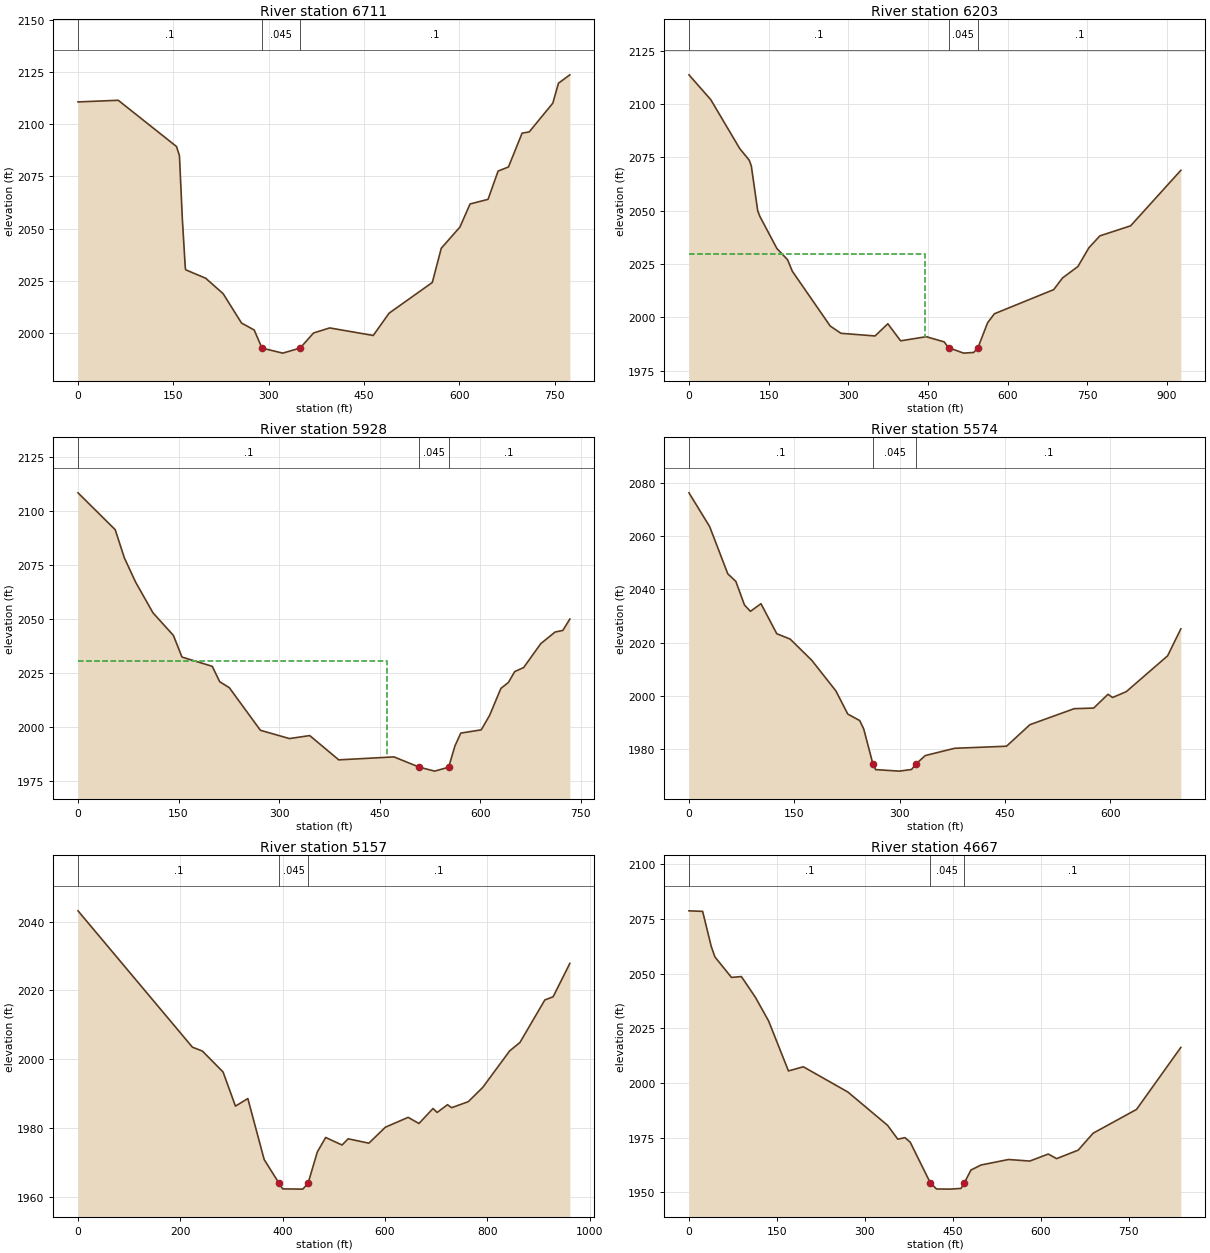
Type RM Length L Ch R = 1 ,6711    ,493.6,507.7,521.3
XS GIS Cut Line= 4
2267388.98539871702176.802721852 2267606.0190155702054.954086545
2267950.29733713701735.890178084     2268000.311      701711.713
#Sta/Elev= 30
       0 2110.78    63.3 2111.57     155 2089.36   159.6 2084.93   164.2 2054.37
   168.8  2031.1   169.5 2030.16   200.9 2026.12   228.4 2018.68   257.3  2004.6
   277.2 2001.27  289.421992.586   322.1 1990.16  349.421992.586   370.6 1999.84
     396 2002.26   464.5 1998.64   489.4 2009.34   557.4 2024.08   571.5 2040.51
   600.9 2050.71   616.8 2061.78   645.1    2064   660.9 2077.57   677.2 2079.55
   698.7 2095.78   709.9 2096.39     747 2110.18   755.9 2119.77   773.8 2123.79
#Mann= 3 ,-1,0
       0      .1       0  289.42    .045       0  349.42      .1       0
Bank Sta=289.42,349.42
XS Rating Curve= 0 ,0
Exp/Cntr=0.3,0.1

Type RM Length L Ch R = 1 ,6203    ,256.8,274.6,290.2
XS GIS Cut Line= 3
2267423.28958797702399.0006895112267867.13313623702438.711654826
2268331.51020643702315.720413707
#Sta/Elev= 30
       0 2113.71      41 2102.08    95.6 2079.13   113.3 2073.74   117.4 2070.99
   129.4 2050.04   133.4 2047.39   165.5 2032.31   185.6 2027.07   194.5 2021.67
   265.9 1995.97     286 1992.56   350.3 1991.31   374.4 1997.03   398.5 1989.02
   446.7 1990.97   480.4 1988.54  488.791985.825     517 1983.26   536.1 1983.58
  544.071985.824   562.2 1997.48     575 2001.71   686.7 2013.03   703.2 2018.48
   732.2 2023.85   752.9 2032.63   773.6 2038.22   831.5 2042.94     926 2068.95
#Mann= 3 ,-1,0
       0      .1       0  488.79    .045       0  544.07      .1       0
#XS Ineff= 2 , 0
          444.77 2029.91
Permanent Ineff=
       F       F
Bank Sta=488.79,544.07
XS Rating Curve= 0 ,0
Exp/Cntr=0.3,0.1

Type RM Length L Ch R = 1 ,5928    ,350.9,354.8,360.3
XS GIS Cut Line= 4
2267408.90991986702474.6353830752267851.03908082702658.190810912
 2267944.4129289702697.2960977122268088.86306993 702749.96852483
#Sta/Elev= 30
       0 2108.33    55.5 2091.25    69.2 2078.17    85.8 2067.05   111.8 2052.77
   142.3 2042.29   155.1 2032.27   200.3 2027.97   211.4 2020.83   225.7 2018.09
   272.1 1998.35   315.4 1994.51   345.7 1995.89     389 1984.65   471.3 1986.02
   509.4 1981.24     532 1979.43  552.871981.236   562.3  1991.1     571 1997.04
   601.5 1998.55     614 2005.25   630.8 2017.72   642.1 2020.52   651.4 2025.52
   664.8 2027.41   690.4  2038.5   711.7 2043.86   723.2 2044.59   733.7 2049.87
#Mann= 3 ,-1,0
       0      .1       0   509.4    .045       0  552.87      .1       0
#XS Ineff= 2 , 0
          461.52  2030.3
Permanent Ineff=
       F       F
Bank Sta=509.4,552.87
XS Rating Curve= 0 ,0
Exp/Cntr(USF)=0,0
Exp/Cntr=0.3,0.1

Type RM Length L Ch R = 1 ,5574    ,442.7,416.6,395.6
XS GIS Cut Line= 4
2267385.29813986702620.2678298322267561.55151475702798.701655328
2267672.73746774702908.5490879732267955.96918027702984.507323496
#Sta/Elev= 30
       0 2076.19    29.4 2063.54    55.3 2045.77    66.7 2042.98      79  2034.1
    87.5 2031.71   102.5 2034.58     125 2023.32   144.1 2021.29   174.9 2013.32
   209.2 2001.84   226.1 1993.16   243.1 1990.72   248.8 1987.58  261.851974.477
   265.7 1972.31   299.5 1971.74   316.9 1972.36   323.4 1974.48   336.4 1977.58
   378.2 1980.31   452.1 1981.09   485.5 1989.18   548.5 1995.18   576.3 1995.41
   596.6 2000.59   603.1 1999.37   622.7 2001.58   681.5 2015.02   700.3 2025.13
#Mann= 3 ,-1,0
       0      .1       0  261.85    .045       0   323.4      .1       0
Bank Sta=261.85,323.4
XS Rating Curve= 0 ,0
Exp/Cntr=0.3,0.1

Type RM Length L Ch R = 1 ,5157    ,510.1,489.9,466.6
XS GIS Cut Line= 4
2267055.28951109703170.3819704182267387.70823961703215.561982992
2267586.08229355703212.319421747 2268008.5401742703147.929692685
#Sta/Elev= 30
       0 2043.15   223.6 2003.47   243.1 2002.34   283.5 1996.25   307.7 1986.32
   331.9 1988.52   363.9 1970.74     3931963.853     400 1962.23   439.3 1962.16
  449.561963.854   467.7 1972.98     484 1977.19     516    1975     528 1976.81
   568.4 1975.53   600.7 1980.18   645.2 1983.05   666.3 1981.26   693.8 1985.62
   701.9 1984.48   722.1 1986.73   730.2 1985.86   762.6  1987.6   790.9 1991.75
   843.5 2002.37   863.7 2004.84   912.3 2017.21   928.5 2018.14   961.2 2027.86
#Mann= 3 ,-1,0
       0      .1       0     393    .045       0  449.56      .1       0
Bank Sta=393,449.56
XS Rating Curve= 0 ,0
Exp/Cntr=0.3,0.1

Type RM Length L Ch R = 1 ,4667    ,405.8,402.7,402.3
XS GIS Cut Line= 4
2267335.55348151703776.7054149512267690.83712739703655.467732124
2267793.77013907703553.6218609262268032.94139276703342.798518489
#Sta/Elev= 30
       0 2078.79    23.3 2078.54    37.9 2062.59    44.2 2057.72    72.5 2048.33
    89.4 2048.72   113.6 2039.11   135.9 2028.37   169.7 2005.55   195.1 2007.45
   271.1  1995.9   338.8 1980.66   356.2 1974.34   368.4 1975.04   377.3    1973
  411.731954.337   422.3 1951.56   444.8 1951.49     464 1951.81  469.691954.336
     481 1960.22   498.1 1962.52   545.1 1965.04   581.4 1964.33   612.9 1967.55
   627.1 1965.44   663.9 1969.32   689.4 1977.07   763.4 1987.94     839 2016.31
#Mann= 3 ,-1,0
       0      .1       0  411.73    .045       0  469.69      .1       0
Bank Sta=411.73,469.69
XS Rating Curve= 0 ,0
Exp/Cntr=0.3,0.1

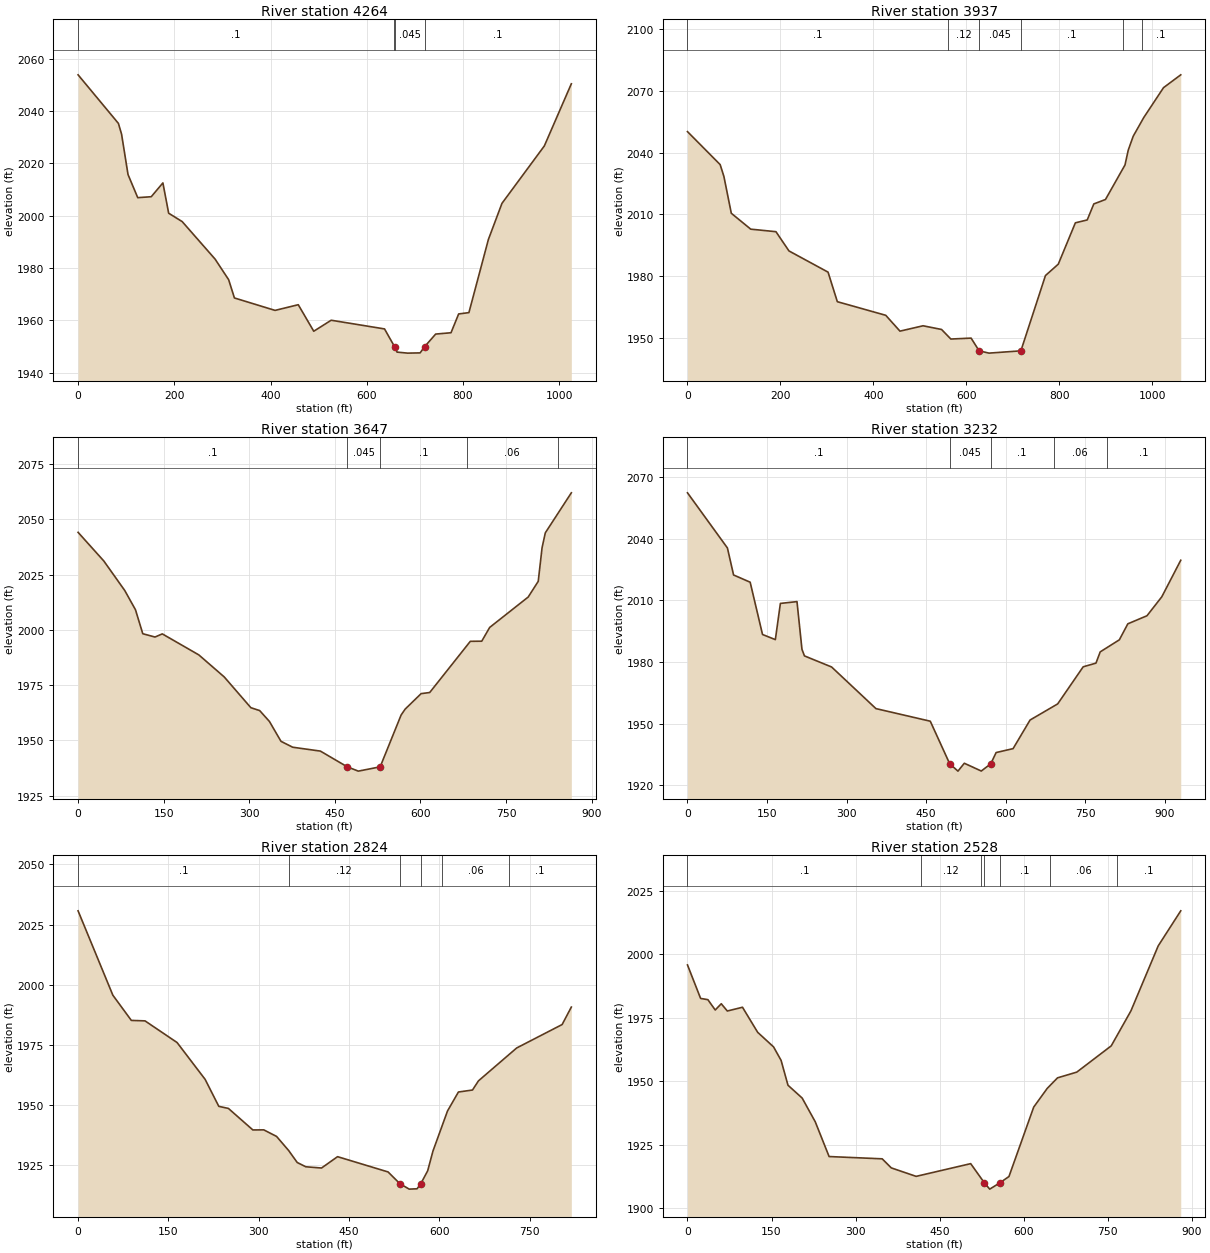
Type RM Length L Ch R = 1 ,4264    ,242.7,327.9,382.3
XS GIS Cut Line= 3
2267416.82666994703943.8305190182268029.63863312703880.954519018
2268299.11604524703572.932103172
#Sta/Elev= 30
       0 2053.85    83.8  2035.3    90.4 2031.19   103.8 2015.76     124 2006.91
   152.1 2007.27   176.3 2012.55   188.3 2000.97   216.5 1997.75   284.8 1983.43
     313 1975.56     325 1968.58   409.5 1963.83   457.7    1966   489.9 1955.86
   526.1 1960.07     637 1956.75  657.981949.928     663 1947.89   684.8  1947.5
     711 1947.59  720.15 1949.93   743.3 1954.78   775.2 1955.29   791.1 1962.47
   812.4 1962.98   852.9 1990.93   881.1 2004.73   969.2 2026.68  1025.3 2050.42
#Mann= 4 ,-1,0
       0      .1       0  656.03     .12       0  657.98    .045       0
  720.15      .1       0
Bank Sta=657.98,720.15
XS Rating Curve= 0 ,0
Exp/Cntr=0.3,0.1

Type RM Length L Ch R = 1 ,3937    ,300.6,289.5,276.1
XS GIS Cut Line= 4
2267409.99286632703968.9152668962268011.99161247703997.488038808
2268084.90144425704110.7938584612268323.33629952704330.508621787
#Sta/Elev= 30
       0 2050.12    70.3 2034.14    78.3 2028.45    94.3 2010.54   136.1 2002.84
   190.4 2001.61   218.4 1992.28   302.5    1982   322.5 1967.67   426.7 1961.07
   457.3 1953.39     507 1955.99   546.8  1954.2   566.8 1949.56   610.4 1950.01
  627.621943.851   648.9 1942.73  717.54 1943.84   770.4 1980.33     798 1985.86
   834.8 2005.91   860.3  2007.3   874.5 2015.07   899.6 2017.22   941.6 2033.97
   948.6 2041.15   959.3 2047.91     982 2056.96  1024.5 2071.44  1061.6 2077.67
#Mann= 6 ,-1,0
       0      .1       0     560     .12       0  627.62    .045       0
  717.54      .1       0  937.41     .06       0  977.41      .1       0
Bank Sta=627.62,717.54
XS Rating Curve= 0 ,0
Exp/Cntr(USF)=0,0
Exp/Cntr=0.3,0.1

Type RM Length L Ch R = 1 ,3647    ,445.3,415.4,394.7
XS GIS Cut Line= 3
2267381.87043122704030.1999134552267720.04692062704155.928617963
2268122.58462005704458.613343128
#Sta/Elev= 30
       0 2044.14    45.1 2031.17    81.9 2017.77   100.6 2009.09   113.4 1998.24
   134.8 1996.75   147.6 1998.17   211.6 1988.66   256.1 1978.69   302.8 1964.76
   318.3 1963.45   335.3 1958.55   355.6 1949.54   376.1 1946.87   424.6 1945.12
  471.761937.995   491.1 1936.05  529.411937.995   566.1 1961.44   573.2 1964.12
   601.2 1971.13   616.2 1971.63   687.4 1994.81   707.4 1994.86   721.3 2001.09
   788.8 2014.85   806.4 2021.96   813.1 2037.14   818.8 2043.91   864.4 2062.02
#Mann= 5 ,-1,0
       0      .1       0  471.76    .045       0  529.41      .1       0
  680.79     .06       0  840.79      .1       0
Bank Sta=471.76,529.41
XS Rating Curve= 0 ,0
Exp/Cntr=0.3,0.1

Type RM Length L Ch R = 1 ,3232    ,394,408.2,419.6
XS GIS Cut Line= 4
2267142.56351066704339.6275576632267536.97354367704574.165352066
2267708.77177806704572.3516973682268007.82682282704591.385966346
#Sta/Elev= 30
       0 2062.27    75.3 2035.44    86.9  2022.3   118.2 2018.78   141.5 1993.34
   165.7 1990.85   175.2 2008.46   206.5 2009.34   215.9 1986.12   220.6 1982.92
   271.8 1977.53   355.4 1957.28   457.9 1951.15  494.55 1930.43   510.1 1926.86
   522.1 1930.69   554.1 1926.91  571.991930.426   582.1  1935.9   614.1 1937.81
   646.1 1951.72   698.2 1959.57   746.3 1977.62   770.4 1979.41   778.4 1984.88
   814.5 1990.75   830.5 1998.53   866.6 2002.46   894.6  2011.7   930.3 2029.46
#Mann= 5 ,-1,0
       0      .1       0  494.55    .045       0  571.99      .1       0
  690.68     .06       0  790.68      .1       0
Bank Sta=494.55,571.99
XS Rating Curve= 0 ,0
Exp/Cntr=0.3,0.1

Type RM Length L Ch R = 1 ,2824    ,284.2,295.4,308.4
XS GIS Cut Line= 3
2267137.61274302704577.8074103692267451.89991992704934.234766745
2267765.93484326705075.478640361
#Sta/Elev= 30
       0 2030.69    57.8 1995.59    88.5 1985.11   111.2 1984.92   164.5 1975.91
   211.1 1960.59   233.8 1949.37   249.8  1948.5   290.4 1939.55   308.5 1939.59
   329.8 1936.86     350 1930.95   364.1 1926.01   378.3 1924.24   404.5 1923.72
   431.1 1928.44     515 1922.09  534.68  1917.2   550.1 1914.94   563.2 1915.08
  569.371917.201   580.8 1922.54   589.6 1930.76   613.8 1947.45   631.9 1955.33
   655.3 1956.16   665.2 1959.97   728.7 1973.65   804.2 1983.39   819.5 1990.65
#Mann= 6 ,-1,0
       0      .1       0     350     .12       0  534.68    .045       0
  569.37     .12       0   605.2     .06       0   715.2      .1       0
Bank Sta=534.68,569.37
XS Rating Curve= 0 ,0
Exp/Cntr=0.3,0.1

Type RM Length L Ch R = 1 ,2528    ,297.6,291.4,285.2
XS GIS Cut Line= 5
 2267055.6385013704700.5994301722267269.29143368704935.019622448
2267295.34252771705120.212054817 2267328.8671836 705206.65217059
2267575.03286514705347.713719545
#Sta/Elev= 30
       0 1995.84    23.4 1982.65    36.4 1982.16    49.5 1978.09    60.3 1980.55
    71.1 1977.69    98.2 1979.17   125.3 1969.29   153.7 1963.54   167.1 1958.23
   179.4 1948.44   204.7 1943.39   228.1 1934.03   252.8 1920.34   347.6 1919.44
   363.8 1915.87   408.2 1912.53   505.6 1917.54   530.11909.949   539.6  1907.5
  557.431909.944   573.9 1912.46   618.1 1939.83   642.2 1947.19   660.6 1951.35
     695 1953.61   756.5 1963.96   791.7 1977.76   840.4 2003.37   880.6 2017.17
#Mann= 7 ,-1,0
       0      .1       0  417.18     .12       0  524.19      .1       0
   530.1    .045       0  557.43      .1       0   646.9     .06       0
   766.9      .1       0
Bank Sta=530.1,557.43
XS Rating Curve= 0 ,0
Exp/Cntr(USF)=0,0
Exp/Cntr=0.3,0.1

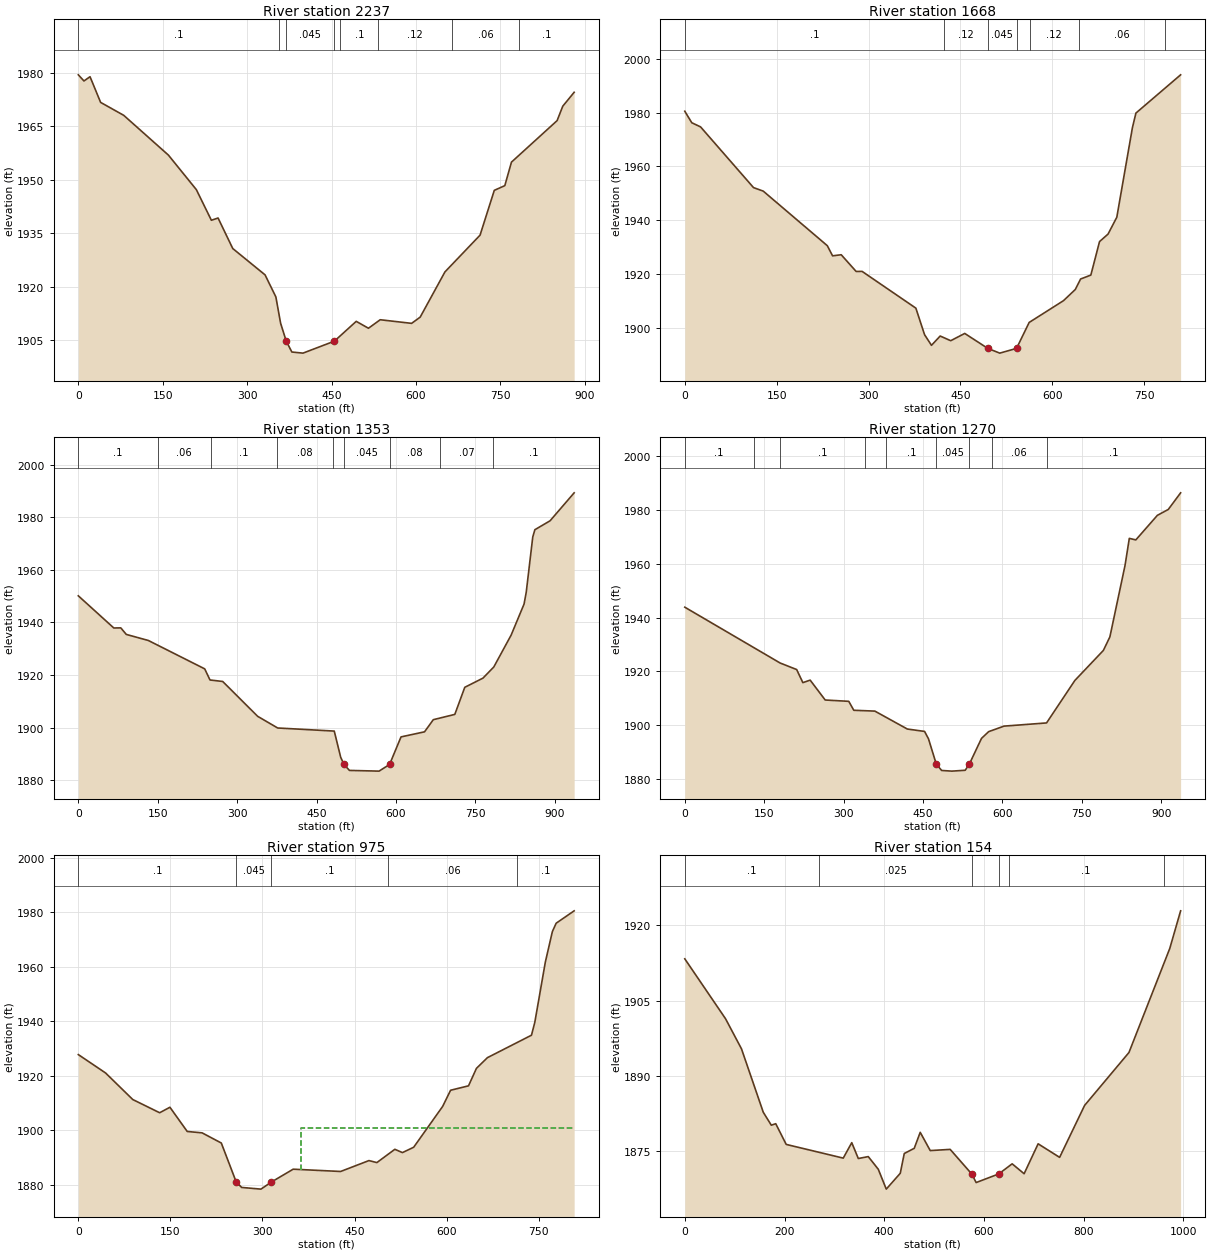
Type RM Length L Ch R = 1 ,2237    ,587.4,568.4,537.7
XS GIS Cut Line= 4
2266777.57105157704865.7275869092267002.81416528705114.630036788
2267054.04377767705274.2091360232267352.13069856 705506.20533334
#Sta/Elev= 30
       0 1979.35      10 1977.63    20.8 1978.82    39.6 1971.63    80.7    1968
     160 1956.87   209.7 1947.19   236.4 1938.61   248.3 1939.24   274.4 1930.69
   331.8 1923.31     351 1917.14   359.4 1909.77  369.421904.748   379.4  1901.7
   399.2 1901.39  454.961904.746   493.8 1910.29   515.5 1908.36   536.4 1910.74
   592.2 1909.73   607.4 1911.47   651.4 1924.14   713.8 1934.44   739.1 1946.99
   757.8 1948.31   769.6 1954.89   850.7 1966.52   860.8 1970.57     881 1974.46
#Mann= 8 ,-1,0
       0      .1       0  355.69     .12       0  369.42    .045       0
  454.96     .12       0  465.69      .1       0  533.29     .12       0
  663.29     .06       0  783.29      .1       0
Bank Sta=369.42,454.96
XS Rating Curve= 0 ,0
Exp/Cntr=0.3,0.1

Type RM Length L Ch R = 1 ,1668    ,339,315,288.2
XS GIS Cut Line= 3
2266408.41359724705248.5660917162266653.62473323705530.126328108
2266958.75525025 705841.89798312
#Sta/Elev= 30
       0  1980.5    11.4 1976.22    25.8 1974.67   112.2  1952.1   128.1 1950.79
   232.7  1930.5   241.3 1926.72   255.4 1927.13   279.8 1920.91   289.5 1920.94
   377.3 1907.27   391.5  1897.4   402.8 1893.44     417  1896.9   434.2 1895.16
   457.1 1897.86  494.74  1892.3   514.3 1890.54  541.69  1892.3   562.3 1901.95
   618.3 1910.04   637.6  1914.2   646.3 1918.11     663 1919.56   677.2 1932.02
   691.1 1934.81   705.4 1941.08   730.9  1974.4   736.6 1979.81   809.6 1994.04
#Mann= 7 ,-1,0
       0      .1       0  423.37     .12       0  494.74    .045       0
  541.69      .1       0  563.37     .12       0  643.37     .06       0
  783.37      .1       0
Bank Sta=494.74,541.69
XS Rating Curve= 0 ,0
Exp/Cntr=0.3,0.1

Type RM Length L Ch R = 1 ,1353    ,80.4,83.7,89.5
XS GIS Cut Line= 6
2266098.54889793705628.4870528352266391.32012879705871.808697574
2266449.90077983705859.4416712422266587.23986173705879.619451047
2266656.23485073705853.5836061382266932.73359203705911.613297516
#Sta/Elev= 30
       0 1950.11      67 1937.88    80.2 1937.92    90.6 1935.43   132.3 1933.12
   238.7 1922.33   248.7  1918.1   272.7 1917.53   338.7 1904.28   376.5 1899.84
   483.4 1898.66   495.5 1888.73  501.771885.961   512.1  1883.7     568 1883.43
  587.85 1885.96   609.5 1896.45   653.9 1898.38   670.5    1903   711.1 1905.01
   729.9 1915.31   764.3 1918.81   784.7 1923.04   817.4 1935.14   841.9 1946.99
     846  1951.5   858.3 1972.47   862.3 1975.26     891 1978.65   936.5 1989.29
#Mann= 9 ,-1,0
       0      .1       0     150     .06       0     250      .1       0
  375.04     .08       0  480.77     .06       0  501.77    .045       0
  587.85     .08       0  683.96     .07       0  783.96      .1       0
Bank Sta=501.77,587.85
XS Rating Curve= 0 ,0
Exp/Cntr(USF)=0,0
Exp/Cntr=0.3,0.1

Type RM Length L Ch R = 1 ,1270    ,303.2,295.1,288.2
XS GIS Cut Line= 6
2266096.76317469705707.0588756062266389.53440554705950.380520345
2266448.11505659705938.0134940132266585.45413848705958.191273817
2266654.44912749705932.1554289082266930.94786879705990.185120286
#Sta/Elev= 30
       0 1943.88     180 1923.11   211.3 1920.67     223  1915.8   236.8 1916.73
   265.2 1909.33   309.7 1908.84   319.2 1905.51     359  1905.2   420.3 1898.53
   452.9 1897.64   460.3 1894.88     4751885.474   485.2  1883.1   504.5 1882.86
   529.6 1883.18  537.441885.474   560.4 1895.04   573.9 1897.55   602.9 1899.61
   683.3  1900.8   736.8 1916.62   790.6 1927.79   802.9 1932.83   831.5 1959.42
   839.6  1969.5   851.9 1968.93   892.6 1978.07   913.2 1980.26   936.5 1986.45
#Mann= 9 ,-1,0
       0      .1       0     130     .06       0     180      .1       0
     340     .06       0  380.69      .1       0     475    .045       0
  537.44     .08       0  579.61     .06       0  683.96      .1       0
Bank Sta=475,537.44
XS Rating Curve= 0 ,0
Exp/Cntr(USF)=0,0
Exp/Cntr=0.3,0.1

Type RM Length L Ch R = 1 ,975     ,807.2,820.4,813.2
XS GIS Cut Line= 3
2266192.11541323706272.8274198692266633.10962327 706218.29156218
2266971.93476473706086.975803707
#Sta/Elev= 30
       0 1927.76    44.4 1921.01    88.7 1911.26   132.5 1906.41   149.2 1908.43
   177.4 1899.54   201.6 1899.03   232.9  1895.3  257.191880.997   266.1 1878.99
   297.5 1878.37  314.651880.995     350 1885.69   427.3 1884.85   473.4 1888.85
   486.3 1888.11   515.6 1892.99     528 1891.78   546.3 1893.75   593.5 1908.74
   606.4 1914.67   635.6 1916.29   648.5  1922.7   666.4 1926.63   738.2 1934.88
   743.6 1939.62   760.8 1961.77   772.2 1972.91   778.4 1975.99   807.7 1980.54
#Mann= 5 ,-1,0
       0      .1       0  257.19    .045       0  314.65      .1       0
  504.35     .06       0  714.35      .1       0
#XS Ineff= 2 , 0
                          362.13         1900.89
Permanent Ineff=
       F       F
Bank Sta=257.19,314.65
XS Rating Curve= 0 ,0
Exp/Cntr=0.3,0.1

Type RM Length L Ch R = 1 ,154     ,,,
XS GIS Cut Line= 4
2266470.84445242706590.3919006382266775.58364537 706739.81042113
2267185.73012586706764.7963437952267342.15923092706577.295971686
#Sta/Elev= 30
       0 1913.32    81.7 1901.39   113.7 1895.39   157.4 1882.75   173.5 1880.17
   182.4 1880.47   203.4 1876.34   317.8 1873.61   334.9 1876.69     348 1873.53
     368 1873.91   388.1 1871.39   404.1 1867.43   432.2 1870.59   440.2 1874.53
   460.2 1875.56   472.2 1878.75   492.3 1875.11   532.3 1875.35   575.4 1870.46
   584.4 1868.74  629.691870.458   656.6 1872.47   680.6  1870.5   708.7 1876.46
   751.8 1873.76   801.9 1884.11   890.9 1894.66   972.7 1915.38   994.5 1922.89
#Mann= 6 ,-1,0
       0      .1       0     270    .025       0   575.4    .045       0
  629.69    .025       0   649.4      .1       0  960.31     .06       0
Bank Sta=575.4,629.69
XS Rating Curve= 0 ,0
Exp/Cntr=0.3,0.1
LCMann Table=0

Chan Stop Cuts=-1
Use User Specified Reach Order=0
Composite Channel Slope=5